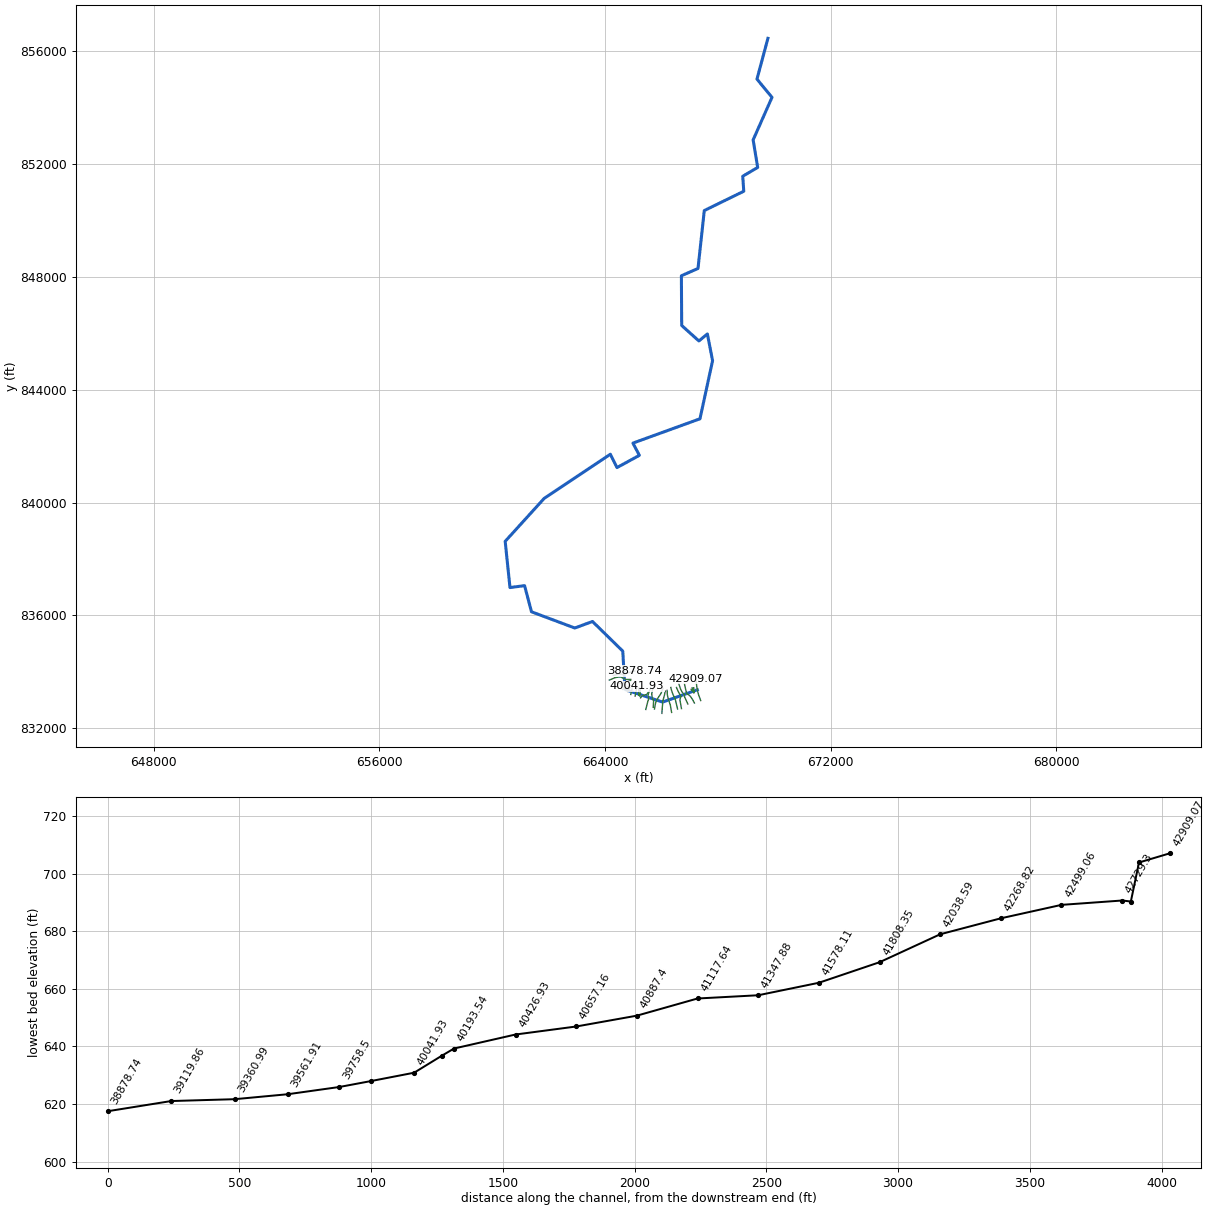
--- 13678_ras.prj (project) ---

Proj Title=13678
Current Plan=p01
Default Exp/Contr=0.3,0.1
English Units
Geom File=g01
Flow File=f01
Plan File=p01
Y Axis Title=Elevation
X Axis Title(PF)=Main Channel Distance
X Axis Title(XS)=Station
BEGIN DESCRIPTION:
RFD model 13678 exported to HEC-RAS
END DESCRIPTION:

--- 13678_ras.p01 (plan) ---

Plan Title=Plan 01
Program Version=4.10
Short Identifier=Plan 01
Geom File=g01
Flow File=f01
Subcritical Flow
Calc Critical at every XS
Secant Critical Depth

--- 13678_ras.f01 (steady flow) ---

Flow Title=Flow 01
Program Version=5.01
Number of Profiles= 6
Profile Names=10yr,25yr,50yr,100yr,100plus,500yr
River Rch & RM=13678,168,42909.07
  322.31  515.31  695.69  859.62 1255.05 1986.37
River Rch & RM=13678,168,42793.23
  327.23  523.26   706.5  873.05 1274.65 2013.31
River Rch & RM=13678,168,42499.06
  342.01  547.08  738.86  913.21 1333.28 2093.32
River Rch & RM=13678,168,42038.59
  348.28   557.2  752.62  930.29 1358.22 2127.25
River Rch & RM=13678,168,41808.35
  349.67  559.45  755.68  934.08 1363.76 2134.75
River Rch & RM=13678,168,41578.11
  442.33   708.8   958.6 1185.81 1731.28 2623.97
River Rch & RM=13678,168,41347.88
  447.18  716.69  969.36 1199.22 1750.86 2649.87
River Rch & RM=13678,168,41117.64
  450.41  721.93  976.53 1208.14 1763.89 2667.08
River Rch & RM=13678,168, 40887.4
  455.55  730.29  987.94 1222.37 1784.66 2694.53
River Rch & RM=13678,168,40657.16
  690.75 1110.71 1506.12  1866.3  2724.8 3886.42
River Rch & RM=13678,168,40426.93
  693.69 1115.49 1512.66 1874.47 2736.72 3901.23
River Rch & RM=13678,168,40193.54
  699.81 1125.47 1526.33 1891.53 2761.64 3932.27
River Rch & RM=13678,168,40041.93
  702.15 1129.28 1531.54 1898.03 2771.13 3944.07
River Rch & RM=13678,168,39879.48
  703.02  1130.7 1533.49 1900.46 2774.68  3948.5
River Rch & RM=13678,168, 39758.5
  704.16 1132.56 1536.05 1903.68 2779.38 3954.39
River Rch & RM=13678,168,39561.91
  831.66 1339.99 1819.74 2257.34 3295.72 4586.08
River Rch & RM=13678,168,39360.99
 1158.56 1872.98 2549.87 3168.61 4626.17 6158.15
River Rch & RM=13678,168,39119.86
  1160.6 1876.33 2554.48  3174.4 4634.62 6168.05
River Rch & RM=13678,168,38878.74
 1160.85 1876.74 2555.06 3175.12 4635.68 6169.28
River Rch & RM=13678,168,38637.61
 1173.56 1897.66 2583.88 3211.28 4688.47 6230.99
River Rch & RM=13678,168,38396.49
 1365.32 2210.94  3013.7 3748.29  5472.5 7126.56
River Rch & RM=13678,168,38163.16
 1366.79 2213.36 3017.05 3752.48 5478.63 7133.57
River Rch & RM=13678,168,38039.37
 1367.77 2214.97 3019.27 3755.28 5482.71 7138.24
River Rch & RM=13678,168, 37871.7
 1379.23 2233.88 3045.37 3788.06 5530.57 7193.04
River Rch & RM=13678,168,37684.35
 1380.43 2235.87 3048.13 3791.53 5535.64 7198.86
River Rch & RM=13678,168,37496.99
 1381.65 2237.88  3050.9 3795.02 5540.72 7204.68
River Rch & RM=13678,168,37476.54
 1382.37 2239.08 3052.56  3797.1 5543.77 7208.17
River Rch & RM=13678,168,37214.07
 1386.68 2246.21 3062.44 3809.55 5561.94  7229.1
River Rch & RM=13678,168,36974.46
 1405.53 2277.35 3105.47 3863.66 5640.94 7319.51
River Rch & RM=13678,168,36734.85
 1436.35 2328.26 3175.83 3952.12  5770.1 7466.93
River Rch & RM=13678,168,36495.24
 1439.66 2333.76 3183.44 3961.71  5784.1 7482.99
River Rch & RM=13678,168,36255.63
 1442.02 2337.68 3188.87 3968.56  5794.1 7494.45
River Rch & RM=13678,168,35885.16
 1446.27 2344.73 3198.64 3980.88 5812.08 7515.06
River Rch & RM=13678,168,35597.87
 1452.27 2354.75 3212.59 3998.51 5837.83 7544.79
River Rch & RM=13678,168, 35415.4
  1465.2 2376.33  3242.6 4036.46 5893.23 7608.67
River Rch & RM=13678,168,35232.93
 1491.83 2420.58 3303.99 4113.92 6006.32 7738.07
River Rch & RM=13678,168,35050.46
 1493.65 2423.63 3308.23 4119.29 6014.16 7747.12
River Rch & RM=13678,168,34689.87
 1547.66 2513.54 3433.09 4276.96 6244.37 8009.98
River Rch & RM=13678,168,34348.32
 1557.81 2530.53 3456.77 4306.94 6288.14 8060.15
River Rch & RM=13678,168,33973.51
 1578.63 2565.41 3505.42 4368.61 6378.17 8163.43
River Rch & RM=13678,168,33695.44
 1623.29  2639.8 3608.75 4499.14 6568.74 8379.44
River Rch & RM=13678,168,33505.77
 1624.15 2641.25  3610.8 4501.74 6572.54 8383.83
River Rch & RM=13678,168,33316.11
 1679.38 2733.76 3739.77 4665.15 6811.12 8655.08
River Rch & RM=13678,168,33126.45
 1680.45 2735.57  3742.3 4668.39 6815.84  8660.5
River Rch & RM=13678,168,32670.45
 1685.17 2743.53 3753.47  4682.6 6836.59 8684.29
River Rch & RM=13678,168,32471.58
  1689.9 2751.52 3764.65 4696.83 6857.37 8708.07
River Rch & RM=13678,168,32272.71
 1703.12 2773.76 3795.76 4736.36 6915.08 8773.85
River Rch & RM=13678,168,31684.53
 1711.88 2788.56 3816.51 4762.77 6953.64 8817.96
River Rch & RM=13678,168,31023.82
 1717.64 2798.29 3830.15 4780.13    6979 8846.96
River Rch & RM=13678,168,30604.89
 2095.15 3434.67  4721.2 5913.34 8633.4710703.36
River Rch & RM=13678,168, 30049.5
 2101.89 3446.04 4737.15 5933.65 8663.1210736.21
River Rch & RM=13678,168,29808.99
  2136.2 3503.84 4818.07 6036.53 8813.3310901.83
River Rch & RM=13678,168,29568.47
  2144.7 3518.22 4838.24 6062.23 8850.8510943.34
River Rch & RM=13678,168,29327.96
 2146.32 3520.96 4842.08 6067.12 8857.9910951.23
River Rch & RM=13678,168,29087.45
 2158.48  3541.5 4870.89 6103.81 8911.5611010.39
River Rch & RM=13678,168,28846.93
 2196.28 3605.27 4960.24  6217.5 9077.5511193.01
River Rch & RM=13678,168,28606.42
  2198.7 3609.35 4965.97  6224.8 9088.2111204.75
River Rch & RM=13678,168, 28365.9
 2209.38 3627.41 4991.29 6257.05 9135.2911256.55
River Rch & RM=13678,168,28125.39
 2218.22 3642.36 5012.27 6283.77  9174.311299.48
River Rch & RM=13678,168,27884.87
 2223.65 3651.52 5025.13 6300.15 9198.2211325.79
River Rch & RM=13678,168, 27791.1
 2225.25 3654.24 5028.94    6305 9205.3111333.59
River Rch & RM=13678,168,27719.59
 2230.27 3662.72 5040.84 6320.17 9227.4411357.92
River Rch & RM=13678,168,27383.07
 2238.11 3675.96 5059.41 6343.82 9261.9811395.84
River Rch & RM=13678,168,27145.26
 2250.25 3696.43 5088.08 6380.29 9315.2211454.09
River Rch & RM=13678,168,26907.45
 2260.47  3713.7 5112.32 6411.15 9360.2811503.51
River Rch & RM=13678,168,26669.65
 2264.67 3720.81 5122.29 6423.85 9378.8211523.84
River Rch & RM=13678,168,26431.84
 2268.09 3726.58 5130.37 6434.14 9393.8511540.28
River Rch & RM=13678,168,26194.03
 2276.75 3741.18 5150.84 6460.18 9431.8711581.83
River Rch & RM=13678,168,25956.23
 2283.37 3752.35  5166.5 6480.13 9460.9811613.68
River Rch & RM=13678,168,25718.42
 2287.79 3759.81 5176.96 6493.43 9480.4111634.89
River Rch & RM=13678,168,25480.61
 2291.19 3765.57 5185.02  6503.7  9495.411651.27
River Rch & RM=13678,168,25242.81
 2295.97 3773.64 5196.36 6518.15 9516.4911674.38
River Rch & RM=13678,168,   25005
 2298.77 3778.38    5203 6526.59 9528.8311687.85
River Rch & RM=13678,168,24767.19
 2311.82 3800.39 5233.85 6565.84 9586.1311750.33
River Rch & RM=13678,168,24529.39
 2577.73    4243  5848.9 7342.4910720.0412952.75
River Rch & RM=13678,168,24217.39
 2602.18 4284.36 5906.97  7416.510828.0913068.98
River Rch & RM=13678,168,23939.66
 2604.91 4288.97 5913.43 7424.73 10840.113081.86
River Rch & RM=13678,168,23441.97
    2609 4295.88 5923.12 7437.0710858.1213101.19
River Rch & RM=13678,168,22607.41
 2622.37  4318.5 5954.87 7477.5210917.1813164.61
River Rch & RM=13678,168,22128.41
 2631.15 4333.31 5975.64 7503.9510955.77 13205.9
River Rch & RM=13678,168, 21886.8
 2745.74 4523.76 6240.06 7837.5511442.8213713.83
River Rch & RM=13678,168,21645.19
 2747.87 4527.35  6245.1 7843.9611452.1813723.77
River Rch & RM=13678,168,21161.97
  2753.7 4537.17 6258.86 7861.4511477.7213750.86
River Rch & RM=13678,168,20920.36
 2755.05 4539.46 6262.06 7865.5211483.6613757.18
River Rch & RM=13678,168,20678.75
 2780.62 4582.84 6323.08 7943.4211597.39 13878.8
River Rch & RM=13678,168,20437.15
  2783.3 4587.37 6329.44 7951.5211609.2213891.39
River Rch & RM=13678,168,20195.54
 2798.11 4612.46 6364.72 7996.5111674.9113961.45
River Rch & RM=13678,168,19953.93
 2847.42 4695.27 6480.46  8143.411889.3714186.85
River Rch & RM=13678,168,19712.32
 2850.26 4700.08 6487.22 8152.0211901.9514200.22
River Rch & RM=13678,168,19470.71
 2870.65 4734.46 6535.39 8213.29 11991.414294.58
River Rch & RM=13678,168, 19229.1
 2880.99    4752 6560.06 8244.7812037.3814343.44
River Rch & RM=13678,168,18987.49
 2884.38 4757.75 6568.14 8255.0812052.4214359.42
River Rch & RM=13678,168,18745.89
 2888.52 4764.76    6578 8267.67 12070.814378.93
River Rch & RM=13678,168,18504.28
 2901.22 4786.34 6608.38 8306.4712127.45 14439.2
River Rch & RM=13678,168,18262.67
 2905.73 4793.99 6619.13 8320.1912147.4814460.44
River Rch & RM=13678,168,18021.06
 2906.86  4795.9 6621.82 8323.6212152.4914465.75
River Rch & RM=13678,168,17779.45
 3199.38 5286.29 7306.54 9191.7313419.9215778.89
River Rch & RM=13678,168,17537.84
 3209.66 5303.73 7331.08 9223.0613465.6615826.75
River Rch & RM=13678,168,17296.23
 3212.22 5308.07  7337.2 9230.8713477.0715838.71
River Rch & RM=13678,168,17054.63
 3247.36 5367.98 7421.74 9339.0713635.0516004.87
River Rch & RM=13678,168,16813.02
  3258.8 5387.52 7449.35 9374.4413686.6916059.26
River Rch & RM=13678,168,16571.41
 3261.47 5392.09 7455.81 9382.7213698.77   16072
River Rch & RM=13678,168, 16329.8
 3265.56 5399.08  7465.7  9395.413717.2816091.52
River Rch & RM=13678,168,16088.19
 3307.16 5470.54 7567.02 9525.6213907.41   16293
River Rch & RM=13678,168,15846.58
 3309.99 5475.39 7573.88 9534.4213920.2516306.51
River Rch & RM=13678,168,15758.51
 3312.97 5480.49 7581.11 9543.7113933.8216320.85
River Rch & RM=13678,168,15659.74
 3313.49  5481.4 7582.39 9545.3513936.2216323.38
River Rch & RM=13678,168,15423.01
    3317 5487.42 7590.92  9556.3 13952.216340.26
River Rch & RM=13678,168,15217.39
 3331.38 5512.25 7626.24 9601.8314018.6716411.05
River Rch & RM=13678,168,15011.77
 3332.93 5514.92 7630.04 9606.71 14025.816418.63
River Rch & RM=13678,168,14880.29
 3335.67 5519.65 7636.76 9615.3814038.46 16432.1
River Rch & RM=13678,168,14726.53
 3339.45 5526.17 7646.03 9627.3114055.8816450.61
River Rch & RM=13678,168,14388.62
 3340.31 5527.65 7648.13 9630.0314059.8416454.82
River Rch & RM=13678,168,14257.94
 3341.69 5530.02 7651.51 9634.3714066.1816461.55
River Rch & RM=13678,168,13904.66
 3343.75 5533.58 7656.56 9640.8814075.6816471.64
River Rch & RM=13678,168,13680.25
 3401.76 5632.81  7796.9 9820.8314338.4216747.38
River Rch & RM=13678,168,13455.83
 3421.27 5666.53  7844.9 9882.7314428.7816843.34
River Rch & RM=13678,168,13231.42
 3424.52 5672.14 7852.86 9892.9814443.7516859.17
River Rch & RM=13678,168,   13007
 3432.07 5685.14 7871.33 9916.7514478.4516895.82
River Rch & RM=13678,168,12782.59
 3469.73 5749.93 7963.2810035.0214651.1317077.75
River Rch & RM=13678,168,12558.17
 3471.56  5753.1 7967.8110040.8814659.6817086.87
River Rch & RM=13678,168,12333.76
 3474.56 5758.31 7975.2410050.48 14673.717101.79
River Rch & RM=13678,168,12096.95
 3490.87 5786.61 8015.6310102.6814749.9117182.91
River Rch & RM=13678,168,11860.15
 3493.84 5791.79 8023.0210112.2414763.8817197.79
River Rch & RM=13678,168,11623.34
 3495.33 5794.38 8026.7210117.0314770.8617205.23
River Rch & RM=13678,168,11386.53
 3495.67 5794.95 8027.5410118.0914772.4117206.88
River Rch & RM=13678,168,11097.25
 3501.11 5804.42 8041.08 10135.614797.9817234.15
River Rch & RM=13678,168,10676.12
 3502.76  5807.3 8045.1810140.9114805.7317242.41
River Rch & RM=13678,168,10439.31
 3539.91 5871.96 8137.6210260.5614980.4217428.67
River Rch & RM=13678,168, 10202.5
 3541.54  5874.8 8141.6910265.8314988.1217436.89
River Rch & RM=13678,168,9965.696
 7308.1412243.8117089.5521664.5531630.2433487.26
River Rch & RM=13678,168,9593.696
 7516.9312605.7217606.1622331.8332604.4734412.61
River Rch & RM=13678,168,9350.609
 7519.4212610.0617612.4122339.9232616.2934423.94
River Rch & RM=13678,168,9107.521
 7520.3812611.7517614.8322343.0732620.8934428.34
River Rch & RM=13678,168,8864.433
 7522.3212615.1417619.6822349.3732630.0834437.16
River Rch & RM=13678,168,8621.346
 7527.5512624.2917632.8322366.44   3265534461.07
River Rch & RM=13678,168,8378.258
 7542.2212649.9217669.5922414.1332724.6334527.74
River Rch & RM=13678,168, 8135.17
 7548.8312661.48 17686.222435.6932756.1134557.92
River Rch & RM=13678,168,7892.083
 7590.1912733.5917789.5122569.5632951.5534744.39
River Rch & RM=13678,168,7648.995
 7614.7312776.4317850.9222649.1733067.7934855.34
River Rch & RM=13678,168,7405.907
 7617.4912781.2417857.8222658.1333080.8834867.87
River Rch & RM=13678,168, 7162.82
 7631.9112806.4817894.0622705.1733149.5534933.61
River Rch & RM=13678,168,6919.732
 7633.98 12810.117899.24 22711.933159.37   34943
River Rch & RM=13678,168,6676.644
 7639.76 12820.217913.7522730.7233186.8634969.28
River Rch & RM=13678,168,6433.557
  7643.212826.2217922.3822741.9233203.2134984.91
River Rch & RM=13678,168,6190.469
 7645.5512830.3217928.2622749.5533214.3434995.55
River Rch & RM=13678,168,5947.381
 7646.3812831.7717930.3422752.2433218.28 34999.3
River Rch & RM=13678,168,5704.294
 7654.9712846.7517951.82 22780.133258.9435038.07
River Rch & RM=13678,168,5461.206
 7660.7912856.9117966.3822798.9633286.4835064.32
River Rch & RM=13678,168,5287.051
12193.9720307.6528247.14 35666.952073.6850896.09
River Rch & RM=13678,168,5085.841
12196.3620311.8428253.1735674.7352085.1150906.35
River Rch & RM=13678,168,4884.631
12212.5120340.13 28293.835727.4652162.0950975.43
River Rch & RM=13678,168, 4683.42
12214.0120342.76 28297.635732.3952169.2950981.91
River Rch & RM=13678,168, 4482.21
12217.5420348.9328306.4735743.9152186.1150997.01
River Rch & RM=13678,168,    4281
12221.0920355.1428315.3835755.4652202.9851012.12
Boundary for River Rch & Prof#=13678,168,1
Up Type= 0
Dn Type= 2
Boundary for River Rch & Prof#=13678,168,2
Up Type= 0
Dn Type= 2
Boundary for River Rch & Prof#=13678,168,2
Up Type= 0
Dn Type= 2
Boundary for River Rch & Prof#=13678,168,2
Up Type= 0
Dn Type= 2
Boundary for River Rch & Prof#=13678,168,2
Up Type= 0
Dn Type= 2
Boundary for River Rch & Prof#=13678,168,2
Up Type= 0
Dn Type= 2

--- 13678_ras.g01 (geometry) ---

Geom Title=13678
Program Version=4.10

River Reach=13678,168
Reach XY= 30
 667269.84030953  833362.1505225666040.995443434832926.092190564
664706.830255359833372.187060833664628.707441509834732.212516531
663555.879814416835783.716693684 662928.27564773835551.945860326
 661393.45578602 836127.13491641 661147.61647588837053.629232511
660630.532592177836985.973638102660460.467207342838623.534909233
661845.013724536840148.486782968664187.605378032841711.288814738
664423.870290101841239.279746234665216.470092148841671.737526983
664988.171481043842105.765304789667364.868998826 842968.04348053
667811.480479896845027.372095853667627.338894546845975.341758236
  667326.7131477845726.425026968666716.950379401846275.012244642
666705.879814386848037.188915879667294.942314386848296.043082535
 667517.83415404850348.152488992668916.817314416851032.501415879
668880.879814386851565.313915864669410.115908116851876.211230323
 669249.08743456 852852.98313202669917.210170835854359.961963147
669384.854061544855007.412630752669772.958987653856452.600586087

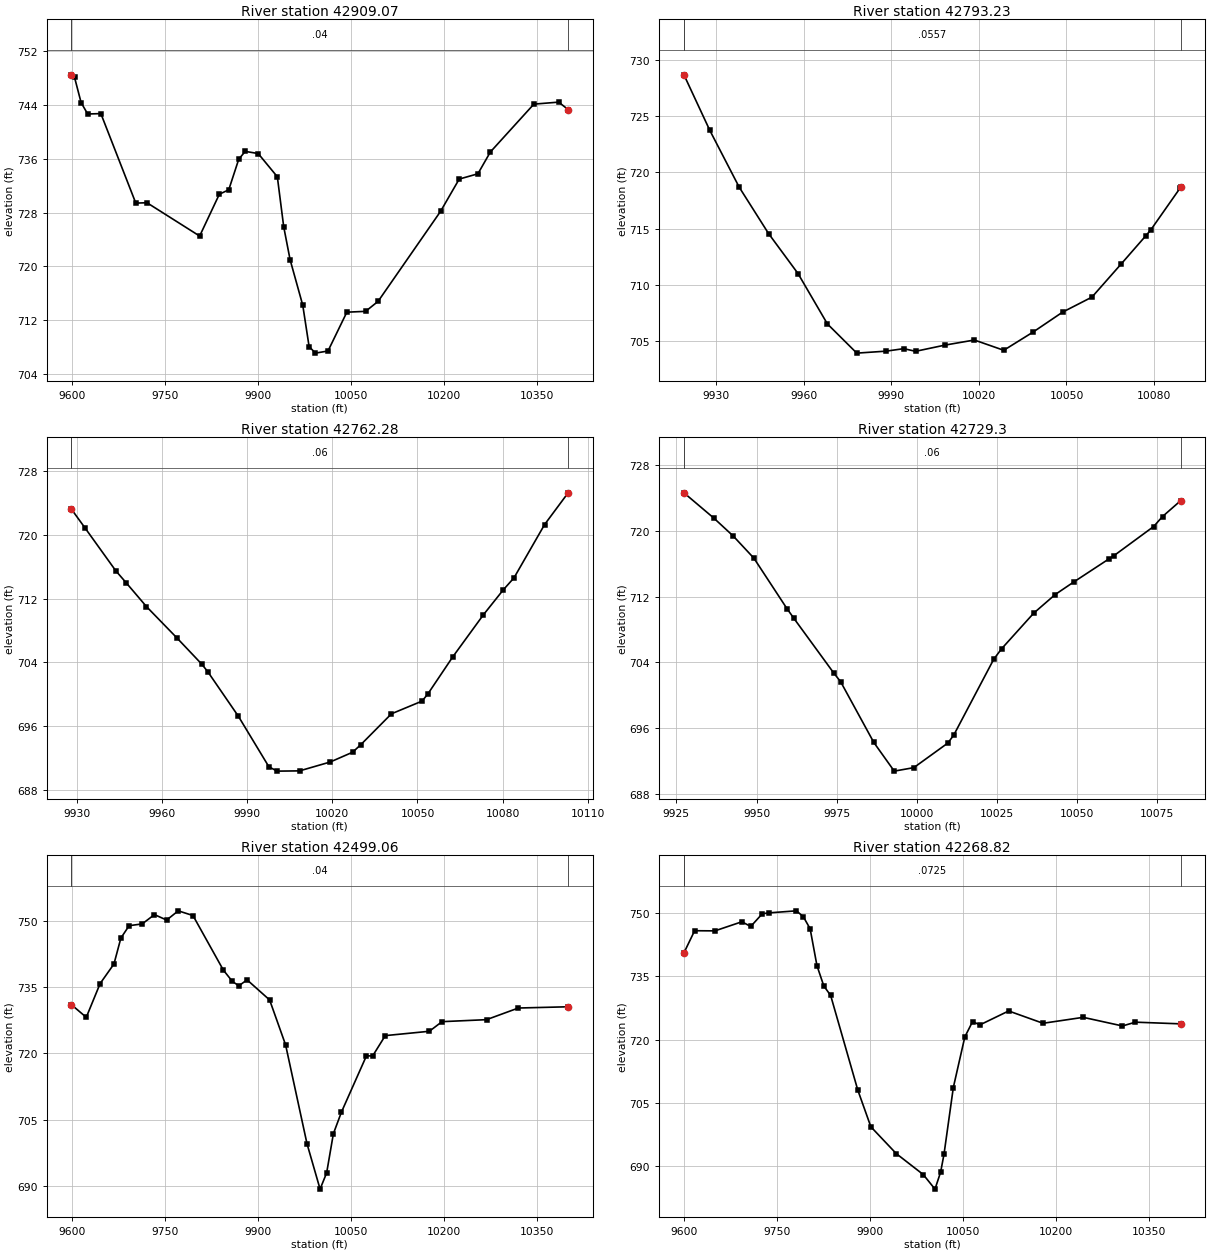
Type RM Length L Ch R = 1 ,42909.07,115.835900,115.835900,115.835900
XS GIS Cut Line= 6
667390.341653432832980.411891078667311.797639683 833197.33335378
667275.654156961833328.149625739667261.213905004833406.896841668
667245.216110747833526.098426498667223.427592144833760.195355635
#Sta/Elev= 30
9599.026748.46819603.906748.10179614.541744.33869625.176 742.6449646.447742.7052
9702.833729.39939720.894729.45589805.977724.50369837.747  730.729852.955731.3801
9869.121735.93179879.579737.08979900.495736.76639931.405733.31569941.693725.8888
 9951.98721.00149972.496714.20419982.696708.08269992.897707.100810013.22707.4182
10043.65713.187110073.93713.310810094.11714.797110194.92728.164310225.09732.9727
10255.27733.756910275.39736.996410345.63744.111510385.74744.410810400.98743.3045
#Mann= 3 , 0 , 0
9599.026    0.04       09599.026    0.04       010400.98    0.04       0
#XS Ineff= 2 , 0
       0                               0
Bank Sta=9599.026,10400.98
Exp/Cntr=0.3,0.1

Type RM Length L Ch R = 1 ,42793.23,30.947400,30.947400,30.947400
XS GIS Cut Line= 2
667164.073041558833266.193390921667143.572797626833435.165099069
#Sta/Elev= 21
9918.901 728.6539927.772723.71729937.845718.67499947.919714.55439957.992711.0118
9968.065706.53949978.139703.94739988.212704.12349994.233 704.3449998.285704.1093
10008.36704.659910018.43 705.11110028.51   704.210038.58705.819910048.65707.5829
10058.73708.9199 10068.8711.876910077.26714.385610078.87714.877410088.95718.6032
10089.11718.6822
#Mann= 3 , 0 , 0
9918.901  0.0557       09918.901  0.0557       010089.11  0.0557       0
#XS Ineff= 2 , 0
       0                               0
Bank Sta=9918.901,10089.11
Exp/Cntr=0.3,0.1

Type RM Length L Ch R = 1 ,42762.28,32.984900,32.984900,32.984900
XS GIS Cut Line= 2
667152.269870788833270.541927546667086.420602173833432.680220991
#Sta/Elev= 24
9928.089723.20829932.901720.84479943.694715.49749947.409713.97319954.487711.0151
9965.281707.06419973.985703.79419976.074702.86369986.867697.2733 9997.66690.9207
10000.56690.382710008.45690.414310019.25691.526810027.14692.751210030.04693.7007
10040.83697.568810051.63 699.16310053.71700.084210062.42704.698210073.21709.9708
10080.29713.128710084.01714.6098 10094.8721.295910103.09725.2689
#Mann= 3 , 0 , 0
9928.089    0.06       09928.089    0.06       010103.09    0.06       0
#XS Ineff= 2 , 0
       0                               0
Bank Sta=9928.089,10103.09
Exp/Cntr=0.3,0.1

Type RM Length L Ch R = 1 , 42729.3,230.236900,230.236900,230.236900
XS GIS Cut Line= 2
667144.194017112833257.496317729667051.632309318 833381.74022077
#Sta/Elev= 23
9927.362 724.6389936.719721.54649942.751719.37029949.189716.67319959.489710.5353
9961.659709.34539974.129702.66689976.227701.63489986.599694.22099992.966690.7322
9999.069691.1571 10009.7694.156510011.54695.129610024.01 704.36910026.44705.6338
10036.48709.981310043.18 712.24810048.95 713.77110059.92716.582710061.42716.9591
10073.89720.534310076.66721.751310082.29 723.674
#Mann= 3 , 0 , 0
9927.362    0.06       09927.362    0.06       010082.29    0.06       0
#XS Ineff= 2 , 0
       0                               0
Bank Sta=9927.362,10082.29
Exp/Cntr=0.3,0.1

Type RM Length L Ch R = 1 ,42499.06,230.236900,230.236900,230.236900
XS GIS Cut Line= 6
667167.050017277832893.650604543667098.769008363833023.339652632
667025.815578799 833128.83888999666971.626836229833180.379640053
666891.126707018833222.339266362666814.835334249 833573.35648709
#Sta/Elev= 30
9599.169731.05239623.021728.19919645.365735.86129667.709740.30199678.881746.1856
9692.208 748.9929713.277749.39419733.054751.50299752.777750.27129771.488752.3628
9795.227751.29659844.293738.91259858.878736.33989869.334735.35219882.549736.7059
9918.985732.13659944.759721.94339979.328699.507610000.41689.217710011.02692.9136
10021.89 701.79610034.98706.726210075.18719.440310085.34719.454610105.66724.0486
10176.77725.034210197.27 727.215 10269.1727.6688 10320.4730.3102 10400.8 730.591
#Mann= 3 , 0 , 0
9599.169    0.04       09599.169    0.04       0 10400.8    0.04       0
#XS Ineff= 2 , 0
       0                               0
Bank Sta=9599.169,10400.8
Exp/Cntr=0.3,0.1

Type RM Length L Ch R = 1 ,42268.82,230.237000,230.237000,230.237000
XS GIS Cut Line= 6
666934.215810359832859.185559461666820.916482664833108.962243639
666796.722675513833203.585149852666733.525768732833278.863635647
666679.621130171833380.904381343666612.345255622833585.363076793
#Sta/Elev= 30
9599.153740.5664 9616.39745.81139649.088745.77249692.685747.93269706.943 746.814
9725.614749.83299736.649750.04479780.792750.52589791.828749.13439802.863746.2747
9813.899737.51819824.935732.7141 9835.97730.46659879.813708.02239900.888699.3272
9941.962692.95869985.454688.002310004.44684.544710013.58688.6105   10019692.8349
10034.03708.636510052.59720.632410065.07724.248810077.04723.490910123.36726.7844
10178.86723.865110243.71725.273810307.09 723.22810327.97724.128610400.91723.7294
#Mann= 3 , 0 , 0
9599.153  0.0725       09599.153  0.0725       010400.91  0.0725       0
#XS Ineff= 2 , 0
       0                               0
Bank Sta=9599.153,10400.91
Exp/Cntr=0.3,0.1

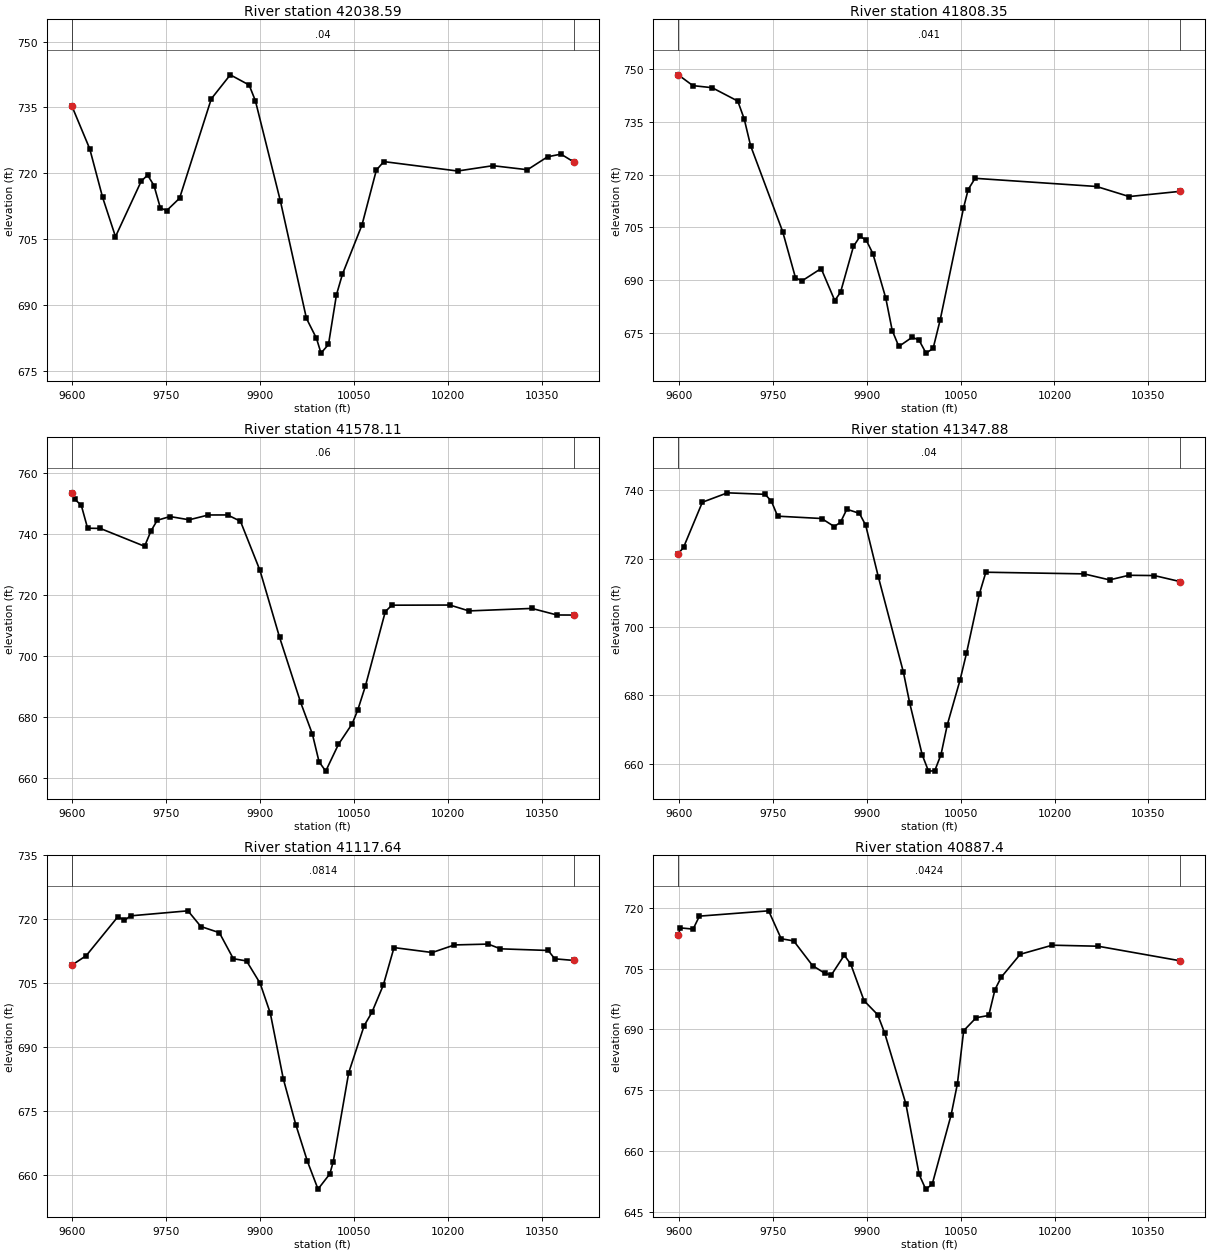
Type RM Length L Ch R = 1 ,42038.59,230.236900,230.236900,230.236900
XS GIS Cut Line= 6
 666709.27301312832697.032674401666656.481024171832984.109867271
666661.068668172 833048.52812066 666693.84751184833129.084004121
666592.262631096833302.700819521666532.210705408833444.173319468
#Sta/Elev= 30
9599.162735.37269627.881725.55329648.419 714.4929668.956705.54499710.001718.1783
9720.213719.58489730.426 717.1999740.638712.0639 9750.85711.50879771.274714.3091
9821.936736.97269852.232742.43669882.325740.11679892.353736.50739932.388713.5759
9973.816686.91779989.846682.36849997.078 678.99810009.02680.970310021.74692.2904
 10031.2696.945410062.47708.192810085.47720.7273 10097.4722.655710215.21720.5115
10271.58721.723910326.71720.802410358.83723.754510380.24724.357310400.76722.5669
#Mann= 3 , 0 , 0
9599.162    0.04       09599.162    0.04       010400.76    0.04       0
#XS Ineff= 2 , 0
       0                               0
Bank Sta=9599.162,10400.76
Exp/Cntr=0.3,0.1

Type RM Length L Ch R = 1 ,41808.35,230.236900,230.236900,230.236900
XS GIS Cut Line= 6
 666569.90648305832682.175609949666491.266424031833019.114447269
666423.189088849 833164.85528771666384.808320118833256.881338703
666355.173460005833347.179275065666333.062680801833444.764783055
#Sta/Elev= 30
9599.054748.40589622.431745.33539653.158744.74959694.126740.94639704.368735.8946
9714.611728.26519765.821703.85119786.306690.71359796.548   689.89827.323693.3326
9849.035684.23289858.283686.57919878.923699.63989889.507702.49459899.563701.3233
9909.883697.59559930.523  684.939940.842675.69859951.377671.17639972.745673.7963
9983.599672.9819 9994.83669.278310006.11670.5994 10017.4678.709310054.65710.5089
10062.11715.778610073.15718.982310267.23716.657810319.23713.795310400.96715.2817
#Mann= 3 , 0 , 0
9599.054   0.041       09599.054   0.041       010400.96   0.041       0
#XS Ineff= 2 , 0
       0                               0
Bank Sta=9599.054,10400.96
Exp/Cntr=0.3,0.1

Type RM Length L Ch R = 1 ,41578.11,230.236900,230.236900,230.236900
XS GIS Cut Line= 6
666359.608202078832559.993855849666314.444451496832816.267690911
666238.601282014833050.924358218 666218.35023298833129.427471455
666205.537372787833214.859823289666199.123714592833342.018138815
#Sta/Elev= 30
9599.062753.60929604.124 751.4349614.237749.5283 9624.35741.97699644.576741.9106
9715.366736.03889725.479 741.0429735.592744.59049755.929745.81569786.578744.7445
9817.227 746.3289847.876746.33919868.465744.27229899.649728.10429930.832706.1978
9964.478684.79199983.413 674.2849994.008665.209810004.64662.142210025.06670.9674
10046.95677.716710055.76 682.187 10068.1690.143810099.83714.575510110.31716.6799
10202.99716.726510233.41714.798810333.89715.617210373.91713.461110400.94713.4389
#Mann= 3 , 0 , 0
9599.062    0.06       09599.062    0.06       010400.94    0.06       0
#XS Ineff= 2 , 0
       0                               0
Bank Sta=9599.062,10400.94
Exp/Cntr=0.3,0.1

Type RM Length L Ch R = 1 ,41347.88,230.236900,230.236900,230.236900
XS GIS Cut Line= 6
666014.568198612832526.574734933666026.298307545832703.996198953
666043.854349997832882.908488783666046.752546625832964.022492421
666105.211056457833166.599002911666133.256484525833316.074765066
#Sta/Elev= 30
9599.034721.40639607.478723.25569637.543736.46929677.631739.22349737.762738.7848
9747.784736.78029757.805732.39249828.092731.70799848.188729.35899858.236730.6169
9868.284734.4211 9888.38733.22299898.428729.74129918.524714.70519958.707686.7087
9968.711677.72389988.718662.55889998.722657.804210008.72657.901510018.73662.6682
10028.77671.366310049.09684.423810059.34692.221410079.85709.555510090.36715.9956
10247.14715.511910288.04713.7461 10318.7715.097410359.32715.020310400.92713.2426
#Mann= 3 , 0 , 0
9599.034    0.04       09599.034    0.04       010400.92    0.04       0
#XS Ineff= 2 , 0
       0                               0
Bank Sta=9599.034,10400.92
Exp/Cntr=0.3,0.1

Type RM Length L Ch R = 1 ,41117.64,230.237000,230.237000,230.237000
XS GIS Cut Line= 6
665752.450257635832682.271396305665782.401210893832855.222954158
665811.542870259832960.086784262665847.635696179833029.822587129
665983.007932955833232.070390213666051.983299603833414.320284236
#Sta/Elev= 30
9599.077709.23099622.144711.47329672.888720.63889683.037719.76769693.186720.8214
 9784.65721.99539805.203718.31659834.775716.86549857.124710.75259878.184710.2329
9899.906704.9853 9916.22697.93529936.892682.58199956.889671.80549975.485663.1821
 9992.37656.677510011.25660.2535 10016.7663.137210041.37683.991910066.04695.0361
10078.38698.150610096.67704.574210113.75 713.368 10174.8712.209210210.33713.9907
10264.12714.188610283.78 713.07710359.97712.693610370.43 710.73310400.96710.3486
#Mann= 3 , 0 , 0
9599.077  0.0814       09599.077  0.0814       010400.96  0.0814       0
#XS Ineff= 2 , 0
       0                               0
Bank Sta=9599.077,10400.96
Exp/Cntr=0.3,0.1

Type RM Length L Ch R = 1 , 40887.4,230.236900,230.236900,230.236900
XS GIS Cut Line= 6
665707.623438556832741.461427025665720.952470514 832965.70229519
665663.396997098833129.196319149665656.675339691833221.044319961
665677.732622598833344.653874183665738.070890237833518.695118268
#Sta/Elev= 30
9599.133713.30939602.701714.99729622.862714.69479632.943717.88669743.497719.1953
9763.504  712.339783.511711.7918 9813.57705.72479833.721703.77349843.859703.4668
9864.301708.28079874.703706.04759895.839697.07919917.666 693.6249928.906689.0573
9962.625671.70349983.813654.3165 9994.31650.712910004.62651.867710034.88668.9664
10044.92676.626710054.92689.697610074.92692.897410094.94693.442110104.96699.8319
10114.98702.880310145.25 708.50510196.45 710.739 10269.5710.486610400.88 706.895
#Mann= 3 , 0 , 0
9599.133  0.0424       09599.133  0.0424       010400.88  0.0424       0
#XS Ineff= 2 , 0
       0                               0
Bank Sta=9599.133,10400.88
Exp/Cntr=0.3,0.1

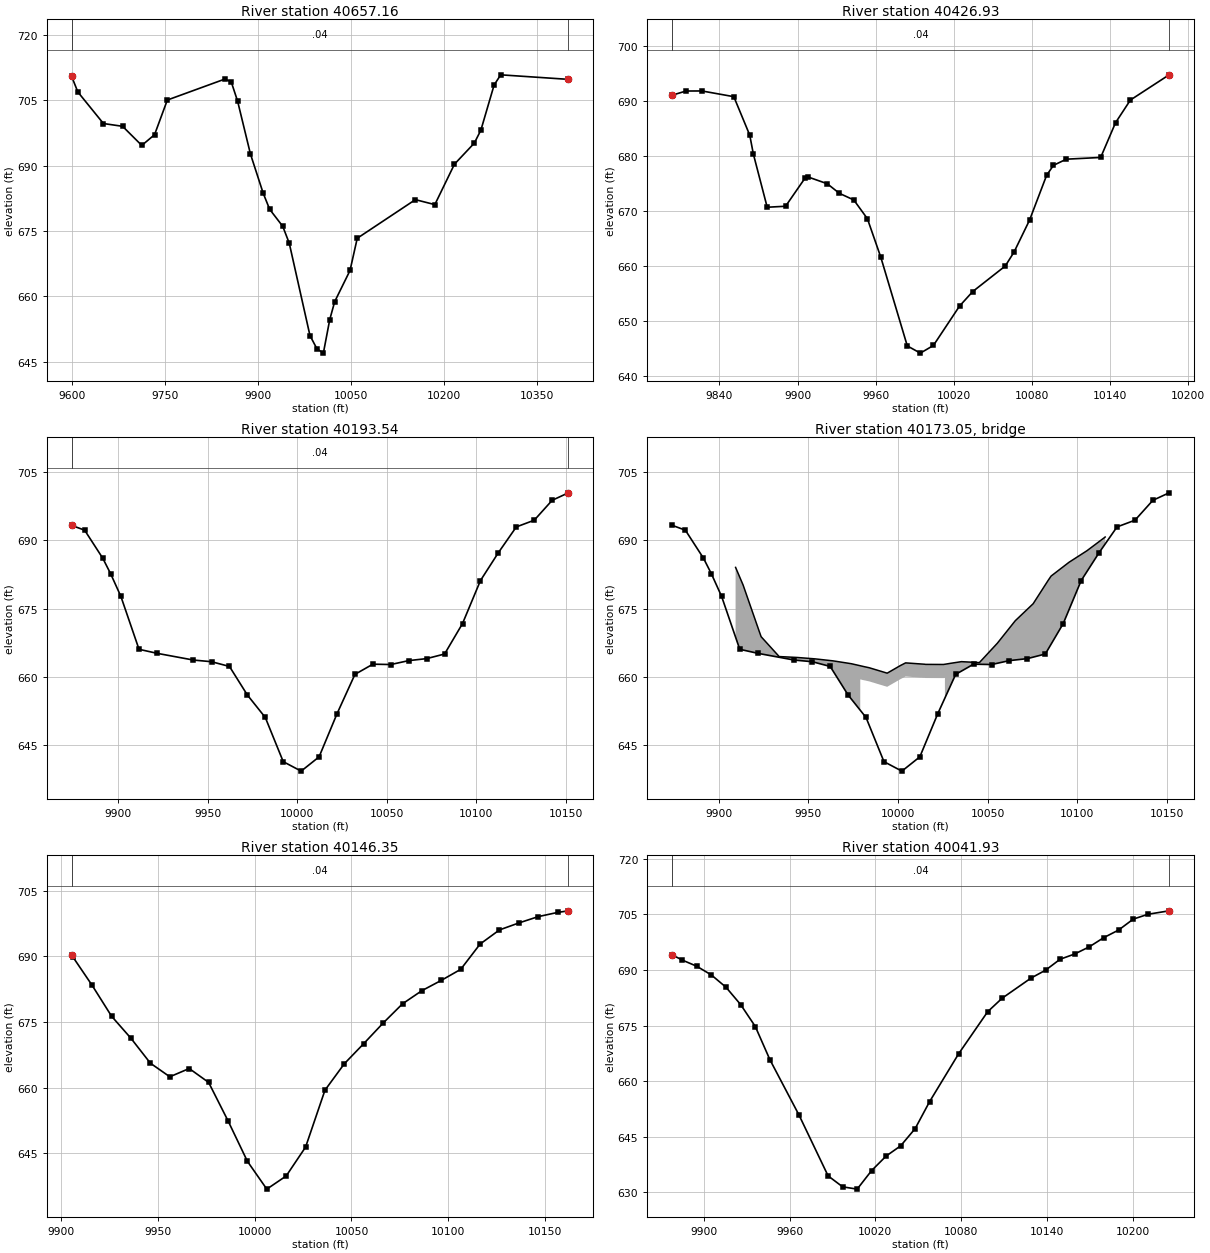
Type RM Length L Ch R = 1 ,40657.16,230.236900,230.236900,230.236900
XS GIS Cut Line= 6
665444.477512069832665.058343359665520.635884643832968.068266761
665558.037544311833065.771615615665525.469111262833142.998485694
665527.423463317833195.369798012665610.781063183833427.279791527
#Sta/Elev= 30
9599.071710.58489609.322706.93029650.566699.68849681.499699.05029712.432694.6602
9733.054697.11969753.677705.08639846.476709.90059856.787709.26279867.098704.8125
 9887.72692.72599908.342683.68349918.811679.97959939.888 676.0849950.426672.1947
9983.831650.98429995.032647.952110005.45646.947510015.74654.647610023.72658.7728
10048.47665.935610060.11673.331310153.91682.202410185.31681.064210216.98690.3527
10248.98695.185310259.65698.183810280.99708.556610291.66710.876710400.78709.8353
#Mann= 3 , 0 , 0
9599.071    0.04       09599.071    0.04       010400.78    0.04       0
#XS Ineff= 2 , 0
       0                               0
Bank Sta=9599.071,10400.78
Exp/Cntr=0.3,0.1

Type RM Length L Ch R = 1 ,40426.93,233.387000,233.387000,233.387000
XS GIS Cut Line= 6
665258.826603631833076.401041544665307.411305811833140.936621001
665340.677109309833167.480191827665445.015853268833187.292898251
665486.492912087833205.005487489 665544.50843241833291.717345711
#Sta/Elev= 30
 9803.76691.13099814.292691.88769826.541691.90039851.039690.85849863.288683.8438
9866.033680.42329876.673670.72679890.779670.90489905.886676.08729908.107676.2317
9922.784675.00649932.087 673.261 9943.17672.05159953.613668.64019963.919661.6115
9984.242645.47599994.268644.1615 10004.3645.558810024.39652.737610034.44 655.363
10059.47660.024410066.21662.564810078.14668.391910091.23676.545110096.47678.3549
10106.36679.475710132.73679.792810144.14686.113910155.56690.249810185.27 694.837
#Mann= 3 , 0 , 0
 9803.76    0.04       0 9803.76    0.04       010185.27    0.04       0
#XS Ineff= 2 , 0
       0                               0
Bank Sta=9803.76,10185.27
Exp/Cntr=0.3,0.1

Type RM Length L Ch R = 1 ,40193.54,47.188000,47.188000,47.188000
XS GIS Cut Line= 4
665231.717008173833137.755835101665243.639038563833216.239066064
665241.057420731833299.883483469665236.905476093833414.041751996
#Sta/Elev= 29
9874.053 693.321 9881.38692.26219891.495 686.0969895.913682.6624 9901.61677.6982
9911.725666.07679921.839665.18869942.069 663.7129952.183663.34759962.202662.3051
9972.207656.02349982.211651.08339992.216641.375810002.22639.294110012.23642.4342
10022.23651.906810032.24660.565210042.24662.803910052.25662.725910062.25663.5865
10072.26664.026710082.27665.041410092.27671.732610102.28681.184710112.29687.3184
10122.29692.9768 10132.3694.450610142.31698.829910151.35700.4718
#Mann= 3 , 0 , 0
9874.053    0.04       09874.053    0.04       010151.35    0.04       0
#XS Ineff= 2 , 0
       0                               0
Bank Sta=9874.053,10151.35
Exp/Cntr=0.3,0.1

Type RM Length L Ch R = 3 ,40173.05,,,
BEGIN DESCRIPTION:
END DESCRIPTION:
Bridge Culvert--1,0,-1,-1, 0
Deck Dist Width WeirC Skew NumUp NumDn MinLoCord MaxHiCord MaxSubmerge Is_Ogee
10.798750,25.590500,2.6,0, 34, 34, , , 0.95, 0, 0,0,,
 9909.41 9913.61 9922.66 9923.67 9933.73 9943.79 9953.85 9963.90 9973.96 9978.99
 9978.99 9980.38 9984.00 9994.0110001.4610004.3010014.9910015.3910025.4310026.23
10026.2310029.6410035.4510044.2410045.4610055.4710065.4810075.4910083.8910085.50
10095.5110105.5210115.5310115.66
  684.08  680.20  669.96  668.84  664.48  664.28  663.97  663.53  662.91  662.46
  662.46  662.33  662.02  660.83  662.52  663.09  662.79  662.76  662.74  662.79
  662.79  663.01  663.36  663.18  663.15  667.40  672.35  676.10  681.25  682.18
  685.21  687.75  690.71  690.76
 -315.92 -319.80 -330.04 -331.16 -335.52 -335.72 -336.03 -336.47 -337.09 -337.54
  659.46  659.33  659.02  657.83  659.52  660.09  659.79  659.76  659.74  659.79
 -337.21 -336.99 -336.64 -336.82 -336.85 -332.60 -327.65 -323.90 -318.75 -317.82
 -314.79 -312.25 -309.29 -309.24
 9909.41 9913.61 9922.66 9923.67 9933.73 9943.79 9953.85 9963.90 9973.96 9980.38
 9984.00 9986.76 9986.76 9994.0110001.4610004.3010014.9910015.3910025.4310029.64
10034.0110034.0110035.4510044.2410045.4610055.4710065.4810075.4910083.8910085.50
10095.5110105.5210115.5310115.66
  684.08  680.20  669.96  668.84  664.48  664.28  663.97  663.53  662.91  662.33
  662.02  661.69  661.69  660.83  662.52  663.09  662.79  662.76  662.74  663.01
  663.27  663.27  663.36  663.18  663.15  667.40  672.35  676.10  681.25  682.18
  685.21  687.75  690.71  690.76
 -315.92 -319.80 -330.04 -331.16 -335.52 -335.72 -336.03 -336.47 -337.09 -337.67
 -337.98 -338.31  658.69  657.83  659.52  660.09  659.79  659.76  659.74  660.01
  660.27 -336.73 -336.64 -336.82 -336.85 -332.60 -327.65 -323.90 -318.75 -317.82
 -314.79 -312.25 -309.29 -309.24
BR Coef=-1 , 0 , 0 ,, 0 ,,,0.8,0,1,0,
WSPro=,,,, 1 ,,,, 0 ,,,, 0 ,,,,-1 ,-1 ,-1 , 0 , 0 , 0 , 0 , 0
BC Design=,, 0 ,, 0 ,,,,,,

Type RM Length L Ch R = 1 ,40146.35,104.425000,104.425000,104.425000
XS GIS Cut Line= 4
665192.154940248833164.346733227665195.397732705833236.336725652
665194.749174207833307.678159595665193.452057272 833420.52733691
#Sta/Elev= 28
9905.613690.24569906.267689.92879916.277683.37819926.287676.32289936.297671.2638
9946.307665.57239956.318662.46539966.328664.35649976.338661.1764 9986.34 652.385
 9996.34643.111810006.34636.749810016.34 639.76110026.34 646.37210036.34659.3968
10046.34665.458410056.34670.056210066.34674.762610076.34679.169310086.34682.1797
10096.35684.535210106.35687.058910116.35692.845910126.35696.084210136.35697.6776
10146.35699.126510156.35700.086710161.88700.4519
#Mann= 3 , 0 , 0
9905.613    0.04       09905.613    0.04       010161.88    0.04       0
#XS Ineff= 2 , 0
       0                               0
Bank Sta=9905.613,10161.88
Exp/Cntr=0.3,0.1

Type RM Length L Ch R = 1 ,40041.93,162.446000,162.446000,162.446000
XS GIS Cut Line= 6
665066.290030651 833138.39493927665069.496494259833150.205629615
665081.415756508833204.846405746665091.418122164 833258.81905754
665119.026049863833425.813221946665132.666492339833479.242899347
#Sta/Elev= 30
9877.944694.10689884.789692.7285 9895.09691.03219905.325688.6788 9915.56685.3602
9925.795680.6817 9936.03674.77239946.265665.79439966.605  650.879986.946634.4548
9997.116631.500410007.26630.8829 10017.4635.901310027.54639.815510037.67642.5661
10047.81647.214510057.94654.512910078.21 667.40510098.49678.746410108.62682.4013
10128.89687.854910139.03689.973610149.17692.9222 10159.3694.329910169.44696.2448
10179.74698.761110190.06700.797610200.38703.7632 10210.7705.0691 10225.4 705.991
#Mann= 3 , 0 , 0
9877.944    0.04       09877.944    0.04       0 10225.4    0.04       0
#XS Ineff= 2 , 0
       0                               0
Bank Sta=9877.944,10225.4
Exp/Cntr=0.3,0.1

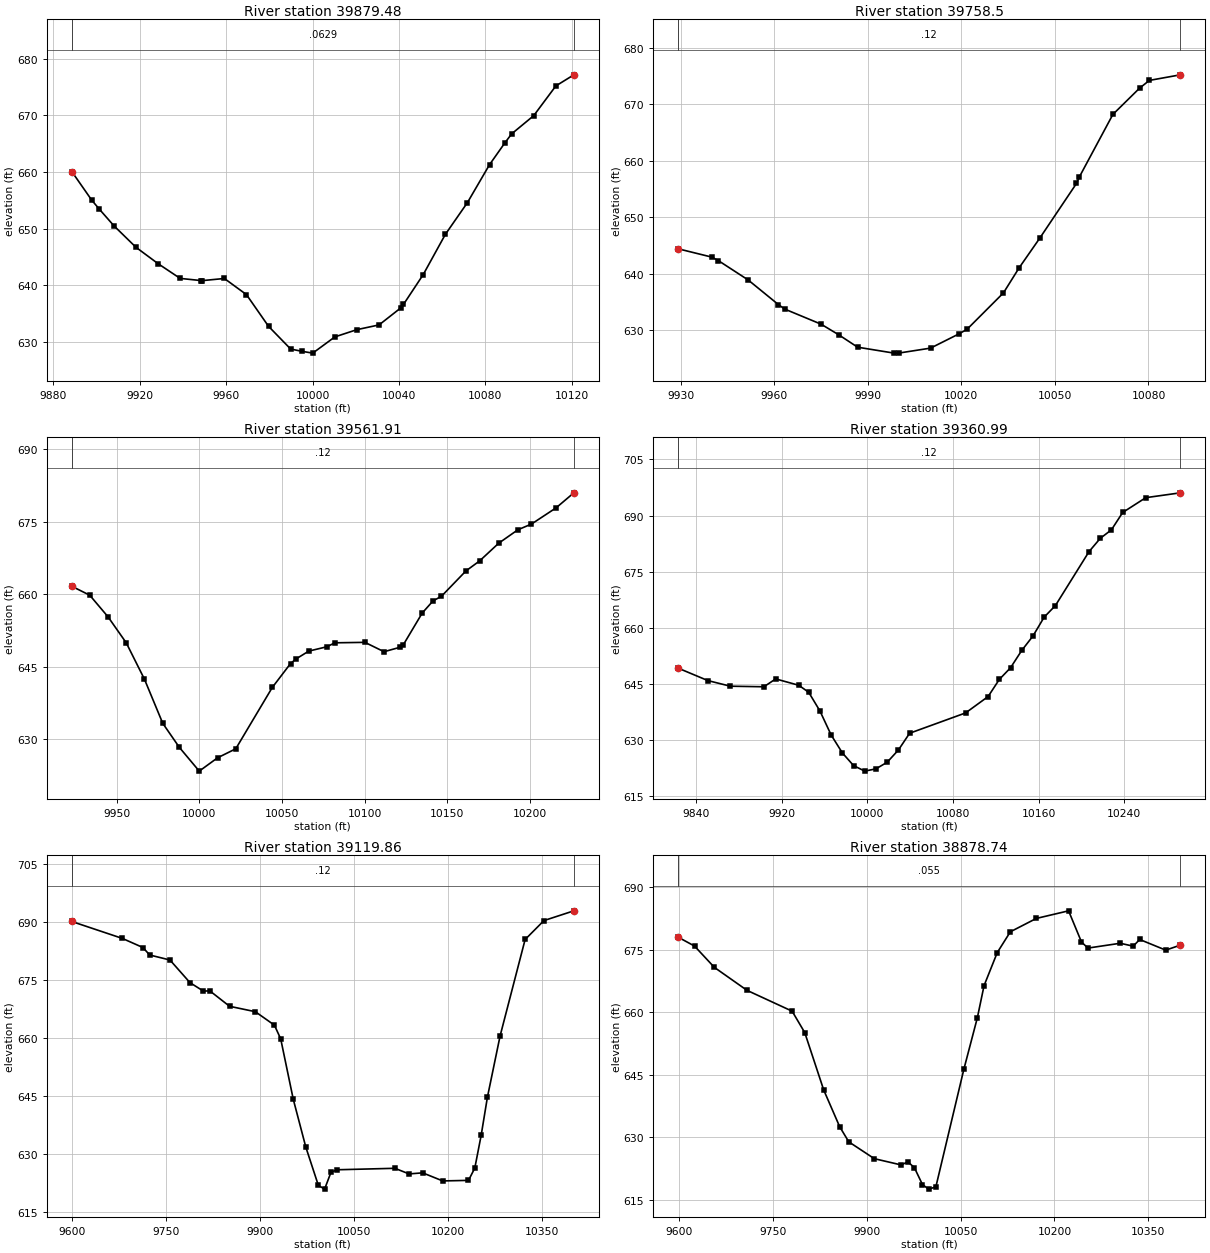
Type RM Length L Ch R = 1 ,39879.48,120.982100,120.982100,120.982100
XS GIS Cut Line= 2
664912.292681634833195.954284281664961.798975021833423.140699223
#Sta/Elev= 29
9888.483660.09049897.741655.02459901.198653.46029907.975650.5147 9918.21646.7039
9928.445643.81199938.679641.20729948.165640.83059948.914640.81389959.149641.1912
9969.383638.34179979.618632.73579989.853628.72589995.133 628.32210000.09 628.005
10010.32630.873510020.56632.156910030.79632.988910041.03636.0473 10042.1636.6058
10051.26641.8897 10061.5 648.98710071.73654.607510081.96661.306210089.07665.1557
 10092.2666.742410102.43 669.96410112.67675.2104   10121677.1715
#Mann= 3 , 0 , 0
9888.483  0.0629       09888.483  0.0629       0   10121  0.0629       0
#XS Ineff= 2 , 0
       09944.237                       0
Bank Sta=9888.483,10121
Exp/Cntr=0.3,0.1

Type RM Length L Ch R = 1 , 39758.5,196.594600,196.594600,196.594600
XS GIS Cut Line= 2
664798.360389948833305.817565545 664881.77510348833443.485751301
#Sta/Elev= 23
9929.245644.38539939.982642.92169942.058642.31599951.674638.86989961.355634.5202
9963.366633.72759975.059 631.0479980.652629.19019986.751626.97929998.444625.9288
9999.949625.938710010.14 626.81510019.25629.335510021.83630.142910033.52636.5957
10038.54641.027910045.21646.318210056.91 655.94510057.84657.1028 10068.6 668.173
10077.14672.808110080.29674.185710090.21 675.173
#Mann= 3 , 0 , 0
9929.245    0.12       09929.245    0.12       010090.21    0.12       0
#XS Ineff= 2 , 0
       09932.564                       0
Bank Sta=9929.245,10090.21
Exp/Cntr=0.3,0.1

Type RM Length L Ch R = 1 ,39561.91,200.916800,200.916800,200.916800
XS GIS Cut Line= 3
664625.156179875833377.296515197664769.253402114 833445.00484854
664894.253402114833517.921515197
#Sta/Elev= 30
9922.769 661.6569933.646 659.8059944.695655.34069955.743649.95299966.792642.4027
9977.841633.29719987.912628.31069999.939623.404310010.99626.154810022.04 628.025
10044.13640.709610055.18645.656710058.46646.604510066.23648.238910077.28649.1445
10081.97649.954710100.21650.050910111.79648.112710121.66649.051510123.37649.4909
10134.94656.132110141.51658.645310146.52659.576710161.36664.826210169.67666.9072
10181.25670.577210192.83673.346710201.05674.529410215.98677.892110226.69680.9898
#Mann= 3 , 0 , 0
9922.769    0.12       09922.769    0.12       010226.69    0.12       0
#XS Ineff= 2 , 0
       0                               0
Bank Sta=9922.769,10226.69
Exp/Cntr=0.3,0.1

Type RM Length L Ch R = 1 ,39360.99,241.125000,241.125000,241.125000
XS GIS Cut Line= 3
664458.489513218833611.671515197664566.128402114833578.685404077
664906.406179875833684.588181853
#Sta/Elev= 30
9823.289649.19729851.016 645.8779871.934644.38239903.311644.23099914.317646.3278
9935.869644.6307 9945.16 642.7529955.633637.76689966.106631.34799976.579626.5532
9987.052623.16329997.525621.6836   10008622.301310018.47624.065310028.94627.3348
10039.42631.810510091.72637.244610112.73641.6193 10123.2646.193710133.68649.3114
10144.15653.940910154.62657.8013 10165.1662.847110175.57665.927110206.99680.3534
10217.46683.892610227.93686.182310238.41690.808510259.98694.767110292.25696.0635
#Mann= 3 , 0 , 0
9823.289    0.12       09823.289    0.12       010292.25    0.12       0
#XS Ineff= 2 , 0
       09879.417                       0
Bank Sta=9823.289,10292.25
Exp/Cntr=0.3,0.1

Type RM Length L Ch R = 1 ,39119.86,241.125000,241.125000,241.125000
XS GIS Cut Line= 6
664151.687310214833706.231203854664346.988714039833788.822736564
 664488.06166318833818.102039881664562.873516684833810.201627835
664743.656390638833728.519646257664912.287720778833729.537923608
#Sta/Elev= 30
9599.073690.21119679.798685.83849712.694683.48139723.486681.5513 9755.86680.2569
9787.872674.39789809.135672.2314 9819.64672.26519851.046668.29369892.231666.8934
9922.628663.41849932.703659.87279952.755644.25779972.772631.91339992.781622.0249
10002.79 621.03910013.03625.4168 10023.3626.044610115.04626.422610137.65624.9701
10159.41625.244910191.41623.157510232.56623.300210242.64626.488310252.73634.9004
10262.81644.836410282.96660.595710322.98685.558410353.05690.444710400.78692.9667
#Mann= 3 , 0 , 0
9599.073    0.12       09599.073    0.12       010400.78    0.12       0
#XS Ineff= 2 , 0
       0                               0
Bank Sta=9599.073,10400.78
Exp/Cntr=0.3,0.1

Type RM Length L Ch R = 1 ,38878.74,241.125100,241.125100,241.125100
XS GIS Cut Line= 6
664290.285768524833869.227075529664505.738193088833924.621254162
664577.664704924833921.476823735664652.893756123833897.592490574
664763.635139488833950.354702017665057.374133834834028.722026805
#Sta/Elev= 30
9599.345678.0213 9625.38675.89499656.984670.78079709.162665.25549781.153660.2543
9801.352655.10369831.562641.33019857.139632.47789871.658628.85629912.413 624.813
9955.173623.31119966.024624.05469976.325622.66479989.294618.58269999.154617.4973
10010.63618.032310055.37646.309610076.85658.647310087.59666.384510108.71674.3456
10129.56679.326810171.01682.534810222.55684.363710243.16676.865410253.47675.4138
   10305676.5701 10325.7675.8745 10336.1677.477110377.67674.917110400.92676.1205
#Mann= 3 , 0 , 0
9599.345   0.055       09599.345   0.055       010400.92   0.055       0
#XS Ineff= 2 , 0
       0                               0
Bank Sta=9599.345,10400.92
Exp/Cntr=0.3,0.1