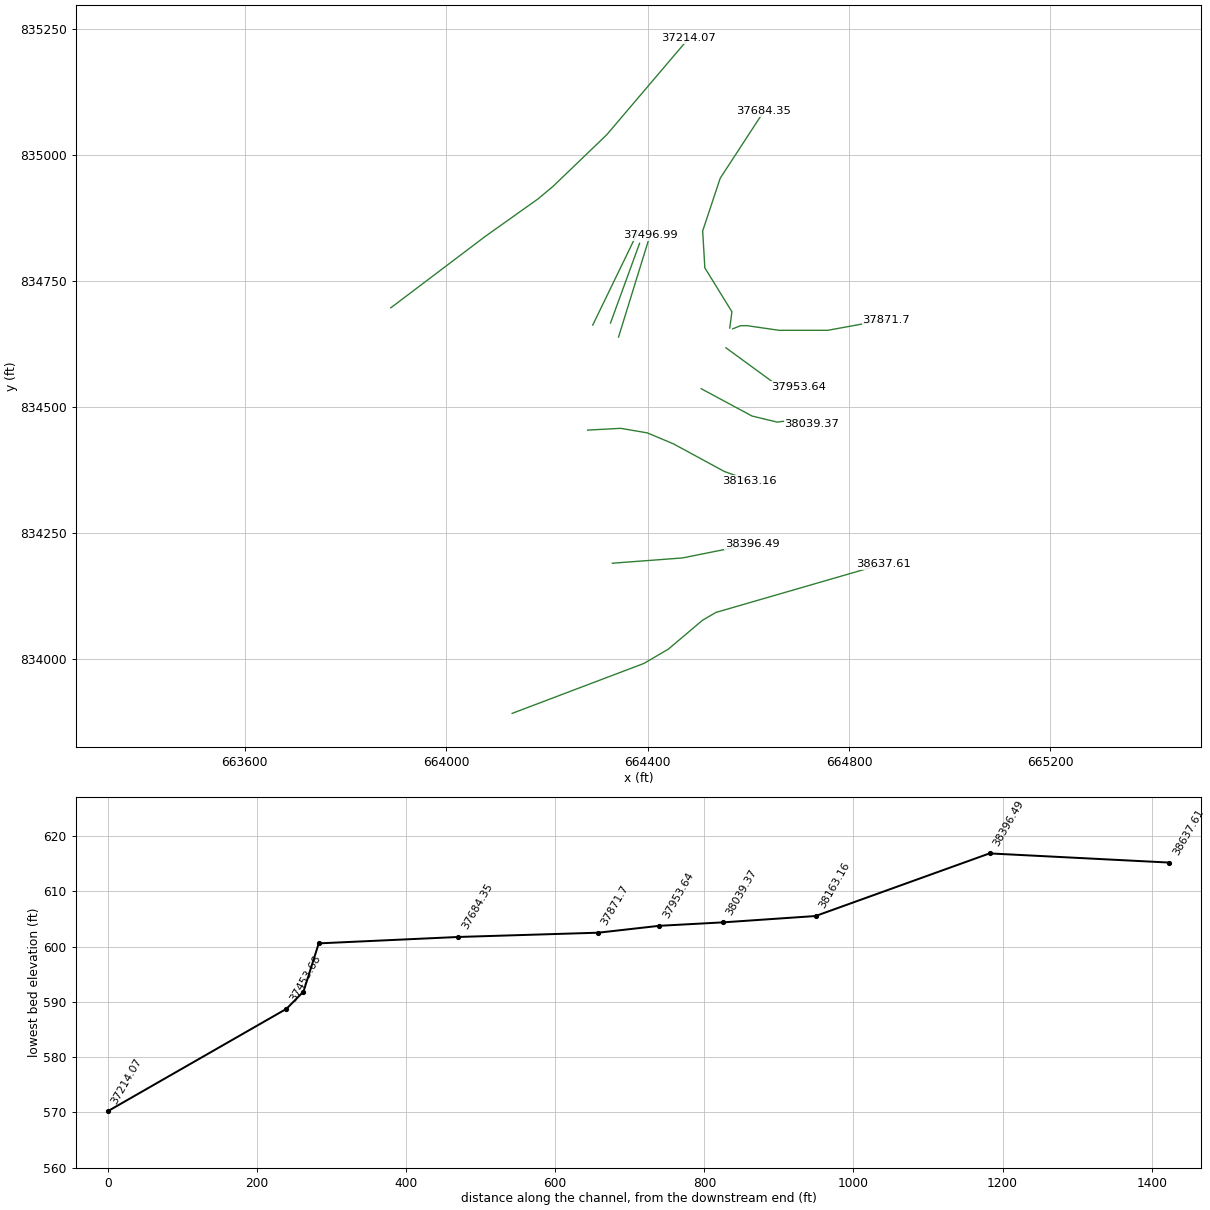
HEC-RAS study 13678_ras.prj: 13678

--- 13678_ras.g01 (geometry) --- (continued)

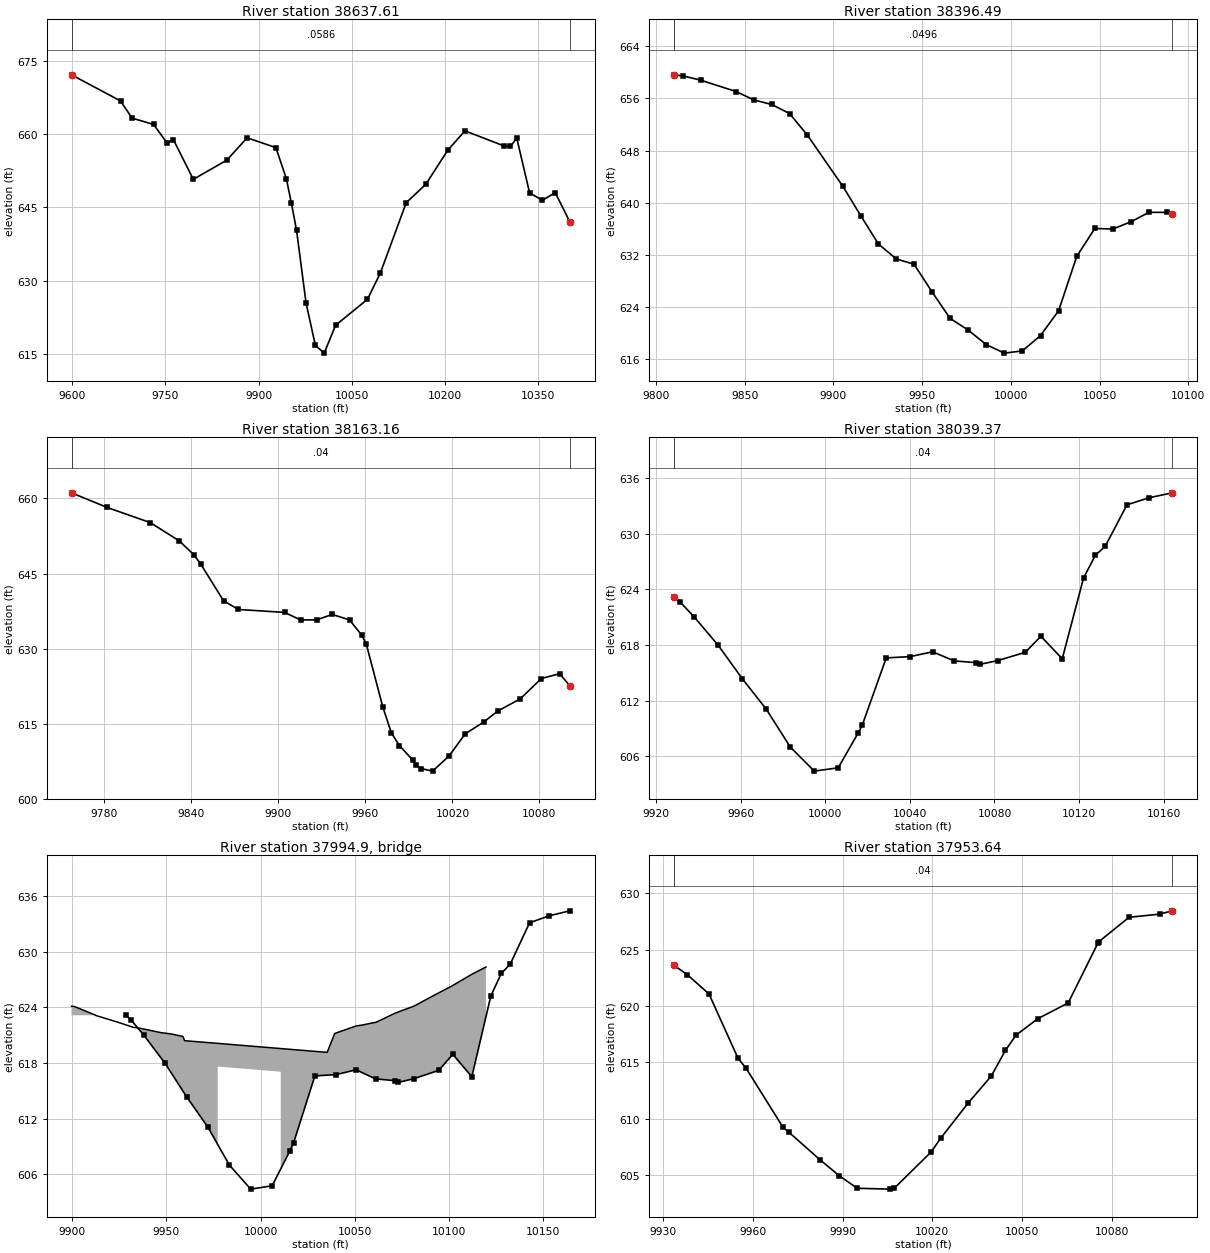
Type RM Length L Ch R = 1 ,38637.61,241.125000,241.125000,241.125000
XS GIS Cut Line= 6
664131.019814858833891.574859176  664392.7814484 833990.78725784
664441.049569126834019.061715911664508.883418592834076.346468348
 664535.59715217834092.004876552664867.818355254834188.259797004
#Sta/Elev= 30
9599.061672.11289677.834666.77019696.372 663.2619731.073661.95839752.369658.2391
9763.017 658.8219794.961650.74339848.887654.66999881.577659.24069927.828657.2256
9944.754650.82979952.671645.9166 9961.11640.30599976.324625.46869991.339616.7909
10005.57615.205610023.87620.897310075.11626.203810095.92631.590310137.56645.9674
10168.99649.725310204.11 656.64110231.98660.655510294.78657.5811 10305.1657.4766
10315.43659.156210336.07647.965210356.71646.452110377.35648.032310400.91642.0139
#Mann= 3 , 0 , 0
9599.061  0.0586       09599.061  0.0586       010400.91  0.0586       0
#XS Ineff= 2 , 0
       0                               0
Bank Sta=9599.061,10400.91
Exp/Cntr=0.3,0.1

Type RM Length L Ch R = 1 ,38396.49,233.325500,233.325500,233.325500
XS GIS Cut Line= 3
 664330.01729098834189.796515182664468.906179875834200.213181853
  664607.7950688834227.990959629
#Sta/Elev= 28
9810.073659.63649815.069659.47259825.097658.82239845.153 657.0659855.182655.7708
 9865.21655.07819875.238653.69029885.266 650.3899905.322642.4935 9915.35638.0105
9925.378633.63119935.406631.34589945.434630.51929955.566626.29179965.764622.2019
9975.962620.4043 9986.16618.16799996.358616.864510006.56617.211810016.75619.5733
10026.95623.386210037.15631.730810047.35636.028310057.55635.931510067.74637.0563
10077.94638.506210088.14638.494610090.99638.3083
#Mann= 3 , 0 , 0
9810.073  0.0496       09810.073  0.0496       010090.99  0.0496       0
#XS Ineff= 2 , 0
       0                               0
Bank Sta=9810.073,10090.99
Exp/Cntr=0.3,0.1

Type RM Length L Ch R = 1 ,38163.16,123.793600,123.793600,123.793600
XS GIS Cut Line= 6
664280.839462114834454.109664241664346.527124381  834457.6569694
664399.307235796834448.635849181664451.146719426834426.922259957
664552.445979519834371.968823262 664601.83452792834354.038799362
#Sta/Elev= 30
9757.358661.11899781.661658.21869811.699655.16299831.756651.49529841.823648.6992
9846.263646.96379862.156 639.5569872.437637.81889904.203637.23929915.232 635.739
9926.321635.73959937.059636.82969949.028635.74379957.468632.6802  9960.5631.0229
9971.971618.35659977.877 613.1859983.442610.63919992.468607.79529994.908606.7133
9998.362606.048610006.32605.534310017.63 608.54510028.84 612.988 10041.7615.3599
10051.16617.5148 10066.9 619.995 10081.3624.029410093.89 624.99110101.01622.5758
#Mann= 3 , 0 , 0
9757.358    0.04       09757.358    0.04       010101.01    0.04       0
#XS Ineff= 2 , 0
       0                               0
Bank Sta=9757.358,10101.01
Exp/Cntr=0.3,0.1

Type RM Length L Ch R = 1 ,38039.37,85.732300,85.732300,85.732300
XS GIS Cut Line= 5
664506.490949899834536.307337463664607.445948362 834482.08008115
664657.635004729834469.965481341 664690.51748994834474.580566972
664725.707517952834465.350395694
#Sta/Elev= 27
9928.309 623.1519931.072 622.6839937.968621.0134 9949.32617.95379960.671614.3612
9972.022611.07149983.373606.99249994.725604.390310006.08604.7499 10015.6608.5537
10017.43609.353110028.78 616.60910040.13616.750210050.68617.268310060.96 616.285
10071.25616.097210073.08615.910210081.54616.317910094.54617.211110101.97618.9411
10112.07616.513210122.17 625.24310127.74627.684110132.38628.641110142.71633.1289
10153.05633.883210164.12634.4229
#Mann= 3 , 0 , 0
9928.309    0.04       09928.309    0.04       010164.12    0.04       0
#XS Ineff= 2 , 0
       0                               0
Bank Sta=9928.309,10164.12
Exp/Cntr=0.3,0.1

Type RM Length L Ch R = 3 , 37994.9,,,
BEGIN DESCRIPTION:
END DESCRIPTION:
Bridge Culvert--1,0,-1,-1, 0
Deck Dist Width WeirC Skew NumUp NumDn MinLoCord MaxHiCord MaxSubmerge Is_Ogee
25.477750,34.776800,2.6,0, 27, 27, , , 0.95, 0, 0,0,,
 9899.65 9901.26 9912.01 9912.76 9924.27 9932.23 9935.77 9947.28 9952.45 9958.78
 9959.63 9977.20 9977.2010010.6610010.6610035.3010039.3210050.8210053.5610053.64
10061.2810071.3910081.5010091.6210101.7310111.8410119.56
  624.13  624.09  623.19  623.11  622.40  621.86  621.76  621.27  621.14  620.86
  620.41  620.12  620.12  619.56  619.56  619.15  621.19  622.01  622.08  622.09
  622.40  623.38  624.15  625.26  626.34  627.55  628.36
 -375.87 -375.91 -376.81 -376.89 -377.60 -378.14 -378.24 -378.73 -378.86 -379.14
 -379.59 -379.88  617.62  617.06 -380.44 -380.85 -378.81 -377.99 -377.92 -377.91
 -377.60 -376.62 -375.85 -374.74 -373.66 -372.45 -371.64
 9899.65 9901.26 9912.01 9912.76 9924.27 9932.23 9935.77 9947.28 9952.45 9958.78
 9959.63 9984.78 9984.7810018.2410018.2410035.3010039.3210050.8210053.5610053.64
10061.2810071.3910081.5010091.6210101.7310111.8410119.56
  624.13  624.09  623.19  623.11  622.40  621.86  621.76  621.27  621.14  620.86
  620.41  619.99  619.99  619.44  619.44  619.15  621.19  622.01  622.08  622.09
  622.40  623.38  624.15  625.26  626.34  627.55  628.36
 -375.87 -375.91 -376.81 -376.89 -377.60 -378.14 -378.24 -378.73 -378.86 -379.14
 -379.59 -380.01  617.49  616.94 -380.56 -380.85 -378.81 -377.99 -377.92 -377.91
 -377.60 -376.62 -375.85 -374.74 -373.66 -372.45 -371.64
BR Coef=-1 , 0 , 0 ,, 0 ,,,0.8,0,1,0,
WSPro=,,,, 1 ,,,, 0 ,,,, 0 ,,,,-1 ,-1 ,-1 , 0 , 0 , 0 , 0 , 0
BC Design=,, 0 ,, 0 ,,,,,,

Type RM Length L Ch R = 1 ,37953.64,81.938400,81.938400,81.938400
XS GIS Cut Line= 3
664555.526234865 834617.64822194664647.827947766834550.152594388
664699.170775503834540.345537409
#Sta/Elev= 25
9933.584623.6228 9938.07622.7855 9945.32 621.0779955.012615.37869957.709614.4894
9970.097609.23549971.953608.82989982.485606.35699988.894604.94869994.874 603.842
10005.84603.765310007.26603.844310019.65607.079610022.78608.282710032.04611.4261
10039.72613.804410044.43616.074110047.93617.409810055.23618.881910065.41620.2783
10075.39625.605310075.59625.699610085.77627.878310095.96628.1576 10100.2628.4515
#Mann= 3 , 0 , 0
9933.584    0.04       09933.584    0.04       0 10100.2    0.04       0
#XS Ineff= 2 , 0
       0                               0
Bank Sta=9933.584,10100.2
Exp/Cntr=0.3,0.1

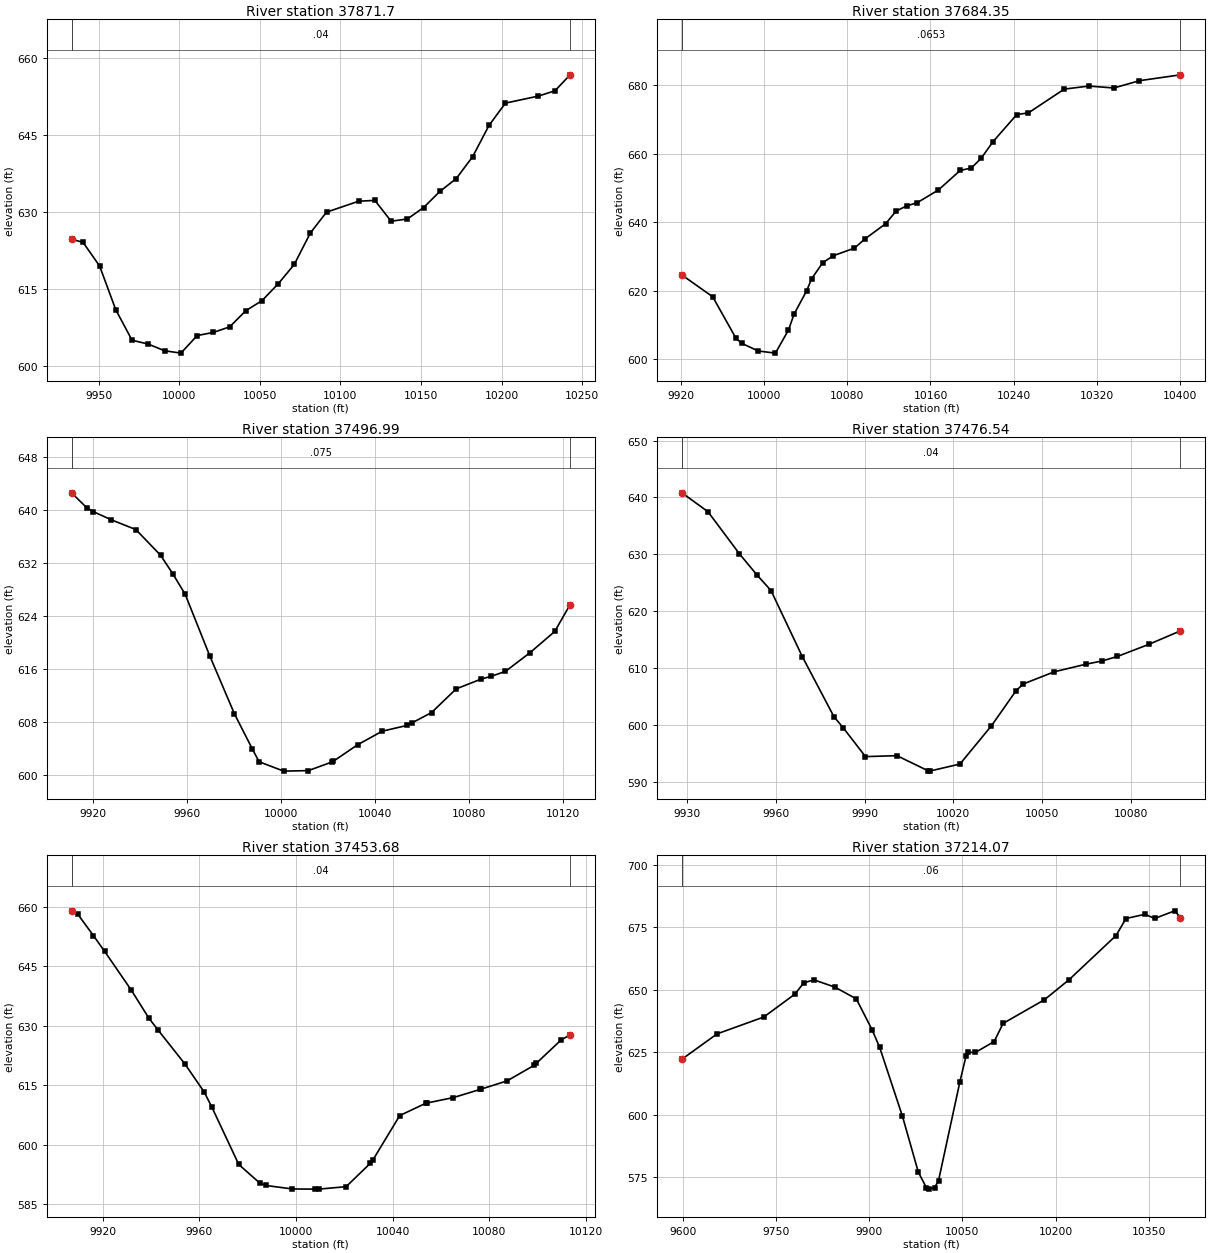
Type RM Length L Ch R = 1 , 37871.7,187.353100,187.353100,187.353100
XS GIS Cut Line= 6
664568.956956906834655.240090495664584.356999146834661.371902235
664596.531896935 834661.67924957664660.842209709834652.330202672
664757.402471505834652.289695839664874.067614755 834673.49305397
#Sta/Elev= 30
9933.239624.65159940.311624.08299950.641619.45369960.644610.95779970.736605.0337
9980.844604.27079990.951602.979310001.07 602.51810011.16605.933610021.26606.5548
10031.33607.627210041.34610.764710051.36612.722310061.38615.978410071.39619.7614
 10081.4625.890210091.41629.934910111.43632.070910121.44632.222610131.51628.1735
 10141.6628.611310151.68  630.8410161.77633.975910171.86636.452410182.05640.7077
10192.24 646.80610202.43651.146310222.85652.510610233.18653.544110242.55656.6489
#Mann= 3 , 0 , 0
9933.239    0.04       09933.239    0.04       010242.55    0.04       0
#XS Ineff= 2 , 0
       0                               0
Bank Sta=9933.239,10242.55
Exp/Cntr=0.3,0.1

Type RM Length L Ch R = 1 ,37684.35,187.353200,187.353200,187.353200
XS GIS Cut Line= 6
664563.130585545834656.878692721664567.447547669834689.200600856
664513.655205136834776.351497695664509.378038088834849.658256368
664544.246401011834954.425047255664630.709647062835086.949006088
#Sta/Elev= 30
9920.651624.56999950.218618.22589972.681606.06989978.155604.61279994.109602.3734
10010.63601.747110023.19608.490210028.68613.2021 10040.7 619.95210045.52623.4896
10056.16628.165510066.47630.233510086.75632.4415 10096.8635.110310116.82639.5821
10126.83643.260710136.93644.777410147.09645.702710167.69649.457210188.68655.1662
10199.33655.8568 10208.9658.725410220.17663.541810243.04671.467710254.42672.0005
10288.87 678.93310312.49679.825210336.63679.268210361.35681.400710400.84683.1113
#Mann= 3 , 0 , 0
9920.651  0.0653       09920.651  0.0653       010400.84  0.0653       0
#XS Ineff= 2 , 0
       0                               0
Bank Sta=9920.651,10400.84
Exp/Cntr=0.3,0.1

Type RM Length L Ch R = 1 ,37496.99,20.447600,20.447600,20.447600
XS GIS Cut Line= 2
  664342.2833471834638.892477036664404.900200725834841.232888371
#Sta/Elev= 28
9911.074642.61879917.467640.37919920.263639.78179927.935638.54739938.403637.0648
9948.871633.19479954.089630.38379959.339627.29519969.807617.97119980.275609.2337
9987.915603.90899990.743602.001210001.21 600.58710011.68 600.66510021.74 601.969
10022.15602.042610032.61604.570210043.08606.620810053.55607.484410055.57607.8461
10064.02609.432810074.49613.009710084.95 614.47110089.39614.910110095.42615.6514
10105.89618.486110116.36621.679310122.88 625.727
#Mann= 3 , 0 , 0
9911.074   0.075       09911.074   0.075       010122.88   0.075       0
#XS Ineff= 2 , 0
       0                               0
Bank Sta=9911.074,10122.88
Exp/Cntr=0.3,0.1

Type RM Length L Ch R = 1 ,37476.54,22.861700,22.861700,22.861700
XS GIS Cut Line= 2
664326.306806684834666.744644731664384.090728372834825.022343323
#Sta/Elev= 23
9928.289640.80589937.077637.47399947.723630.06479953.638626.35459958.368623.6264
9969.014611.93939979.659601.42829982.797599.47949990.305594.417810000.95594.5819
 10011.6591.892910011.96591.865210022.24593.114610032.89599.843610041.12605.9443
10043.53607.169110054.18609.344710064.82610.667110070.28611.240510075.47612.0344
10086.12614.164910096.76616.531410096.78616.5424
#Mann= 3 , 0 , 0
9928.289    0.04       09928.289    0.04       010096.78    0.04       0
#XS Ineff= 2 , 0
       0                               0
Bank Sta=9928.289,10096.78
Exp/Cntr=0.3,0.1

Type RM Length L Ch R = 1 ,37453.68,239.610300,239.610300,239.610300
XS GIS Cut Line= 2
664291.051375955834662.697231323664381.095446467834848.477813601
#Sta/Elev= 30
9907.062659.01549909.621658.15919916.115652.75459920.733 648.7869931.846638.9374
9939.043631.93769942.959628.84919954.071620.28319961.971613.27369965.184609.4069
9976.297594.96229984.899590.32299987.409589.67229998.522588.784610007.83 588.742
10009.63588.756610020.75589.360210030.75 595.24410031.86596.123210042.97607.3209
10053.68610.404110054.09610.4703 10065.2611.861210076.31 613.92910076.61613.9871
10087.42616.074710098.54619.973610099.54620.523410109.65626.323310113.51 627.726
#Mann= 3 , 0 , 0
9907.062    0.04       09907.062    0.04       010113.51    0.04       0
#XS Ineff= 2 , 0
       0                               0
Bank Sta=9907.062,10113.51
Exp/Cntr=0.3,0.1

Type RM Length L Ch R = 1 ,37214.07,239.610300,239.610300,239.610300
XS GIS Cut Line= 6
663889.980630166834696.946524924664078.080393502 834839.16480082
664181.885433686834912.910210873664212.899445032834938.820554069
 664319.20637358835041.062959498664481.687993817835232.158783046
#Sta/Elev= 30
9599.024622.21339655.463632.32989730.682639.08029780.829648.25979794.769652.7369
 9811.35653.94219844.912651.04089879.446646.32249904.658 634.0469916.924626.9986
9953.724599.34199979.207577.00929992.198570.79529996.777570.215210005.44570.8601
10011.72573.616310046.16613.236610056.08623.598110059.74624.972710070.87624.8802
10101.25629.264610115.54636.511910182.04645.970810221.94654.040410297.23 671.658
10313.32 678.478 10343.9680.173710359.46678.499310391.64681.556710400.98678.8514
#Mann= 3 , 0 , 0
9599.024    0.06       09599.024    0.06       010400.98    0.06       0
#XS Ineff= 2 , 0
       0                               0
Bank Sta=9599.024,10400.98
Exp/Cntr=0.3,0.1