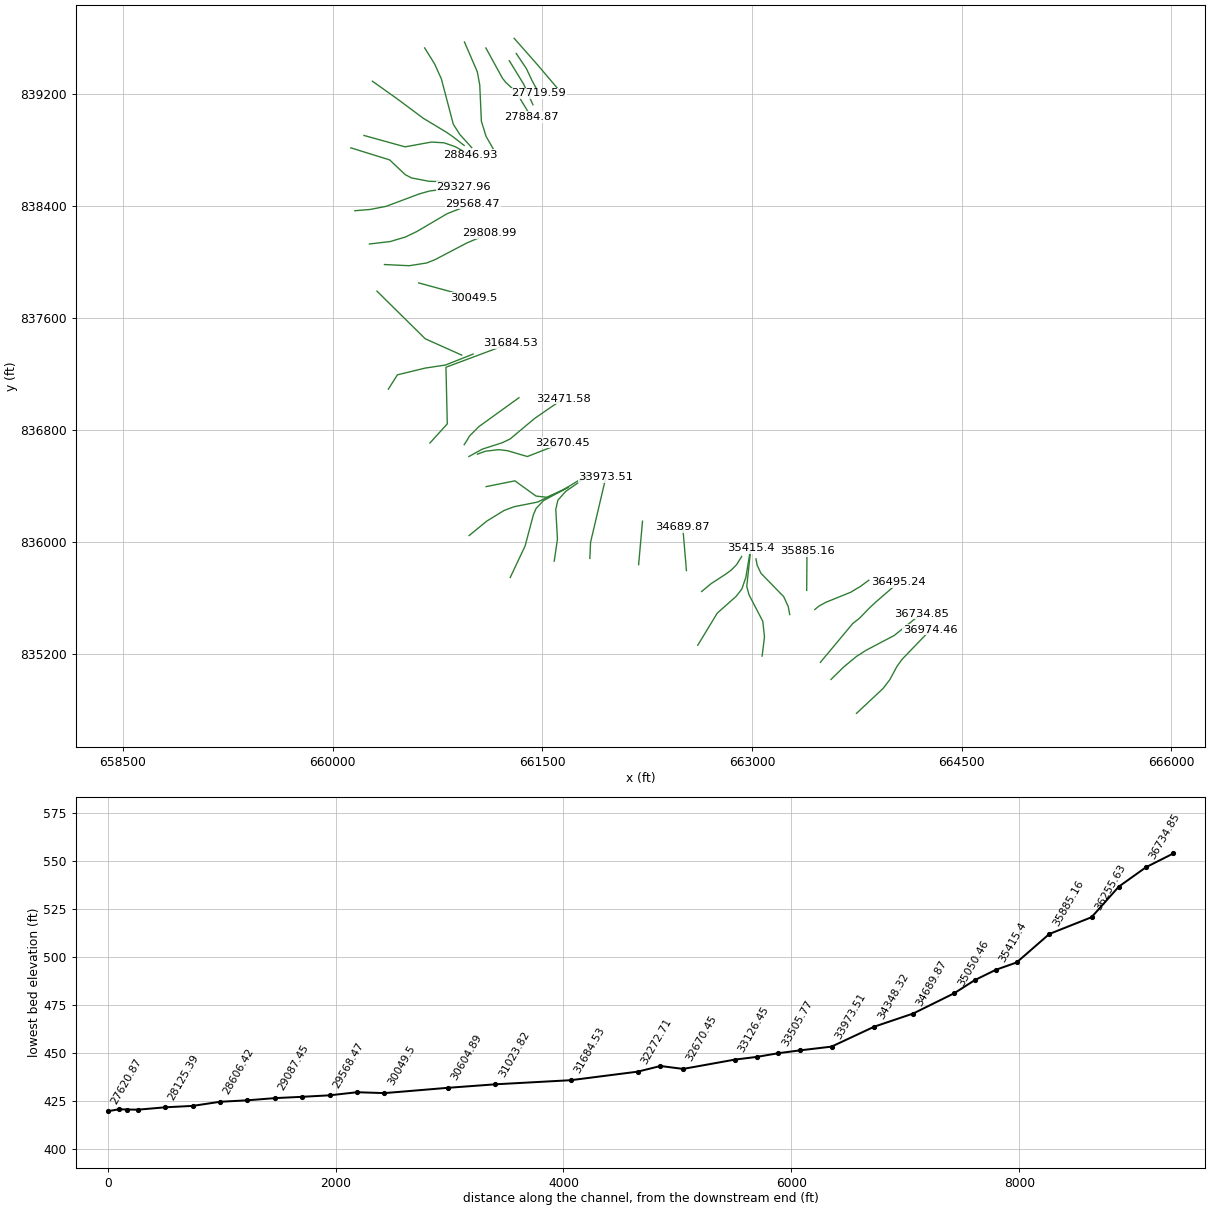
HEC-RAS study 13678_ras.prj: 13678

--- 13678_ras.g01 (geometry) --- (continued)

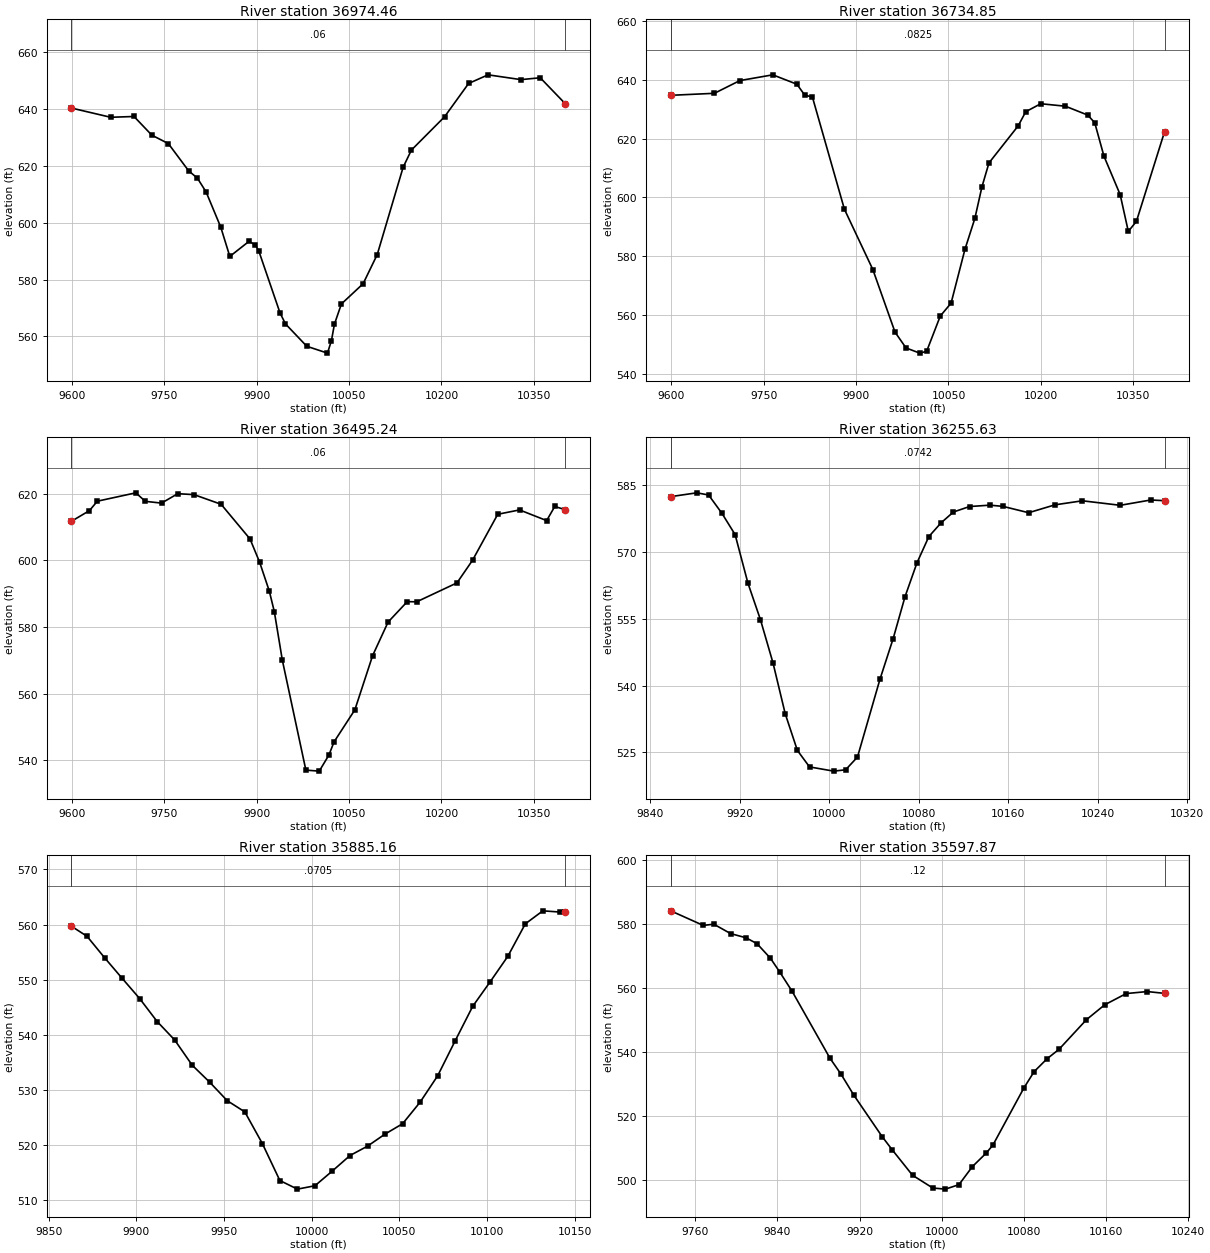
Type RM Length L Ch R = 1 ,36974.46,239.610300,239.610300,239.610300
XS GIS Cut Line= 6
663747.188407275834777.604453517663937.083360756834955.402029303
663986.091105249835019.029151985664036.222093432835112.166068244
664071.284914172835161.457647951664275.774400551835373.749451635
#Sta/Elev= 30
 9599.05640.23969662.886 636.9949700.765637.27379729.644630.72439756.542627.7476
9789.358 618.2169803.697615.60169817.813610.76519841.644598.37989856.312588.1108
9887.549593.41559897.714592.15719903.277590.08879937.846568.26159946.679 564.413
9981.266556.553610014.89554.143610021.35558.563210026.18564.309710037.47571.4154
10072.77578.532510095.68588.775810137.69619.419610151.12625.4679   10205637.1743
10244.04648.876410275.61651.907910329.02650.222210360.33650.875510400.93641.7648
#Mann= 3 , 0 , 0
 9599.05    0.06       0 9599.05    0.06       010400.93    0.06       0
#XS Ineff= 2 , 0
       0                               0
Bank Sta=9599.05,10400.93
Exp/Cntr=0.3,0.1

Type RM Length L Ch R = 1 ,36734.85,239.610300,239.610300,239.610300
XS GIS Cut Line= 6
663565.189042369835020.055593692663657.565127902835110.818467385
663747.677918341835184.672433104663816.806994538835228.878710945
664017.135274553835334.087588396664209.720246572835488.899826632
#Sta/Elev= 30
9599.047634.72519669.999635.40889711.326 639.7429764.766641.69859803.911638.5019
9816.524634.83119829.137634.10739881.067595.9497 9927.22575.42759963.243554.1161
9981.111548.739510003.43546.974810014.54547.574610036.75559.608210054.25563.9821
10076.78582.307710092.86592.8189 10104.3603.512610115.75611.700610163.27624.3456
10175.48629.141210199.88631.861810239.96631.012110276.12628.000210287.51 625.397
10302.48614.016310328.84600.900210342.02588.4099 10355.2591.817310400.96622.3895
#Mann= 3 , 0 , 0
9599.047  0.0825       09599.047  0.0825       010400.96  0.0825       0
#XS Ineff= 2 , 0
       0                               0
Bank Sta=9599.047,10400.96
Exp/Cntr=0.3,0.1

Type RM Length L Ch R = 1 ,36495.24,239.610300,239.610300,239.610300
XS GIS Cut Line= 6
663488.798527259835142.236497742663719.852745031835418.667615013
663771.576748136835459.816061709663832.388817669 835523.11919559
663880.230240677835568.343710051 664047.82946565835713.588344365
#Sta/Elev= 30
9599.059611.70369628.382614.91469641.264617.74139703.722 620.2499719.135617.6986
 9745.48617.16459771.824619.99249798.168619.70979842.161 616.8219889.132606.4194
9904.789599.41779920.446 590.7869928.599 584.6179941.596570.07499979.825537.1057
10001.54536.808410017.19541.615110025.55545.573310059.36555.1913 10088.2571.4467
10113.33581.504810144.44587.625310159.74587.572810225.17593.2523 10250.4600.0306
10291.34613.818210326.75615.125810370.73611.922510383.96616.164610400.94615.1863
#Mann= 3 , 0 , 0
9599.059    0.06       09599.059    0.06       010400.94    0.06       0
#XS Ineff= 2 , 0
       0                               0
Bank Sta=9599.059,10400.94
Exp/Cntr=0.3,0.1

Type RM Length L Ch R = 1 ,36255.63,370.470600,370.470600,370.470600
XS GIS Cut Line= 6
663449.085176224835519.625690907663476.933331858835542.811298296
663525.487770604835570.046008151663704.800419963835642.561233562
663774.700090144835684.282211636 663834.99357837835728.416630947
#Sta/Elev= 30
9858.236582.43369881.561583.28519892.117582.80299904.046578.68269915.833 573.901
9927.277563.02449938.496554.80399949.714545.11049960.615533.72119971.499525.4668
9982.383521.760110004.01520.814110014.64521.108110025.27523.9728 10045.4541.4563
10057.17 550.553 10067.8559.974310078.43 567.53910089.13573.471910100.11576.5691
10111.09  578.9810125.47580.2059 10143.8 580.51710155.47580.238710178.36578.8193
10201.93580.591210226.45 581.49810260.31580.484810287.57581.678610299.96581.5194
#Mann= 3 , 0 , 0
9858.236  0.0742       09858.236  0.0742       010299.96  0.0742       0
#XS Ineff= 2 , 0
       0                               0
Bank Sta=9858.236,10299.96
Exp/Cntr=0.3,0.1

Type RM Length L Ch R = 1 ,35885.16,287.287000,287.287000,287.287000
XS GIS Cut Line= 2
663390.967918336 835656.06596294663393.070240378835937.777117476
#Sta/Elev= 30
9862.938559.70229871.872557.87429881.872553.99269891.873550.27199901.873546.5993
9911.873542.43099921.874539.08189931.874534.51229941.874531.42729951.874528.0795
9961.875526.05489971.875520.32429981.875513.61629991.875 512.05910001.88512.6687
10011.88515.363710021.88518.149310031.88519.848710041.88522.035610051.88523.9069
10061.88527.820110071.88532.590910081.88538.940310091.88545.184410101.88549.6507
10111.88554.231410121.88560.127110131.88562.487210141.88 562.26110144.66562.2964
#Mann= 3 , 0 , 0
9862.938  0.0705       09862.938  0.0705       010144.66  0.0705       0
#XS Ineff= 2 , 0
       0                               0
Bank Sta=9862.938,10144.66
Exp/Cntr=0.3,0.1

Type RM Length L Ch R = 1 ,35597.87,182.471000,182.471000,182.471000
XS GIS Cut Line= 6
663269.643283633835483.623790647663258.853100881835540.788869688
663226.636138469835611.176972174663063.881048551835777.980848451
 663036.70634875835835.866444337 663027.90075247835881.694421017
#Sta/Elev= 30
9736.047584.09849767.775 579.5399777.977579.93079794.297576.99619809.446575.6707
9820.105573.82629833.094569.31199842.178564.99829854.222558.98229891.152538.0395
9901.792 533.1189914.342526.52429942.025513.52429951.748509.43729971.473 501.514
9991.179497.523310003.44497.171610016.69498.566310029.83504.223310043.22508.4253
 10049.8510.951210079.95528.783410089.87533.859610102.36537.853510114.11540.8385
10140.84550.0974 10158.6554.737310179.57558.257310200.06558.880810216.94558.3152
#Mann= 3 , 0 , 0
9736.047    0.12       09736.047    0.12       010216.94    0.12       0
#XS Ineff= 2 , 0
       0                               0
Bank Sta=9736.047,10216.94
Exp/Cntr=0.3,0.1

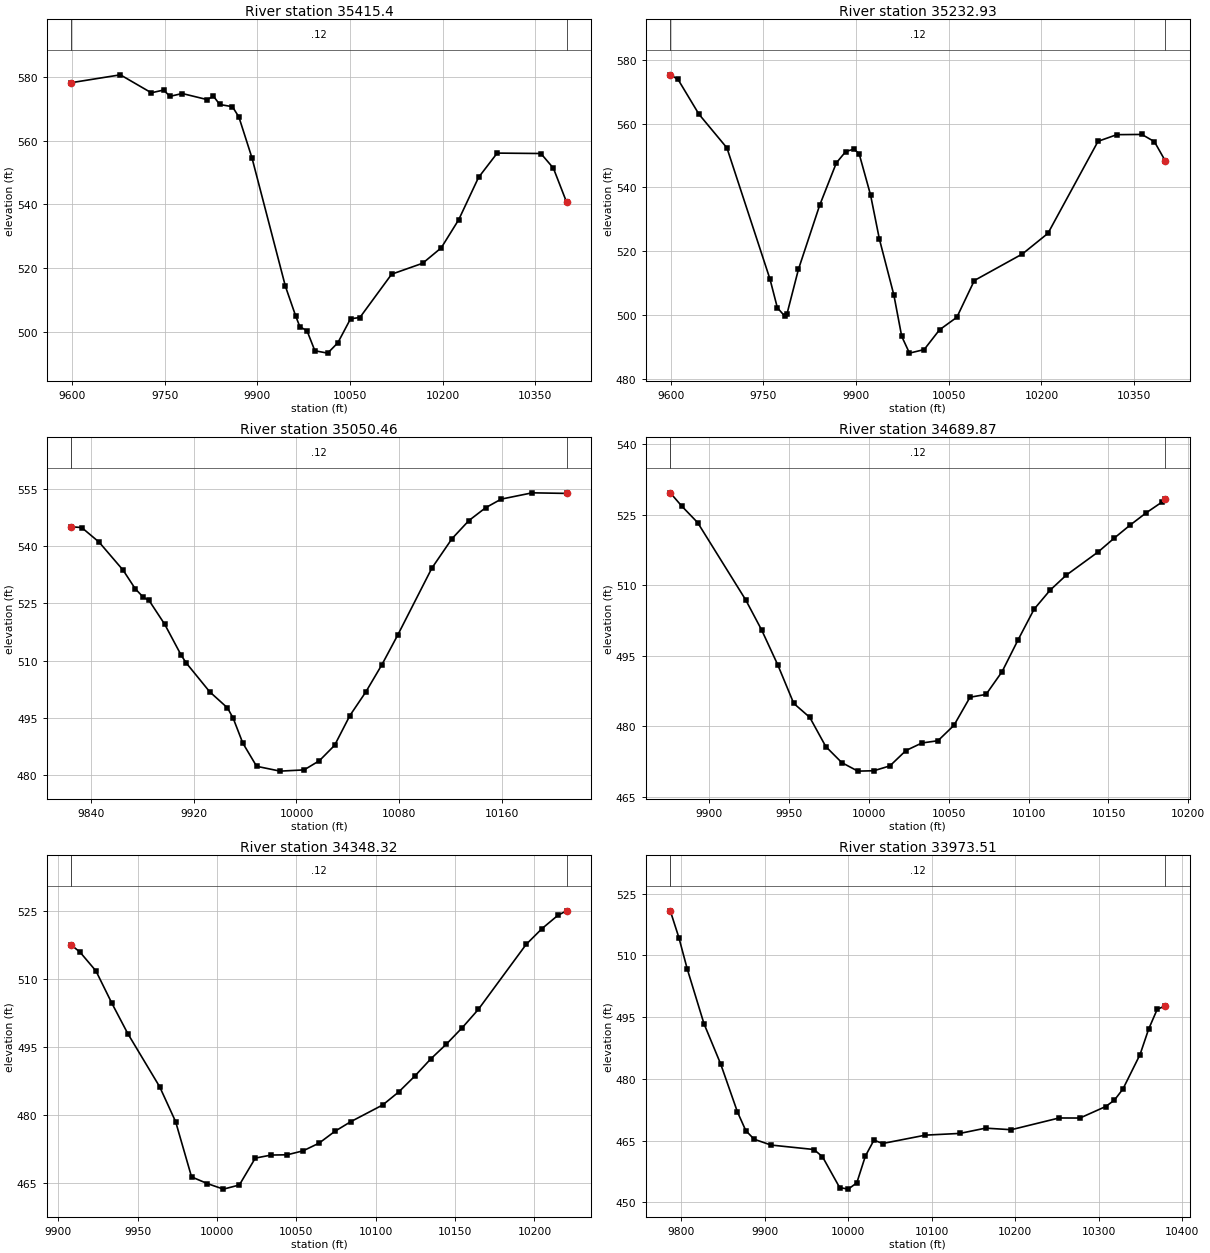
Type RM Length L Ch R = 1 , 35415.4,182.470900,182.470900,182.470900
XS GIS Cut Line= 6
 663072.07520017835186.893956216663088.999385333835323.054980621
663076.914157107835435.384430258662977.747439132 835625.66374421
662962.196461924835685.293260961662991.356869818835956.136694493
#Sta/Elev= 30
9599.182578.2321 9678.44580.69069728.551575.05119748.582575.91999758.597573.9316
9778.627574.82439818.937572.91429829.097573.99359839.256571.38359859.841 570.685
9870.276567.46839891.492554.62459945.607514.31639962.332504.95049968.961501.6494
9980.673500.32159993.321494.077110014.09493.339210030.51496.5909 10051.1504.1248
10066.21504.521210117.62518.117310167.77521.543310197.89526.381810226.16535.2053
10258.26 548.475 10288.5556.125410359.22555.994110379.45551.399910400.83540.7268
#Mann= 3 , 0 , 0
9599.182    0.12       09599.182    0.12       010400.83    0.12       0
#XS Ineff= 2 , 0
       0                               0
Bank Sta=9599.182,10400.83
Exp/Cntr=0.3,0.1

Type RM Length L Ch R = 1 ,35232.93,182.471000,182.471000,182.471000
XS GIS Cut Line= 6
662611.489688176835264.024558621662751.027330194835493.460859919
662886.322201409835613.718791498662927.088355501835666.071865965
 662955.95346069835750.151339666 662987.75574819835942.683428622
#Sta/Elev= 30
9599.071575.27499611.501573.86719645.477562.92879690.782552.37119760.547511.2046
9772.424502.27069784.301499.63979788.065500.3505  9806.6514.31379840.824 534.325
 9867.98547.67179883.182551.22649896.356 551.9819904.802550.57729923.323537.6288
9937.643523.78559961.032506.30489973.797493.29149986.369488.032110010.12489.1408
10035.04495.346410063.08499.2695 10091.4510.795210169.25519.1255 10210.6525.5907
10291.68554.433210322.09556.516710362.63556.5878 10382.9554.337310400.82548.2039
#Mann= 3 , 0 , 0
9599.071    0.12       09599.071    0.12       010400.82    0.12       0
#XS Ineff= 2 , 0
       0                               0
Bank Sta=9599.071,10400.82
Exp/Cntr=0.3,0.1

Type RM Length L Ch R = 1 ,35050.46,360.590600,360.590600,360.590600
XS GIS Cut Line= 6
662639.376388957 835648.05662528662706.720815002835704.046652326
662814.946573699835774.425531924662852.062891312835802.145475738
662889.395691936835839.710409351662925.724740059835898.756918452
#Sta/Elev= 30
9824.743545.03029832.747544.82989846.244541.03269865.024533.66949874.479528.7969
 9880.87526.55249885.183525.77079897.438519.49669910.267511.40279914.167509.3998
9932.431501.85859946.221497.67069950.695494.96269958.171488.46449968.959482.3722
9987.223 481.10810005.92481.429210017.81483.8249 10029.7487.864110041.59 495.642
10054.07501.860310066.55508.971810079.03516.825310105.45 534.22910121.11  541.92
10134.28546.663410147.27550.008610159.37552.264410183.56553.915810210.34553.7633
#Mann= 3 , 0 , 0
9824.743    0.12       09824.743    0.12       010210.34    0.12       0
#XS Ineff= 2 , 0
       0                               0
Bank Sta=9824.743,10210.34
Exp/Cntr=0.3,0.1

Type RM Length L Ch R = 1 ,34689.87,341.554200,341.554200,341.554200
XS GIS Cut Line= 2
 662530.52819398 835797.93879281662504.486527324836106.966570586
#Sta/Elev= 30
9875.563529.69259882.649526.90169892.684523.36679922.791506.92649932.826500.4922
9942.862493.11979952.897484.90699962.932481.93219972.968475.72369983.003472.3068
9993.039470.501310003.07470.581810013.11471.616610023.15474.876810033.18476.4894
10043.22476.966910053.25480.253210063.29486.218310073.32 486.81410083.36491.6485
10093.39498.420410103.43504.948110113.46508.9902 10123.5512.160510143.57517.1277
10153.61520.059410163.64522.848610173.68  525.4510183.71527.768610185.69528.3538
#Mann= 3 , 0 , 0
9875.563    0.12       09875.563    0.12       010185.69    0.12       0
#XS Ineff= 2 , 0
       0                               0
Bank Sta=9875.563,10185.69
Exp/Cntr=0.3,0.1

Type RM Length L Ch R = 1 ,34348.32,374.808400,374.808400,374.808400
XS GIS Cut Line= 2
662188.514305085835839.605459481662216.292082846836150.369348377
#Sta/Elev= 29
9908.239517.38329913.655515.83769923.695511.69459933.735504.57359943.775497.8825
9963.855486.18039973.894478.50459983.934466.33629993.974464.851710004.01463.6424
10014.05464.553610024.09470.476910034.13471.149410044.17 471.20310054.21472.0764
10064.25 473.76410074.29476.385310084.33478.512110104.41482.185710114.45485.0393
10124.49488.496910134.53492.273910144.57495.603910154.61499.240310164.65 503.229
10194.77517.546710204.81521.037510214.85523.970510220.24524.9378
#Mann= 3 , 0 , 0
9908.239    0.12       09908.239    0.12       010220.24    0.12       0
#XS Ineff= 2 , 0
       0                               0
Bank Sta=9908.239,10220.24
Exp/Cntr=0.3,0.1

Type RM Length L Ch R = 1 ,33973.51,278.071300,278.071300,278.071300
XS GIS Cut Line= 3
661839.555971742835884.744348392661844.764305085 835999.32768169
661954.139305085836464.605459467
#Sta/Elev= 30
 9786.99520.81489797.257514.32669807.267 506.7169827.288493.42419847.308483.6161
9867.329471.99669877.339467.44589887.349465.34519907.519463.93179958.882462.8472
9969.154461.0933  9989.7453.60799999.972453.224610010.24454.750810020.52461.2612
10030.79465.130710041.06464.303810092.43466.338810133.52466.753810164.33468.0351
10195.15467.655810252.32470.503510277.33470.492810308.15473.286910318.42474.8085
10328.69477.506510349.24485.905410359.51 492.07710369.79496.896210379.65497.7456
#Mann= 3 , 0 , 0
 9786.99    0.12       0 9786.99    0.12       010379.65    0.12       0
#XS Ineff= 2 , 0
       0                               0
Bank Sta=9786.99,10379.65
Exp/Cntr=0.3,0.1

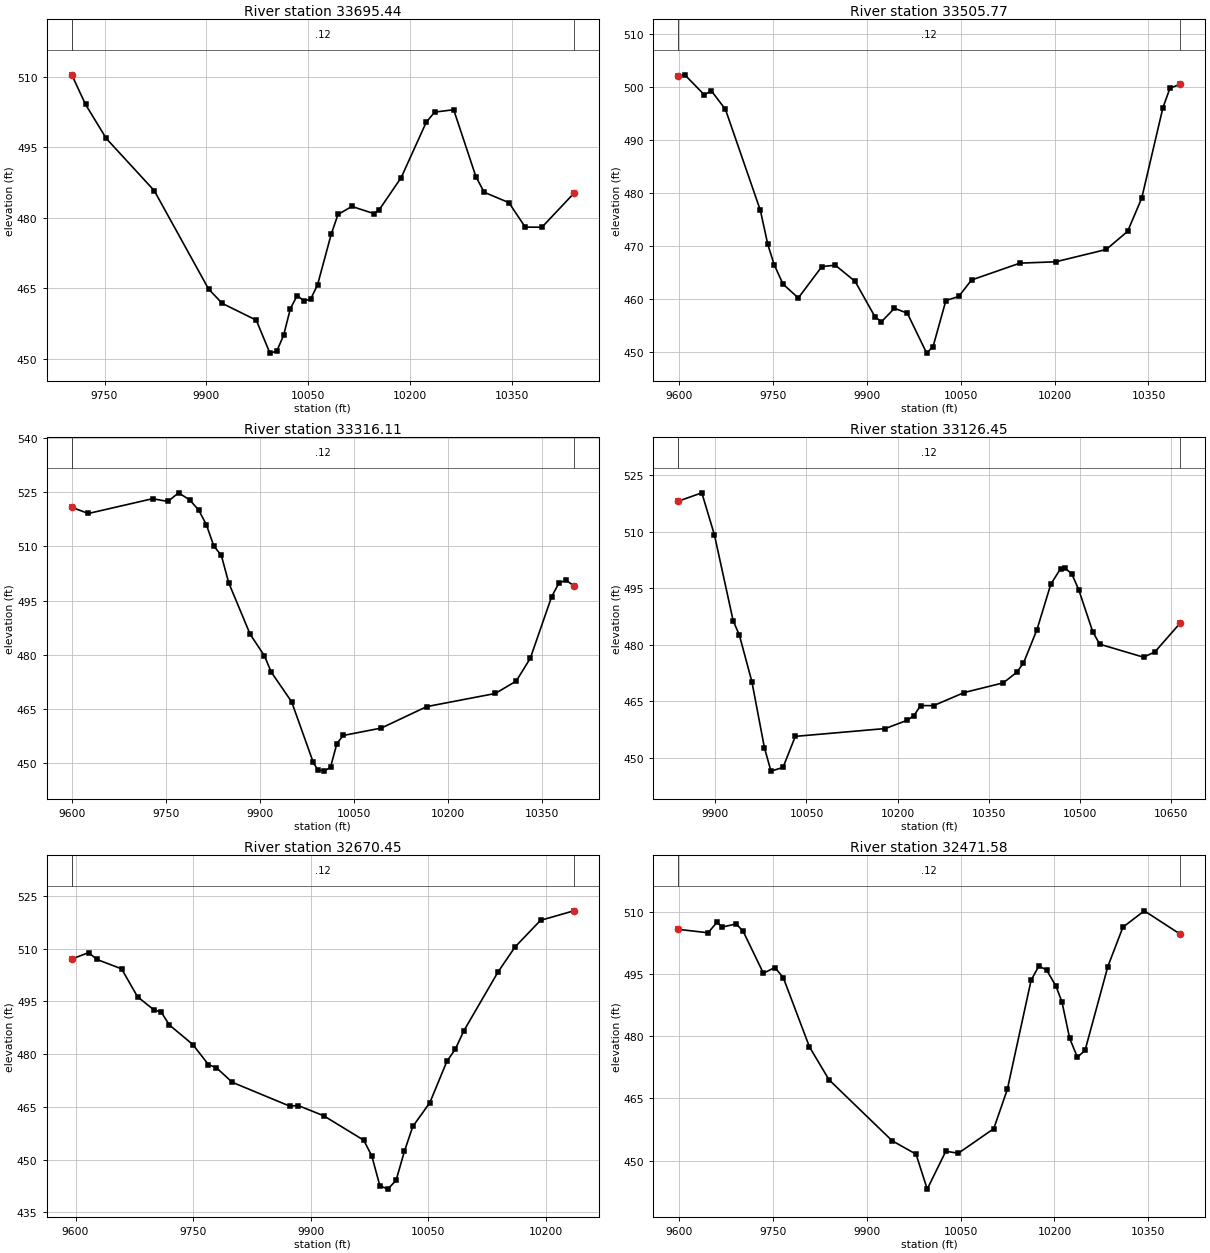
Type RM Length L Ch R = 1 ,33695.44,189.661700,189.661700,189.661700
XS GIS Cut Line= 6
661584.853035559835865.272881736661607.835221348836022.912737258
661595.886350701836233.853160615661610.415934058836299.891871708
661666.633017897836363.205077221661843.407700877836486.143264267
#Sta/Elev= 30
9701.746510.38259721.981504.11349752.564496.86489823.288485.77039903.392 464.864
9923.423461.82939973.591458.26539993.704451.260410003.77 451.67910013.81455.0076
10023.86460.7205 10033.9463.499310043.91462.331910053.91462.773810063.91465.7862
10083.96476.500110093.99 480.71110114.37482.423310146.68480.915410154.83 481.732
 10187.1488.549610224.01500.301110236.36502.459110264.46 502.96910297.19488.7626
10309.36485.443110345.85483.225910369.83478.033210394.51478.004610441.51485.2077
#Mann= 3 , 0 , 0
9701.746    0.12       09701.746    0.12       010441.51    0.12       0
#XS Ineff= 2 , 0
       0                               0
Bank Sta=9701.746,10441.51
Exp/Cntr=0.3,0.1

Type RM Length L Ch R = 1 ,33505.77,189.661800,189.661800,189.661800
XS GIS Cut Line= 6
661270.052336561835748.317074662661376.298890425835973.328006877
661435.918381131836197.184015435661454.969979019836241.347719776
661507.690487901836297.536531114661679.653929409836389.639420521
#Sta/Elev= 30
9599.026  502.049609.513 502.2789640.631498.51099651.972499.25759674.468495.7455
9730.254476.68649741.991470.31319752.246466.46099766.371462.79849790.784460.1859
9828.323466.09219849.835466.3703 9881.57463.30439913.077456.6659 9923.49455.6823
9944.298458.24049964.882457.31559995.757449.778810006.01451.019110026.49459.7012
10046.98460.468510067.47463.576110144.78466.754510201.78467.007410282.51469.3275
 10316.7472.749210339.24479.016210373.06496.068710384.34499.764310400.86500.5105
#Mann= 3 , 0 , 0
9599.026    0.12       09599.026    0.12       010400.86    0.12       0
#XS Ineff= 2 , 0
       0                               0
Bank Sta=9599.026,10400.86
Exp/Cntr=0.3,0.1

Type RM Length L Ch R = 1 ,33316.11,189.661700,189.661700,189.661700
XS GIS Cut Line= 6
 660975.63679301836047.785515395661103.212603337 836151.71550271
661224.822399359836226.417588992661297.959987508 836253.93125695
 661464.65987207836286.904927227661686.246453353836393.480376684
#Sta/Elev= 30
9599.099520.79639625.598 519.1069728.105523.19029752.692522.42979769.621524.8183
9787.638522.84349801.917520.01549813.939516.03899825.961510.11019837.982507.4933
 9849.74499.93579883.952485.7057 9906.75479.74449917.635475.25429950.264466.9995
9984.801450.23949992.002448.1848 10002.2447.842310012.34448.925310022.48455.4784
10032.62457.702410093.47459.756810166.02465.690910275.49469.318610308.96472.7645
10331.32479.037610365.42496.056910376.79499.765410388.15 500.71410400.93499.0683
#Mann= 3 , 0 , 0
9599.099    0.12       09599.099    0.12       010400.93    0.12       0
#XS Ineff= 2 , 0
       0                               0
Bank Sta=9599.099,10400.93
Exp/Cntr=0.3,0.1

Type RM Length L Ch R = 1 ,33126.45,456.000000,456.000000,456.000000
XS GIS Cut Line= 6
661097.814164228836397.379346866661303.132362069836438.693904166
661454.629644589836330.027575961661531.116412508836321.219046603
661639.104549089836368.169071578661836.289663816 836488.71366654
#Sta/Elev= 30
9839.106518.14169877.886520.36589898.595509.21339929.455486.38649939.724482.5365
 9960.26470.18739980.796452.71449991.582446.459210011.48447.449410031.63455.6888
10179.71457.769210215.07459.930310226.41 461.13310237.72463.872410258.94463.8445
10309.47467.332510373.65469.8986 10395.8472.702110406.87475.150810429.01484.0001
10451.81 496.08810467.79500.196210474.78500.407510486.27498.875510497.75494.6485
10520.72483.5211 10532.2480.171310604.37476.716710622.94 478.10610664.82485.8064
#Mann= 3 , 0 , 0
9839.106    0.12       09839.106    0.12       010664.82    0.12       0
#XS Ineff= 2 , 0
       0                               0
Bank Sta=9839.106,10664.82
Exp/Cntr=0.3,0.1

Type RM Length L Ch R = 1 ,32670.45,198.872300,198.872300,198.872300
XS GIS Cut Line= 6
661035.235684323836629.465922465661091.885187249836650.132966002
661187.263887189836661.628637544661250.946957208836653.811832079
661392.623592654 836612.38841302661644.112402383 836710.53259921
#Sta/Elev= 30
9595.225507.02559616.754508.84099627.287506.90569658.784504.22799679.192496.2858
 9699.56492.64219709.624491.87019719.666488.29119749.682 482.7089769.729476.9755
9779.756476.11929799.998471.97049873.301465.19429884.164465.35649916.752462.4433
9967.951455.47689978.184450.97689988.418442.54459998.682441.577710009.19444.1131
10019.72 452.29710030.46459.3911 10052.2466.157510073.94477.908210084.81481.4182
10095.68486.628810139.16503.303210160.89510.4246 10193.5518.026210236.02520.7298
#Mann= 3 , 0 , 0
9595.225    0.12       09595.225    0.12       010236.02    0.12       0
#XS Ineff= 2 , 0
       0                               0
Bank Sta=9595.225,10236.02
Exp/Cntr=0.3,0.1

Type RM Length L Ch R = 1 ,32471.58,198.872400,198.872400,198.872400
XS GIS Cut Line= 6
660974.354759128836612.369225592661070.162112377836665.099487889
661213.385598732836711.195221696661268.335434287836737.255796204
 661443.50314098836883.582591538661651.297327294837026.888465906
#Sta/Elev= 30
9599.137505.72529646.773504.89499660.753507.39549669.694506.29099691.847507.0291
9702.924505.22299735.135495.14099753.395496.52499766.848494.10379808.626477.4115
 9839.96469.4601 9940.71454.76679978.939451.52849996.781443.104510026.47452.2354
10046.48451.7606   10103 457.67210124.73467.153510162.67493.444410174.98496.8713
10187.29495.949310202.35492.042810211.92 488.25110224.24479.458410236.62474.8946
10248.86 476.56910285.24496.765810309.27506.238610343.47510.187610400.97 504.545
#Mann= 3 , 0 , 0
9599.137    0.12       09599.137    0.12       010400.97    0.12       0
#XS Ineff= 2 , 0
       0                               0
Bank Sta=9599.137,10400.97
Exp/Cntr=0.3,0.1

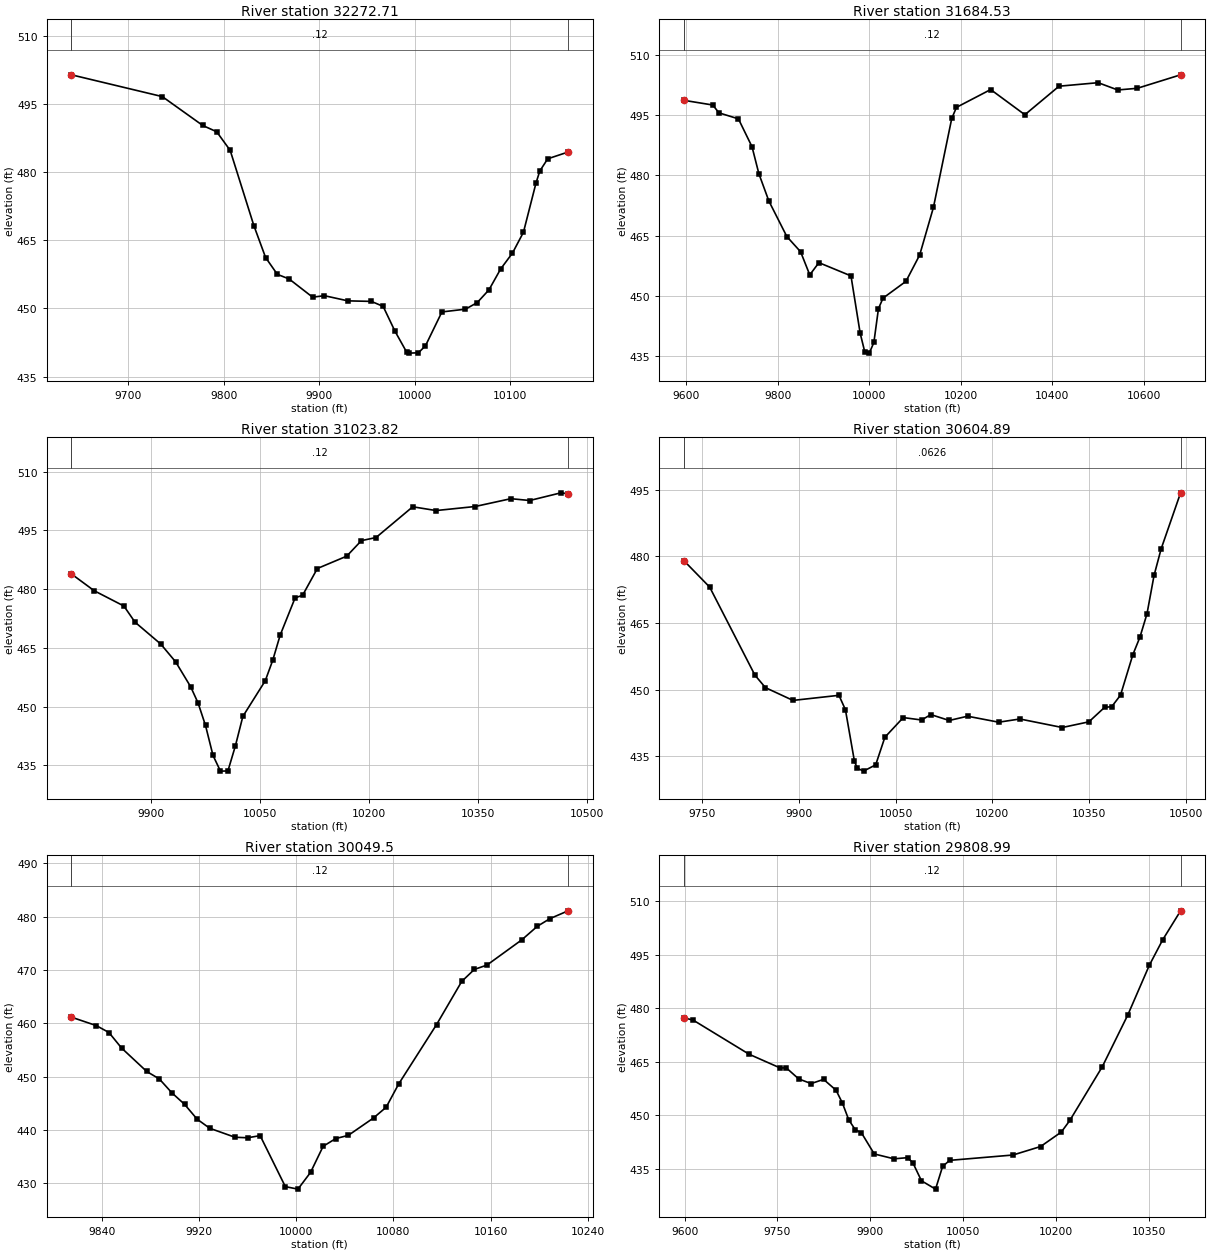
Type RM Length L Ch R = 1 ,32272.71,588.178800,588.178800,588.178800
XS GIS Cut Line= 5
660940.663223475836697.284716353660960.817796826836728.133316129
660978.110846072836758.418014735661045.837677121836826.144845769
661332.296010464837032.308040202
#Sta/Elev= 30
9640.333501.48999735.507496.69179777.933490.3231 9792.51488.94149806.652484.8383
9831.446468.27439843.766461.22449856.087457.51529868.408456.50029893.049452.4828
9905.369 452.813 9930.01451.67379954.652451.55349966.972450.45459979.293445.0132
9991.613440.36699994.187440.152410003.93440.227710011.31441.762510028.57449.2323
10053.22449.840210065.54451.284210077.86454.098210090.18458.7177 10102.5462.2004
10114.02466.792910127.14477.620810131.14480.286510139.46482.979610160.77484.4711
#Mann= 3 , 0 , 0
9640.333    0.12       09640.333    0.12       010160.77    0.12       0
#XS Ineff= 2 , 0
       0                               0
Bank Sta=9640.333,10160.77
Exp/Cntr=0.3,0.1

Type RM Length L Ch R = 1 ,31684.53,660.704300,660.704300,660.704300
XS GIS Cut Line= 4
660695.143232703836708.523317993660819.694134921836845.665528774
660810.176624477837250.159724593661273.702260464837422.933040217
#Sta/Elev= 30
9595.427498.7154 9658.21497.55029671.718495.59739714.207494.10029743.955487.1376
9758.829 480.4469780.686473.61849820.031464.74649850.039460.95539870.045455.1953
 9890.05458.2427 9960.07454.94219980.075440.68879990.078 436.04110000.08435.6846
10010.08438.354610020.09446.783810030.09449.4044 10080.1453.581310110.11460.1507
10140.12 472.00510180.13494.188410190.44496.964510265.14501.405810339.85495.1268
10414.55502.240110499.93503.117910542.62501.302810585.31501.716410679.97505.0772
#Mann= 3 , 0 , 0
9595.427    0.12       09595.427    0.12       010679.97    0.12       0
#XS Ineff= 2 , 0
       0                               0
Bank Sta=9595.427,10679.97
Exp/Cntr=0.3,0.1

Type RM Length L Ch R = 1 ,31023.82,418.931600,418.931600,418.931600
XS GIS Cut Line= 5
660398.268232733837093.939984649660462.635162741837195.831874043
660661.918234825837244.229191512660806.254343808837265.814984649
661004.171010464837343.939984649
#Sta/Elev= 30
9790.262 483.8859821.591479.60849862.485475.70529877.762471.59379913.216466.0057
9933.797461.44919954.378455.12699964.669450.9672 9974.96445.1968 9985.25437.5663
9995.541433.541810005.83433.583910016.12439.985610026.41447.512610057.29456.6169
10067.58 461.84510077.87468.287810098.45477.801810108.74478.450310129.09485.2896
10169.53 488.44110189.75492.402710209.97493.202610260.53501.0535 10292.7500.0914
10346.46501.121510395.76503.121210421.71502.657510464.72504.617410474.58 504.386
#Mann= 3 , 0 , 0
9790.262    0.12       09790.262    0.12       010474.58    0.12       0
#XS Ineff= 2 , 0
       0                               0
Bank Sta=9790.262,10474.58
Exp/Cntr=0.3,0.1

Type RM Length L Ch R = 1 ,30604.89,555.389000,555.389000,555.389000
XS GIS Cut Line= 3
660316.671010494837793.592762426660662.157121569837453.314984649
660922.573788285837336.995540217
#Sta/Elev= 30
9721.958478.99979761.721473.08779831.901453.2883 9848.21450.48029890.962447.6057
9962.216448.7507 9972.26445.52069986.296433.89069990.718432.363810000.33431.7042
10019.22433.119210033.47439.324110061.97443.746710090.47   443.210104.72444.4223
10133.23 443.09510161.73444.051510209.99442.706910242.85443.428110308.56441.5119
10349.87442.788710374.28446.054310385.23446.189410398.91448.788310418.09457.9049
10429.04461.829210439.99467.086810450.94475.7116 10461.9481.671610492.09 494.284
#Mann= 3 , 0 , 0
9721.958  0.0626       09721.958  0.0626       010492.09  0.0626       0
#XS Ineff= 2 , 0
       0                               0
Bank Sta=9721.958,10492.09
Exp/Cntr=0.3,0.1

Type RM Length L Ch R = 1 , 30049.5,240.514400,240.514400,240.514400
XS GIS Cut Line= 2
660615.282121569837852.620540202661009.379343808837744.981651336
#Sta/Elev= 30
9815.161461.16449835.602459.58859845.968458.29099856.334455.39089877.067450.9901
9887.433449.58829897.799446.97929908.166444.83789918.532442.04979928.898440.3463
9949.631438.66649959.997438.56439970.363438.96669991.096429.409510001.46428.9409
10011.83432.074410022.19436.969510032.56438.413710042.93439.021910063.66442.2818
10074.03444.286510084.39448.667310115.49 459.77510136.22467.869710146.59470.1176
10156.96470.929610185.67475.670110198.42478.201310208.79479.634710223.69481.0988
#Mann= 3 , 0 , 0
9815.161    0.12       09815.161    0.12       010223.69    0.12       0
#XS Ineff= 2 , 0
       0                               0
Bank Sta=9815.161,10223.69
Exp/Cntr=0.3,0.1

Type RM Length L Ch R = 1 ,29808.99,240.514400,240.514400,240.514400
XS GIS Cut Line= 6
660370.089804776837983.925887056660546.504391113837975.405988097
660672.330087881837994.964417904660732.727836558838019.096081438
660957.224172961838136.729574709661121.796264235838206.809380603
#Sta/Elev= 30
9599.101477.3075 9614.05476.63789704.282 467.1079754.303463.28679764.303 463.297
 9784.32460.21039804.361458.91499824.471460.08549844.633457.05149854.887453.4582
 9865.15448.75649875.414446.07219885.677445.12629906.293439.23789938.217437.8747
9960.102438.20239968.558436.80199982.498431.738410005.27429.404110016.69435.7649
 10028.1437.448710130.25438.939810174.91441.315210208.41445.372510222.06448.5912
 10274.4463.5864 10315.8478.121210350.61492.036110372.13499.132810400.97507.2118
#Mann= 3 , 0 , 0
9599.101    0.12       09599.101    0.12       010400.97    0.12       0
#XS Ineff= 2 , 0
       0                               0
Bank Sta=9599.101,10400.97
Exp/Cntr=0.3,0.1

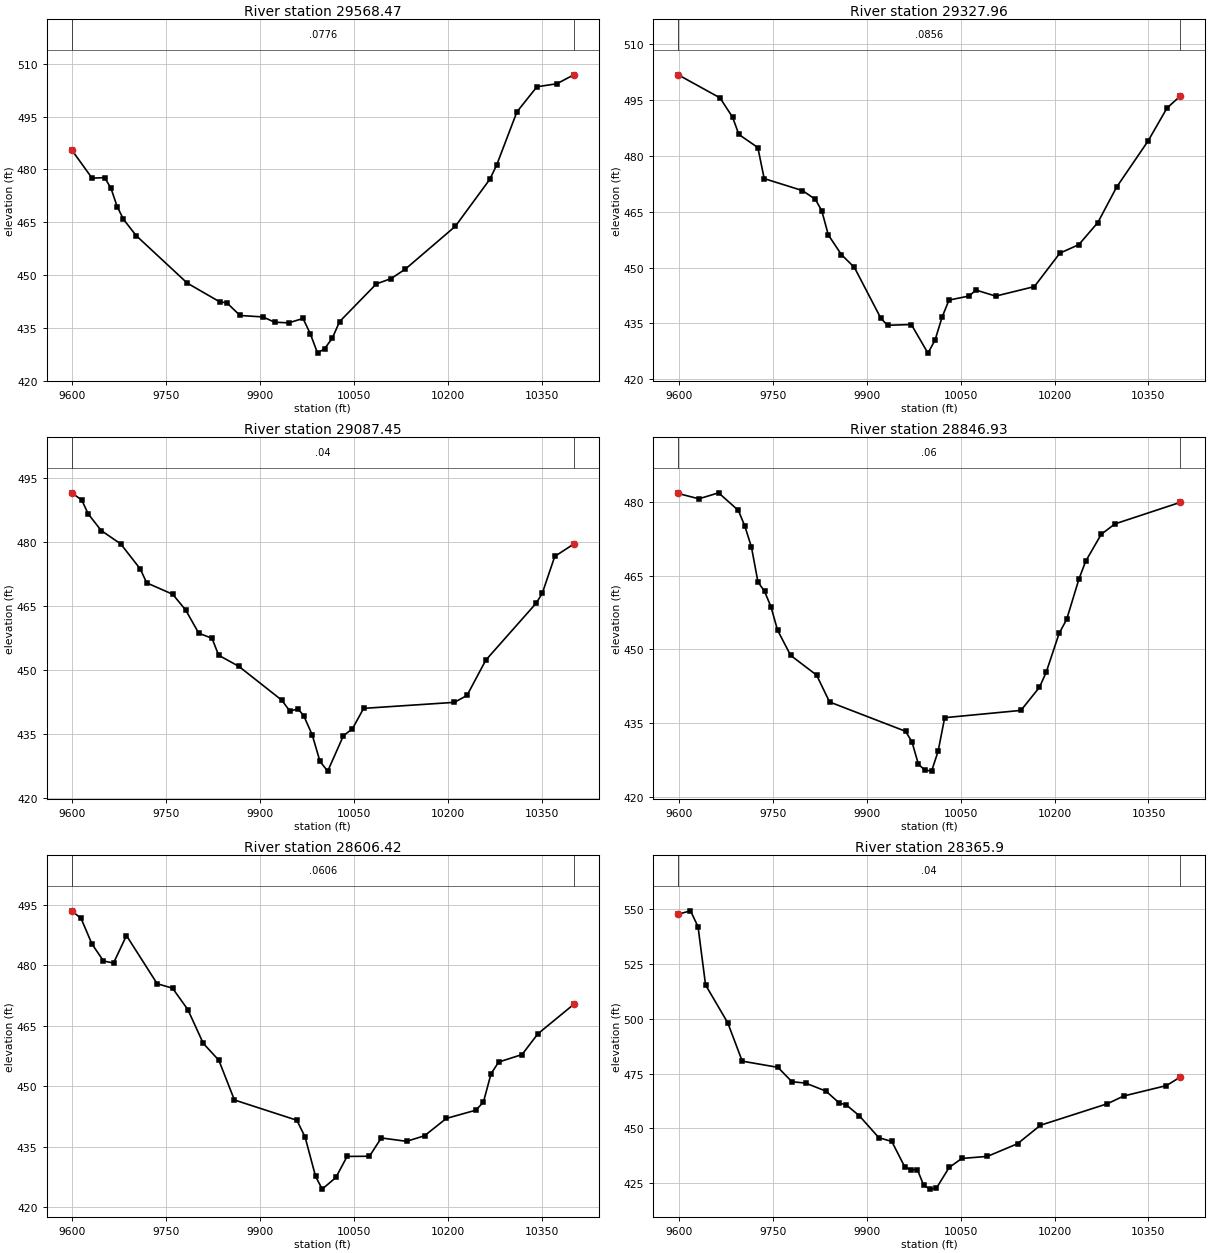
Type RM Length L Ch R = 1 ,29568.47,240.514400,240.514400,240.514400
XS GIS Cut Line= 6
660262.711341606838130.586713722660412.349381079838148.248484845
660520.672912271 838180.67473329660602.923235428838220.327855348
660819.691090801838347.521905337661001.121248784838418.624179351
#Sta/Elev= 30
9599.089485.51129631.486 477.5029651.553477.65319661.587474.68329671.621469.4171
9681.654465.81059701.911461.18459783.546447.68329835.888442.30619846.475442.1369
9867.794438.48639904.472438.07299922.966436.57629945.499436.39749968.438437.6367
 9980.04 433.3089991.642427.792210002.91429.070110015.06431.9966 10026.8436.7401
10085.52447.453710109.01448.963110132.04451.685910211.71463.8313 10266.8477.1804
10277.67481.213610310.07496.335610341.96503.461410373.67504.315510400.97506.8572
#Mann= 3 , 0 , 0
9599.089  0.0776       09599.089  0.0776       010400.97  0.0776       0
#XS Ineff= 2 , 0
       0                               0
Bank Sta=9599.089,10400.97
Exp/Cntr=0.3,0.1

Type RM Length L Ch R = 1 ,29327.96,240.514400,240.514400,240.514400
XS GIS Cut Line= 6
660158.474378032838368.322617541660267.026872274838377.099984139
660382.407442776838399.608729148660620.124914174838488.660003123
660692.221683565838508.877283921660936.094041636838540.757367214
#Sta/Elev= 30
9599.048501.8456 9665.71495.65499685.828490.45429695.887  485.81 9726.19482.2909
9736.319 473.9439797.491470.71919818.004 468.3779828.305465.2871 9838.73  458.81
 9859.58453.5201 9880.43450.05469922.757436.35439933.339434.4971 9971.33434.7139
9997.859427.017610009.17430.503310020.39436.664310031.49 441.277 10063.7442.3776
10074.44443.983110106.02442.348710167.86444.906910208.53453.894110238.83456.1828
10269.14462.111610299.31471.683310349.57484.088410379.73492.928210400.94496.1418
#Mann= 3 , 0 , 0
9599.048  0.0856       09599.048  0.0856       010400.94  0.0856       0
#XS Ineff= 2 , 0
       0                               0
Bank Sta=9599.048,10400.94
Exp/Cntr=0.3,0.1

Type RM Length L Ch R = 1 ,29087.45,240.514400,240.514400,240.514400
XS GIS Cut Line= 6
660129.635623187838817.392340968660407.251360064838731.368510928
660518.784446287838626.010574175660563.694562566838602.515793711
660687.984928732 838578.72698674660865.470271749838573.252435863
#Sta/Elev= 30
 9599.12491.52789615.054489.83179625.424486.57079646.164 482.6859677.275479.5607
9708.386473.71259718.756470.43039760.237467.76739780.978464.06939801.926458.6299
9823.048457.44919833.609453.47999865.876450.87039934.464442.9429 9947.27 440.397
9960.514440.88099969.482439.3092 9983.07 434.8059995.498428.581110007.79426.3227
10032.87434.613810047.34436.259810065.14441.027510210.06 442.438 10230.2444.0504
10260.27452.333110340.34465.612810350.34467.958910370.34476.633510400.81479.5413
#Mann= 3 , 0 , 0
 9599.12    0.04       0 9599.12    0.04       010400.81    0.04       0
#XS Ineff= 2 , 0
       0                               0
Bank Sta=9599.12,10400.81
Exp/Cntr=0.3,0.1

Type RM Length L Ch R = 1 ,28846.93,240.514400,240.514400,240.514400
XS GIS Cut Line= 6
660223.607641439838905.843365601660518.034316373838824.515739986
660705.274387729838858.622701442660795.442527653 838853.54074808
660877.018448759838825.529422302660988.010741664838763.222475586
#Sta/Elev= 30
9599.094481.74479632.048480.66119663.541481.88029695.035478.30519705.532475.0774
9715.981470.83579726.414463.71169736.846461.82969747.278458.62459757.711453.8912
9778.575448.7724 9820.08444.74149840.714439.27479962.062433.30269972.344431.1426
9982.628426.56489993.124425.391410003.64 425.18810014.09429.250310024.55436.0735
10146.28437.558510175.95442.276210186.63445.322510207.36453.272610219.28456.0814
10238.96464.318810249.73467.960810274.62473.441510296.35475.546310400.81479.9433
#Mann= 3 , 0 , 0
9599.094    0.06       09599.094    0.06       010400.81    0.06       0
#XS Ineff= 2 , 0
       0                               0
Bank Sta=9599.094,10400.81
Exp/Cntr=0.3,0.1

Type RM Length L Ch R = 1 ,28606.42,240.514400,240.514400,240.514400
XS GIS Cut Line= 6
660283.731973988839293.594195639660457.487324119 839170.34835011
660648.450403877839028.315677131660818.739069668838925.843724725
660861.324630936838895.921903257660940.391411424838834.555324362
#Sta/Elev= 30
9599.013493.53429613.868491.64889631.153 485.3349649.609481.08059665.722480.5647
9686.389487.3855 9735.43475.4224 9759.95474.3284 9784.47 468.9869808.991460.6311
9833.876456.43039858.813446.55579958.562441.52039971.671 437.3539988.413427.5926
    9999424.415710020.86427.309410038.79432.538310074.51432.581810093.39437.1272
10133.78 436.28910162.46437.669310197.23441.969410244.42444.024810256.49446.0069
10268.71453.069610280.93455.975710318.19457.836810343.51462.986510400.97470.3242
#Mann= 3 , 0 , 0
9599.013  0.0606       09599.013  0.0606       010400.97  0.0606       0
#XS Ineff= 2 , 0
       0                               0
Bank Sta=9599.013,10400.97
Exp/Cntr=0.3,0.1

Type RM Length L Ch R = 1 , 28365.9,240.514400,240.514400,240.514400
XS GIS Cut Line= 6
660657.848438635839531.275345678660728.727732453839417.297918304
660777.110264981839310.889632682660862.698124806 838986.14099975
660909.008606361838913.328994553660994.564412629838819.123617399
#Sta/Elev= 30
9599.069547.80929618.653549.34449630.686542.08669642.719515.48639678.111498.2409
9701.271480.69679758.245477.87499780.574471.31719802.555470.67739835.033467.0155
 9856.52461.51239867.065460.81099888.157455.79249919.445445.75299940.127444.0377
9960.586432.53769970.766431.07349980.946431.21169991.127423.967610001.29422.2664
10011.43422.7204 10031.7432.144910051.97436.273210092.86437.218610140.89442.9932
10177.56451.435810284.44461.252410310.55464.791310378.81469.551410400.91473.4401
#Mann= 3 , 0 , 0
9599.069    0.04       09599.069    0.04       010400.91    0.04       0
#XS Ineff= 2 , 0
       0                               0
Bank Sta=9599.069,10400.91
Exp/Cntr=0.3,0.1

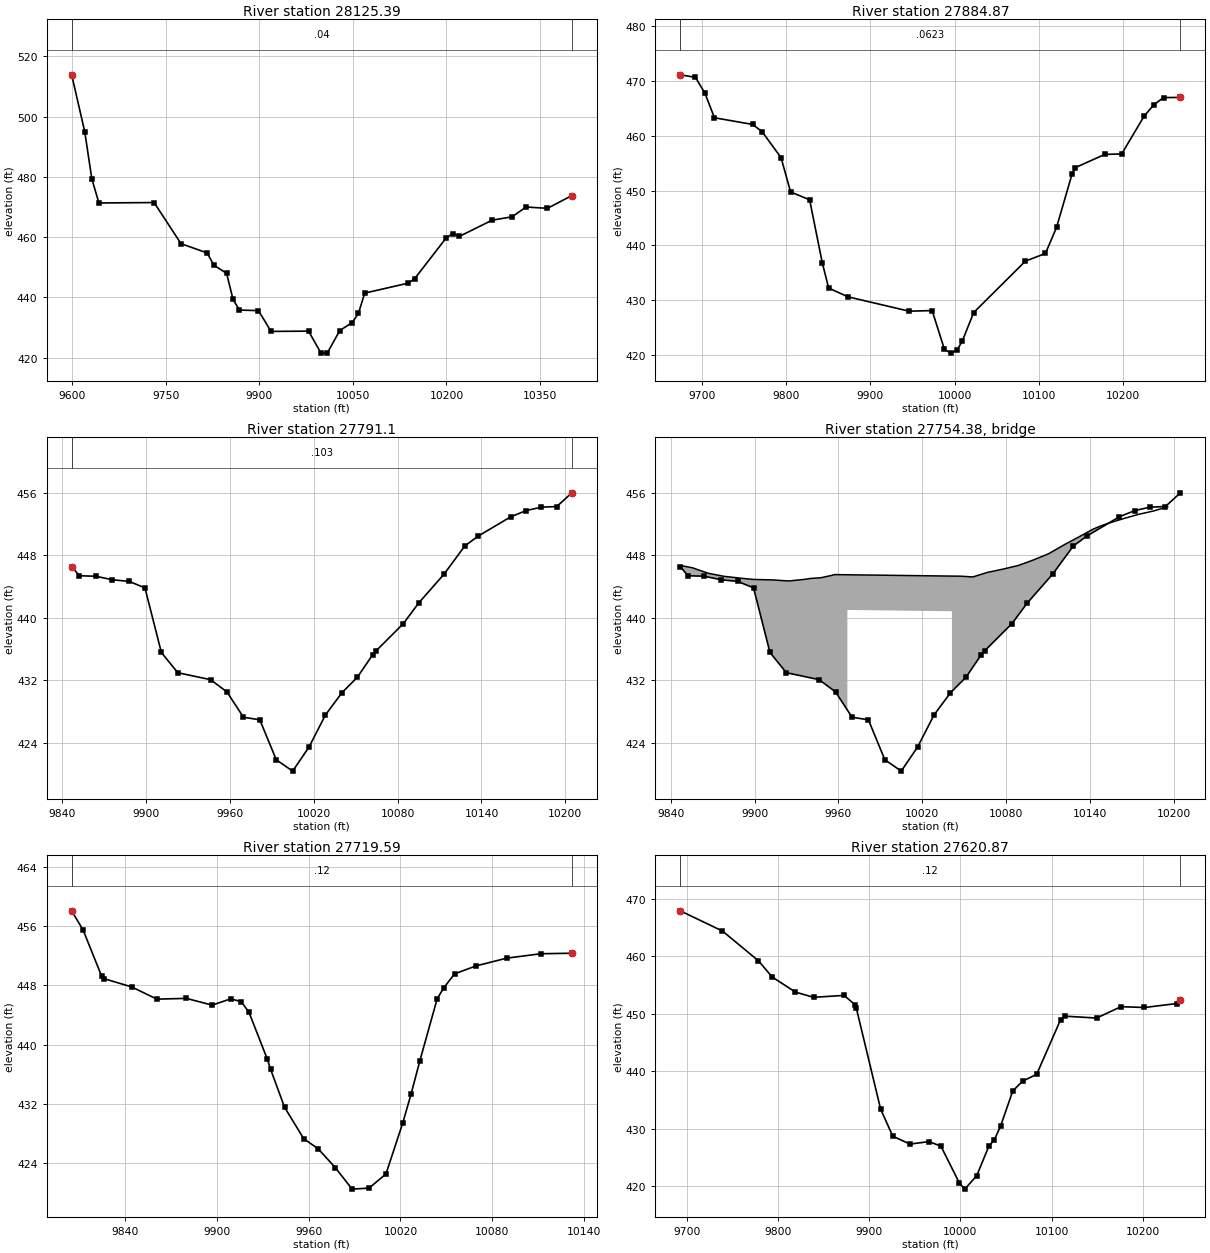
Type RM Length L Ch R = 1 ,28125.39,240.514400,240.514400,240.514400
XS GIS Cut Line= 6
660942.596361991839573.467443135661034.472510308839360.664368352
 661051.96498561839266.591331939661063.555303503839007.366356802
661097.279726508838899.040491835661147.099522917838812.409687004
#Sta/Elev= 30
 9599.08513.88019620.047494.99259631.401 479.3559642.754 471.3619731.291471.4935
9774.313457.8591  9816.4454.76439826.886450.73679847.505448.00139857.765439.3543
9868.026435.81779898.552435.63089918.733428.73599978.852428.82849998.854421.5297
10008.86421.552210028.86429.004310048.87431.688310058.87434.742510068.87441.4488
10139.02444.769710149.12446.287910199.95459.876810210.27461.210110220.59460.2609
10273.05465.634810305.32466.779310327.52470.016210361.88469.581910400.92 473.804
#Mann= 3 , 0 , 0
 9599.08    0.04       0 9599.08    0.04       010400.92    0.04       0
#XS Ineff= 2 , 0
       0                               0
Bank Sta=9599.08,10400.92
Exp/Cntr=0.3,0.1

Type RM Length L Ch R = 1 ,27884.87,93.773300,93.773300,93.773300
XS GIS Cut Line= 6
661095.908441394839530.560366169661214.159971309839315.053575766
 661238.15926893839285.052228386 661293.80002855839233.318316388
661322.748276284839198.290090207661420.478918586839037.764468503
#Sta/Elev= 30
9674.174471.15329692.158470.69719703.456467.80319714.755463.30589759.948462.0886
9771.246460.77999793.843456.01219805.141449.74219827.738448.31519842.738436.8145
9850.334432.1776  9873.4430.57139945.761427.95299973.172428.05939987.767420.9753
9995.349420.284410002.48420.777410008.91422.466810022.51427.705710083.84437.0938
10107.67438.505910120.85443.257710139.24453.009510143.32454.208910178.17456.6091
10198.17456.692310224.64 463.55510236.25465.674310247.87466.993610267.89467.0226
#Mann= 3 , 0 , 0
9674.174  0.0623       09674.174  0.0623       010267.89  0.0623       0
#XS Ineff= 2 , 0
       0                               0
Bank Sta=9674.174,10267.89
Exp/Cntr=0.3,0.1

Type RM Length L Ch R = 1 , 27791.1,71.509900,71.509900,71.509900
XS GIS Cut Line= 3
661263.401757926839439.662824854661365.674659044839273.349882856
661432.582164466839125.197549477
#Sta/Elev= 30
9846.843446.53679852.317445.36179864.057445.30259875.796444.85649888.075444.6334
9899.275443.81159911.014435.54819922.754432.96379946.233432.07149957.972430.4974
9969.712427.27259981.451426.93699993.191421.835210004.93420.375410016.67 423.467
10028.41427.565810040.15 430.39410051.25432.386910062.22435.270910064.74435.7808
10084.17  439.2510095.14441.888110113.34445.588110128.06449.167110137.63450.4314
10160.97452.902910171.95453.695510182.92454.137310193.89454.214210204.65455.9689
#Mann= 3 , 0 , 0
9846.843   0.103       09846.843   0.103       010204.65   0.103       0
#XS Ineff= 2 , 0
       0                               0
Bank Sta=9846.843,10204.65
Exp/Cntr=0.3,0.1

Type RM Length L Ch R = 3 ,27754.38,,,
BEGIN DESCRIPTION:
END DESCRIPTION:
Bridge Culvert--1,0,-1,-1, 0
Deck Dist Width WeirC Skew NumUp NumDn MinLoCord MaxHiCord MaxSubmerge Is_Ogee
25.584350,20.341200,2.6,0, 41, 41, , , 0.95, 0, 0,0,,
 9847.51 9855.67 9859.04 9867.19 9878.71 9879.19 9890.23 9899.35 9901.74 9913.26
 9919.50 9924.78 9936.30 9939.66 9947.81 9955.39 9957.07 9966.39 9966.3910041.19
10041.1910047.2510056.1310066.9110068.1710077.6910088.4810094.9010099.2610110.04
10120.8310121.6210131.6110142.3910148.3510153.1810163.9610174.7410175.0810185.52
10195.54
  446.66  446.38  446.16  445.67  445.27  445.27  445.05  444.89  444.88  444.83
  444.75  444.70  444.91  445.01  445.12  445.42  445.51  445.49  445.49  445.32
  445.32  445.31  445.21  445.81  445.85  446.21  446.67  447.08  447.37  448.15
  449.25  449.34  450.29  451.34  451.78  452.08  452.67  453.22  453.23  453.65
  454.18
 -553.34 -553.62 -553.84 -554.33 -554.73 -554.73 -554.95 -555.11 -555.12 -555.17
 -555.25 -555.30 -555.09 -554.99 -554.88 -554.58 -554.49 -554.51  440.99  440.82
 -554.68 -554.69 -554.79 -554.19 -554.15 -553.79 -553.33 -552.92 -552.63 -551.85
 -550.75 -550.66 -549.71 -548.66 -548.22 -547.92 -547.33 -546.78 -546.77 -546.35
 -545.82
 9847.51 9855.67 9859.04 9867.19 9878.71 9879.19 9890.23 9899.35 9901.74 9913.26
 9919.50 9924.78 9936.30 9939.66 9947.81 9955.39 9957.07 9963.11 9963.1110037.91
10037.9110047.2510056.1310066.9110068.1710077.6910088.4810094.9010099.2610110.04
10120.8310121.6210131.6110142.3910148.3510153.1810163.9610174.7410175.0810185.52
10195.54
  446.66  446.38  446.16  445.67  445.27  445.27  445.05  444.89  444.88  444.83
  444.75  444.70  444.91  445.01  445.12  445.42  445.51  445.50  445.50  445.33
  445.33  445.31  445.21  445.81  445.85  446.21  446.67  447.08  447.37  448.15
  449.25  449.34  450.29  451.34  451.78  452.08  452.67  453.22  453.23  453.65
  454.18
 -553.34 -553.62 -553.84 -554.33 -554.73 -554.73 -554.95 -555.11 -555.12 -555.17
 -555.25 -555.30 -555.09 -554.99 -554.88 -554.58 -554.49 -554.50  441.00  440.83
 -554.67 -554.69 -554.79 -554.19 -554.15 -553.79 -553.33 -552.92 -552.63 -551.85
 -550.75 -550.66 -549.71 -548.66 -548.22 -547.92 -547.33 -546.78 -546.77 -546.35
 -545.82
BR Coef=-1 , 0 , 0 ,, 0 ,,,0.8,0,1,0,
WSPro=,,,, 1 ,,,, 0 ,,,, 0 ,,,,-1 ,-1 ,-1 , 0 , 0 , 0 , 0 , 0
BC Design=,, 0 ,, 0 ,,,,,,

Type RM Length L Ch R = 1 ,27719.59,98.716800,98.716800,98.716800
XS GIS Cut Line= 4
661313.104476213 839491.27718617661385.746910691839383.269356012
661425.891413897839298.201242015661474.638310671839207.398198962
#Sta/Elev= 30
9804.842458.03969812.407455.41139824.458449.21949826.157448.88119844.075447.7754
9860.612446.12859879.912446.22859896.766445.31699908.818446.16259915.749445.8001
9920.869444.3509 9932.92438.00459935.006436.6662 9944.15431.54319956.687427.3015
9966.265425.91559977.323423.4016 9988.38420.49859999.438420.6374 10010.5422.5403
10021.55429.455510026.98433.3595 10032.7437.820610044.05446.198310048.33447.6472
 10055.4449.537310069.47 450.61110089.45451.652210111.75452.249510132.13452.3198
#Mann= 3 , 0 , 0
9804.842    0.12       09804.842    0.12       010132.13    0.12       0
#XS Ineff= 2 , 0
       0                               0
Bank Sta=9804.842,10132.13
Exp/Cntr=0.3,0.1

Type RM Length L Ch R = 1 ,27620.87,237.806800,237.806800,237.806800
XS GIS Cut Line= 6
661298.236084288839599.710320069 661465.24538495839410.603433665
661500.152441596839369.483516159661501.411751759839367.929766529
 661643.83092376839200.796832985661657.609150043839185.312168079
#Sta/Elev= 30
9692.765467.90789739.074464.38769778.517459.21269793.624456.38199819.123 453.761
9838.944452.85679872.489453.18879884.264451.5836 9885.83450.99699912.513433.3987
9925.854428.68299944.691427.31189965.529427.74319978.647426.9538    9999 420.498
10004.85419.475210017.99421.832210031.13426.913610037.37428.110410044.26 430.515
 10057.4436.5441 10068.2438.259210083.68439.460610109.95448.979710114.46449.5785
10149.37449.246910176.13451.226210201.92 451.08410237.38451.771810241.31452.3084
#Mann= 3 , 0 , 0
9692.765    0.12       09692.765    0.12       010241.31    0.12       0
#XS Ineff= 2 , 0
       0                               0
Bank Sta=9692.765,10241.31
Exp/Cntr=0.3,0.1