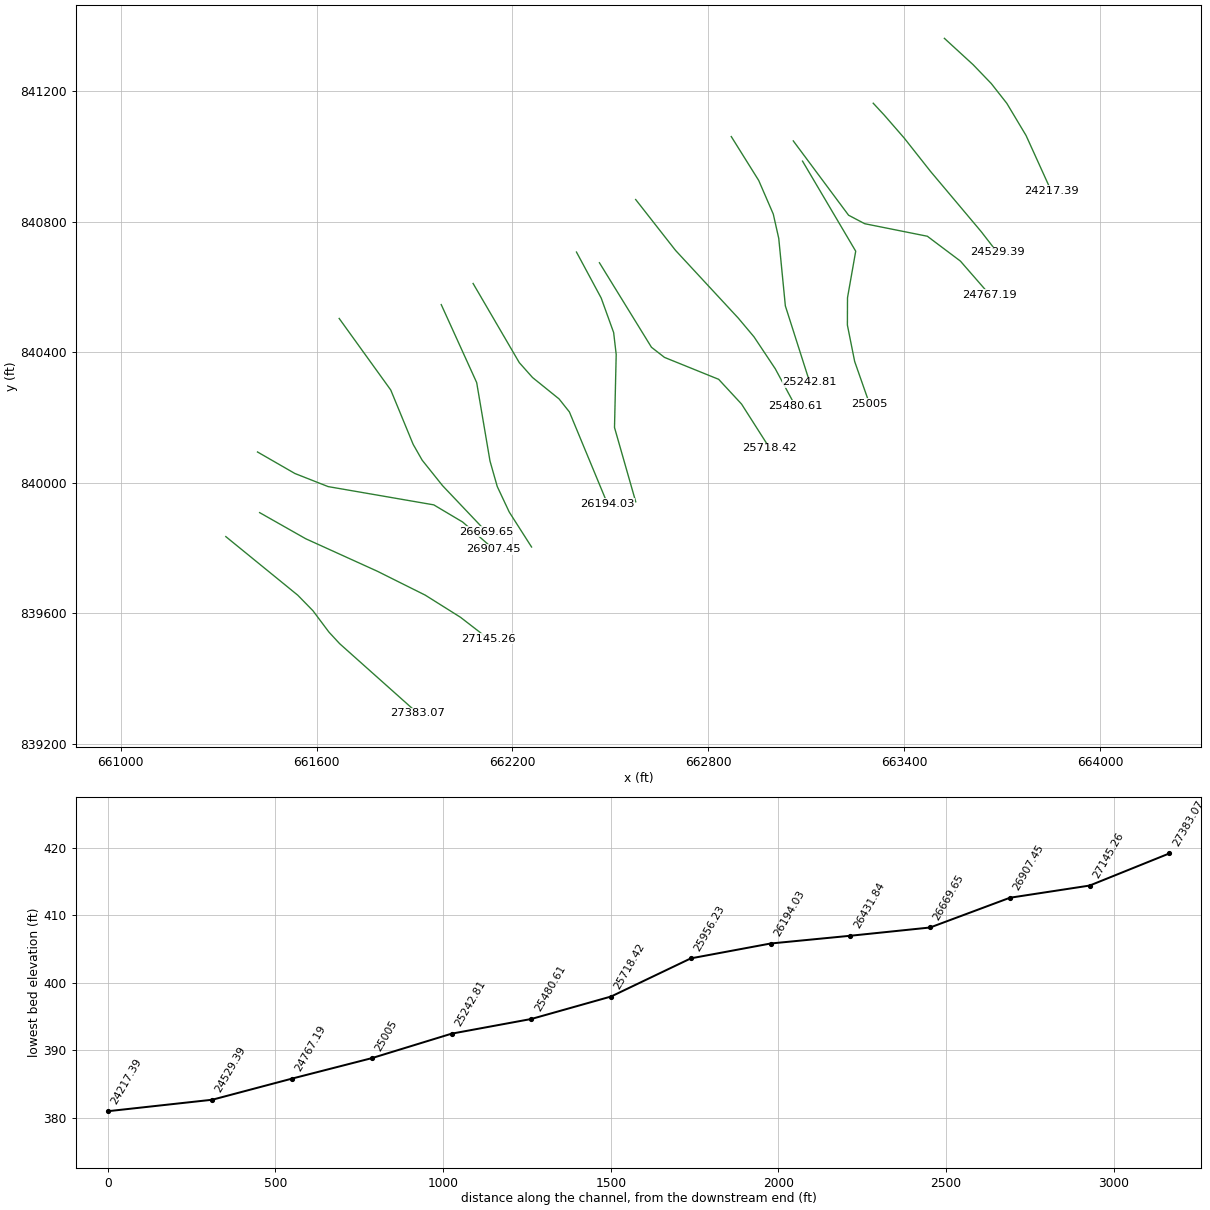
HEC-RAS study 13678_ras.prj: 13678

--- 13678_ras.g01 (geometry) --- (continued)

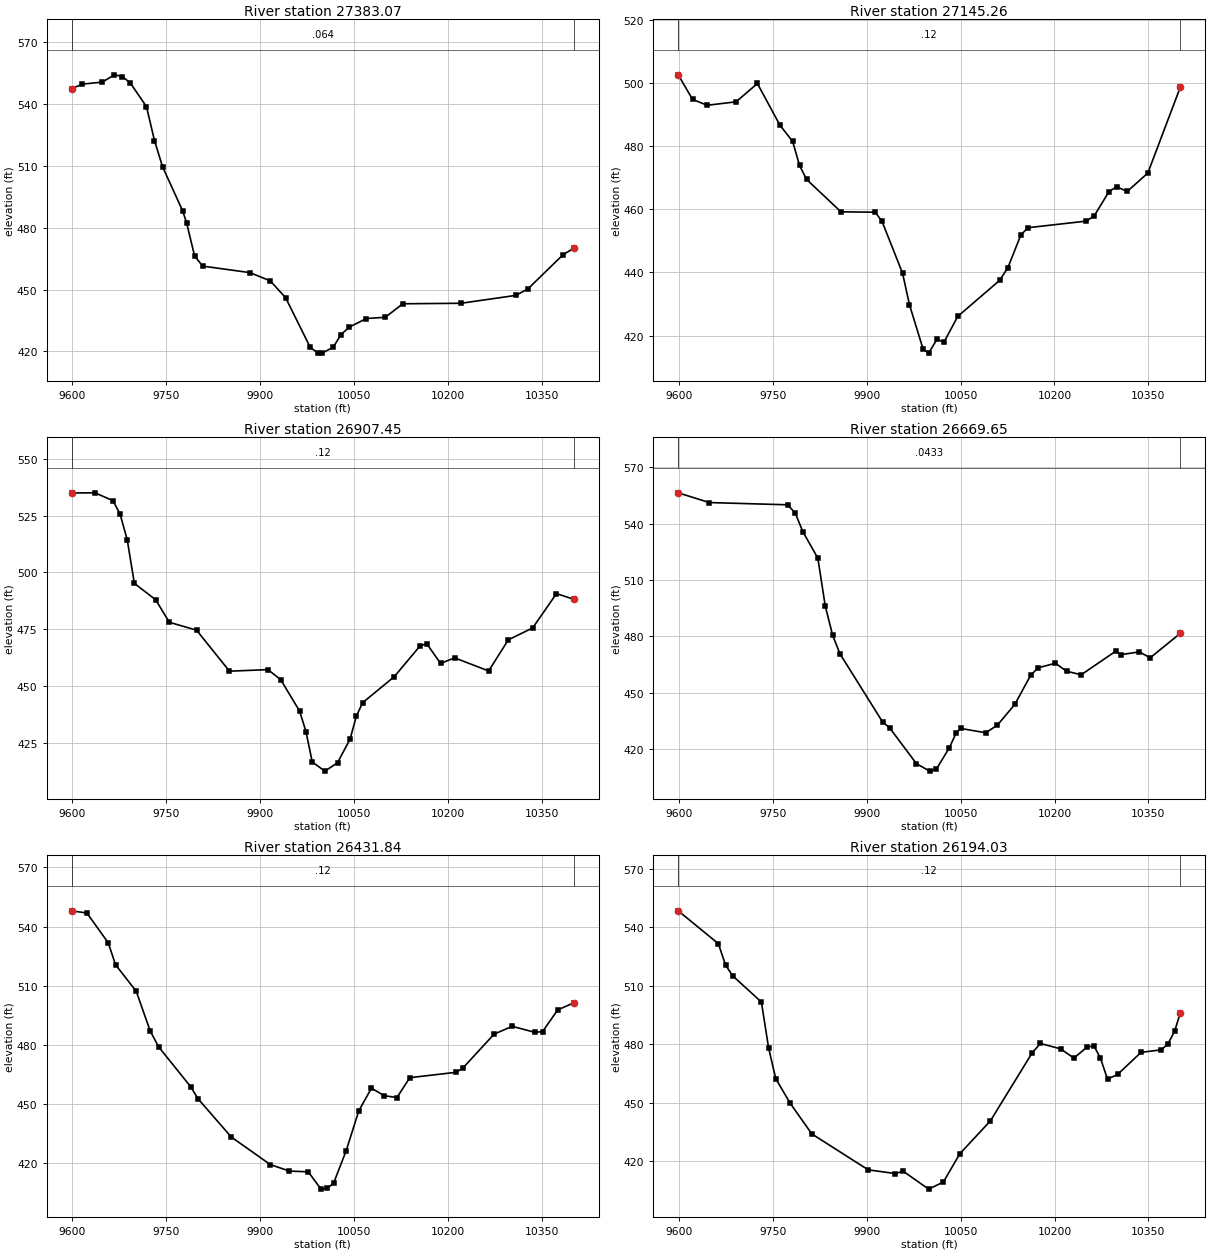
Type RM Length L Ch R = 1 ,27383.07,237.806700,237.806700,237.806700
XS GIS Cut Line= 6
661321.749416376839835.419991395661542.364489677839655.768450468
661588.783031773839608.224716072661637.526862547839543.100630134
661670.414947654839507.489016272  661909.9998313839293.808596568
#Sta/Elev= 30
9599.058 547.5049616.013549.71069647.813550.67489667.198554.21379679.994553.4009
9692.791550.14889718.383538.76379731.179522.28959743.975509.68779776.033 488.295
9782.364482.5249 9795.16466.40799808.088461.41299883.607458.25879916.009454.2617
9940.585446.1022 9979.87  422.049992.102419.2336    9999419.199310016.69422.0998
10029.08428.219710042.46431.851810069.69435.997110099.79436.5731 10127.7443.1396
10220.72 443.38610308.59447.227510327.53450.344710384.06467.036110400.95470.0608
#Mann= 3 , 0 , 0
9599.058   0.064       09599.058   0.064       010400.95   0.064       0
#XS Ineff= 2 , 0
       0                               0
Bank Sta=9599.058,10400.95
Exp/Cntr=0.3,0.1

Type RM Length L Ch R = 1 ,27145.26,237.806800,237.806800,237.806800
XS GIS Cut Line= 6
661425.452886745839908.886181024661566.628199303839828.858270382
  661785.5714208839729.514409028661932.855586027839656.046627281
662040.888808127839588.187969439662125.478929951839522.829035907
#Sta/Elev= 30
9599.033502.61119621.873494.82969645.242492.96379691.421494.0602 9725.47499.8631
9761.366486.67639781.732481.51269792.818473.88859803.903469.48729858.953459.2085
9913.648459.08279924.587 456.1519957.404439.70629968.343429.7653 9990.22415.6542
    9999414.428410012.29418.808510023.39417.8757 10045.6 426.09210112.38437.4736
10125.63441.534210146.26451.861410157.55454.168310251.01456.262610263.59457.9692
10286.99465.591810299.18467.164410316.12465.646910349.07471.479410400.97498.7048
#Mann= 3 , 0 , 0
9599.033    0.12       09599.033    0.12       010400.97    0.12       0
#XS Ineff= 2 , 0
       0                               0
Bank Sta=9599.033,10400.97
Exp/Cntr=0.3,0.1

Type RM Length L Ch R = 1 ,26907.45,237.806800,237.806800,237.806800
XS GIS Cut Line= 6
661418.840996917840094.742884598661533.434684857 840028.78119675
661635.402379508839988.613569895661958.892303714839932.687657349
 662047.49421386839880.025458994662143.227850828839796.144316656
#Sta/Elev= 30
9599.075534.9254 9636.26534.99239664.936531.5208 9676.23525.62629687.671514.3304
9699.039495.1729 9733.07487.95719754.892478.07229798.354474.59279850.947456.5682
9912.454457.24849932.734452.85069962.981438.99149973.063430.03429983.146416.6378
10003.32412.619210023.47416.294410043.57426.734210053.61436.840810063.66 442.735
10114.06454.134210155.52467.743810166.11468.6069 10188.1459.966610210.48462.4408
10264.82456.657510296.18470.342510335.17475.591210373.15490.6813 10400.9488.1717
#Mann= 3 , 0 , 0
9599.075    0.12       09599.075    0.12       0 10400.9    0.12       0
#XS Ineff= 2 , 0
       0                               0
Bank Sta=9599.075,10400.9
Exp/Cntr=0.3,0.1

Type RM Length L Ch R = 1 ,26669.65,237.806700,237.806700,237.806700
XS GIS Cut Line= 6
 661669.14382685840503.791594183661827.144952948 840284.54601444
661895.723118159840118.162170344661923.428431143840069.503690772
661985.700615232839991.690407697662120.012550278839850.114955841
#Sta/Elev= 30
9599.054556.40499648.678551.22219773.784550.02859785.904545.64719798.024535.7499
9822.024 521.6239833.777496.24479845.529480.71749857.282470.70359925.504434.3396
9936.487431.33639979.455412.1957 10000.6408.206310011.14409.145710032.24420.7703
10042.78428.454410049.99430.939710090.12428.641110108.67432.670410136.69443.7657
10162.04459.3336 10173.8463.213610201.42465.663710219.27461.421510242.55459.5091
10297.69472.056210306.45470.263210335.51471.698210352.83468.559110400.91481.5836
#Mann= 3 , 0 , 0
9599.054  0.0433       09599.054  0.0433       010400.91  0.0433       0
#XS Ineff= 2 , 0
       0                               0
Bank Sta=9599.054,10400.91
Exp/Cntr=0.3,0.1

Type RM Length L Ch R = 1 ,26431.84,237.806800,237.806800,237.806800
XS GIS Cut Line= 6
661981.819042591840546.272701826662090.403509407 840307.32420156
662131.207472931840066.951480411662153.379619661839989.028378193
662190.060026608839910.857342605662258.550286918839803.544168926
#Sta/Elev= 30
9599.053548.0004 9623.22546.87989657.302531.78629668.983520.6674 9702.02507.2423
9724.256487.1661 9737.88479.01719788.941458.89289800.587452.8077 9853.78433.4014
9916.034419.44699946.581 416.129 9976.85415.7589 9997.03406.9815 10007.1407.4351
10017.16409.9536 10037.3 426.43310057.43446.629610077.68458.133410097.95454.3374
10118.38453.386810138.93463.457310213.25466.1949 10224.1468.4597 10273.6485.5459
10302.65489.471210338.98486.408610351.02486.822810375.11497.762510400.94 501.408
#Mann= 3 , 0 , 0
9599.053    0.12       09599.053    0.12       010400.94    0.12       0
#XS Ineff= 2 , 0
       0                               0
Bank Sta=9599.053,10400.94
Exp/Cntr=0.3,0.1

Type RM Length L Ch R = 1 ,26194.03,237.806800,237.806800,237.806800
XS GIS Cut Line= 6
662079.460269383840610.921949866 662220.82038322840368.616002942
662261.491175086840322.896214918662342.853542664840257.232397639
662374.483938253840217.417552584662490.985173942839936.531855974
#Sta/Elev= 30
9599.065548.39649663.132531.57099674.588520.64819686.045515.0881 9731.87501.6881
9743.327478.27429754.783462.41529777.696449.90529812.366434.12839902.371 415.718
9945.492413.8168  9958.3415.0122    9999405.830910022.49409.455410048.77423.9625
10097.58440.7767 10164.2475.564610177.36480.432810209.64 477.70610231.07472.9468
10252.51478.774810263.23479.032310273.03473.222210284.66462.139510300.83464.6128
10338.24475.903610370.39477.179110381.11480.196610391.83486.7025 10400.9496.2296
#Mann= 3 , 0 , 0
9599.065    0.12       09599.065    0.12       0 10400.9    0.12       0
#XS Ineff= 2 , 0
       0                               0
Bank Sta=9599.065,10400.9
Exp/Cntr=0.3,0.1

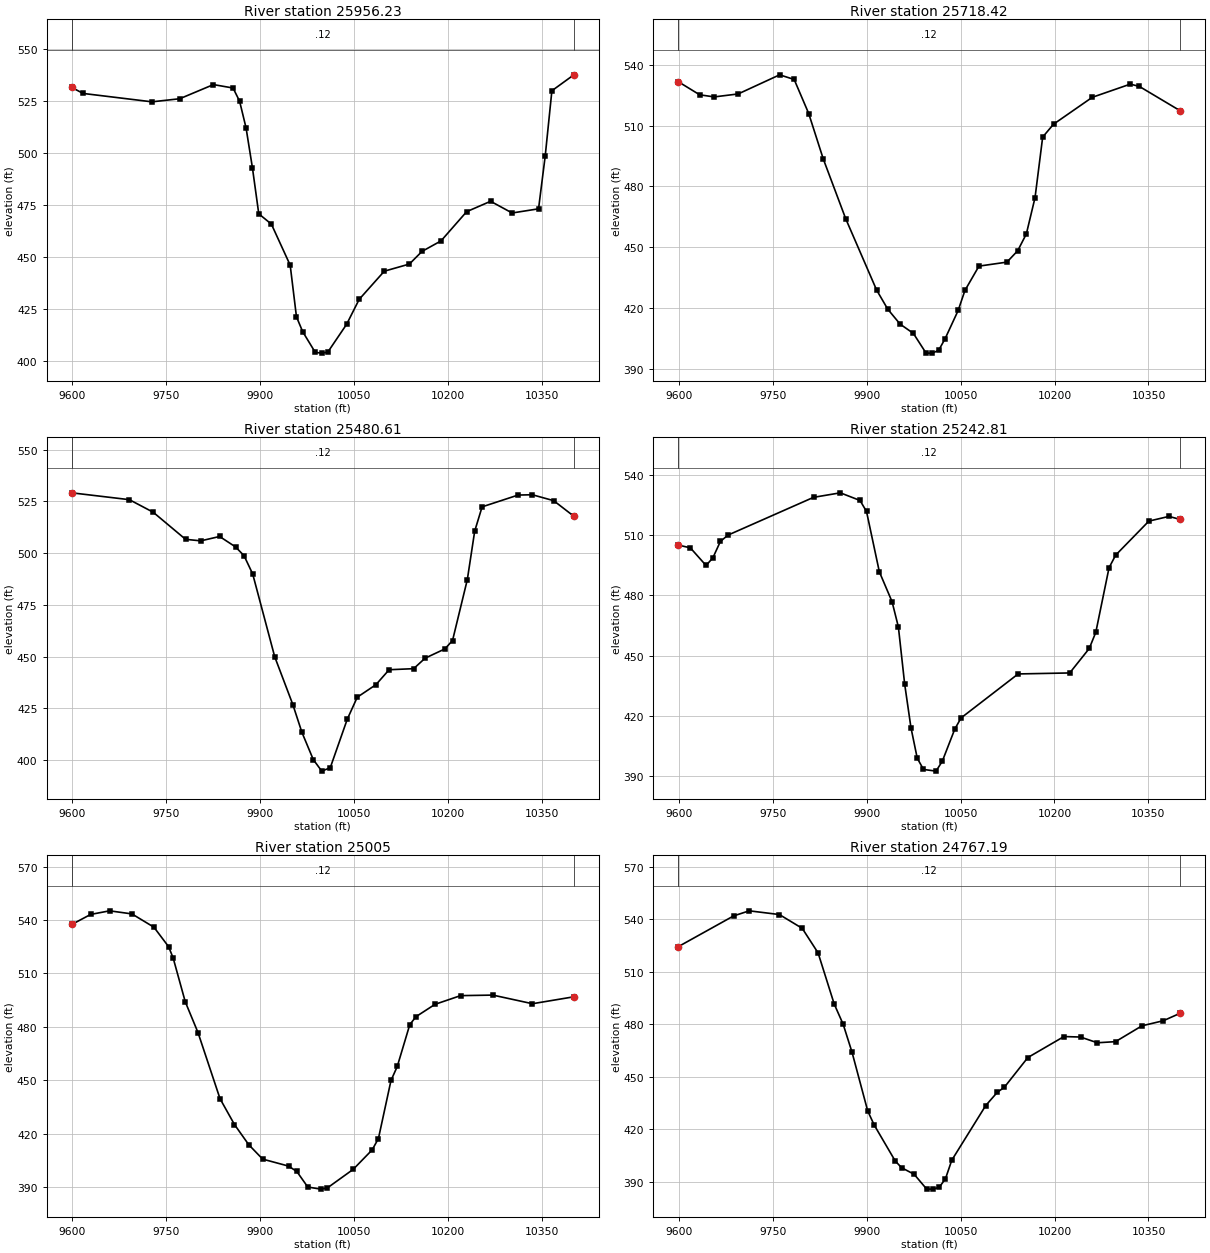
Type RM Length L Ch R = 1 ,25956.23,237.806800,237.806800,237.806800
XS GIS Cut Line= 6
662396.123120584840707.303371885662471.878389898840566.437944054
 662510.06622267 840460.51073042662517.872558202840393.244703765
 662512.68566779840169.715408655662577.714759845839942.081538471
#Sta/Elev= 30
9599.113531.67239617.139528.78299727.185524.73779771.517526.22419825.338533.0432
9856.705531.39429867.161525.01759877.451512.17419887.607492.97699897.762470.7628
9917.878 465.807 9947.93446.0169 9957.94421.1447 9967.95413.9249 9987.97403.9943
 9997.98403.6265   10008404.116810038.09417.548110058.15 429.55610098.23 443.118
 10138.3446.557310158.39452.6428 10188.8457.717310229.69 471.78910267.99476.8067
10302.37471.166910344.55473.1746 10355.2498.616110365.86530.076810400.93537.7503
#Mann= 3 , 0 , 0
9599.113    0.12       09599.113    0.12       010400.93    0.12       0
#XS Ineff= 2 , 0
       0                               0
Bank Sta=9599.113,10400.93
Exp/Cntr=0.3,0.1

Type RM Length L Ch R = 1 ,25718.42,237.806700,237.806700,237.806700
XS GIS Cut Line= 6
662466.467593279840674.511967313 662625.92258909840415.513578313
662665.893647831 840384.46356475662831.787945773840317.338578207
662901.922510236840241.572983865662988.291542646840106.155027807
#Sta/Elev= 30
9599.173 531.572 9633.42525.11229656.629 524.0729694.831525.53029761.069534.9429
9784.278532.66229807.487515.90669830.696493.57719866.461464.20649915.959428.9881
9933.773419.56949953.425412.24769974.594407.6839 9994.84397.993910004.92 397.966
10015.01399.367610025.27405.061210046.12418.964610056.93428.805110079.33440.7897
   10124442.759810141.18448.360410155.03 456.66910168.88474.519510181.07 504.311
10198.42510.648210260.25523.876110320.92530.358310335.26529.265810400.83517.2192
#Mann= 3 , 0 , 0
9599.173    0.12       09599.173    0.12       010400.83    0.12       0
#XS Ineff= 2 , 0
       0                               0
Bank Sta=9599.173,10400.83
Exp/Cntr=0.3,0.1

Type RM Length L Ch R = 1 ,25480.61,237.806800,237.806800,237.806800
XS GIS Cut Line= 6
662577.515097285840868.245352598662699.490281085 840712.57426319
662891.893637085 840504.86058493662940.078588558840447.511867315
663005.345664735840349.490997409663066.293710323840236.655019531
#Sta/Elev= 30
9599.017529.15629691.007525.84779729.059519.78089780.755506.68779805.089505.9383
9835.128508.05519860.576503.01799874.189498.76659888.023489.90549923.135449.9356
9952.077426.83629966.548413.43019984.745400.22399998.329394.633110011.88396.2791
10039.04419.719710055.01 430.358 10084.8436.412510105.91443.6476 10145.1444.1572
10163.31449.217510194.93453.706810207.18457.766610230.79487.188810242.59510.6514
10254.39 522.373 10311.9528.078810334.63528.225710368.73525.365110400.94517.8379
#Mann= 3 , 0 , 0
9599.017    0.12       09599.017    0.12       010400.94    0.12       0
#XS Ineff= 2 , 0
       0                               0
Bank Sta=9599.017,10400.94
Exp/Cntr=0.3,0.1

Type RM Length L Ch R = 1 ,25242.81,237.806800,237.806800,237.806800
XS GIS Cut Line= 6
662870.466848773841061.100754928662954.511684176840926.623647881
662999.161599254840823.616996895663015.941768783840749.043435724
663036.153333017840542.304921416663110.896862661840308.141766962
#Sta/Elev= 30
9599.093505.03459618.405503.65499643.524494.87039654.387498.66049666.381506.8224
9678.376509.9669 9815.15 528.7989857.945531.04889889.418527.24679899.782521.7739
9920.281491.72859940.591476.82939950.699 464.2489960.736435.78369970.772414.1078
  9980.8398.90059990.802393.2886 10010.8392.4523 10020.8  397.3610040.82413.4188
10050.84418.957310141.94440.851210224.35441.347210255.56453.5465   10266461.6072
10287.13493.732710297.69500.013610350.73516.959710382.89519.313310400.96 517.771
#Mann= 3 , 0 , 0
9599.093    0.12       09599.093    0.12       010400.96    0.12       0
#XS Ineff= 2 , 0
       0                               0
Bank Sta=9599.093,10400.96
Exp/Cntr=0.3,0.1

Type RM Length L Ch R = 1 ,   25005,237.806700,237.806700,237.806700
XS GIS Cut Line= 6
663088.728294373840985.867170042663251.730343951840709.914345054
663226.568085247840567.202932556663226.237440714840483.380205416
663248.494819644840372.099175439 663293.68518063840243.099558677
#Sta/Elev= 30
9599.169537.46719629.303543.10449659.605 545.131 9695.24543.39859730.403535.9258
9753.845 524.9619761.198518.47619780.369494.06689800.729476.76369835.892439.6176
9858.987425.0847 9881.82413.74699903.992405.67539945.286401.76099958.522398.7249
9976.019390.00339996.846388.8218 10007.3 389.49610048.51 399.91810078.83410.8646
10088.85417.256110108.89449.8398 10118.9457.700710138.92481.231210148.93485.7092
10179.23492.622110220.02497.498310271.59497.800510334.79492.956810400.88496.8437
#Mann= 3 , 0 , 0
9599.169    0.12       09599.169    0.12       010400.88    0.12       0
#XS Ineff= 2 , 0
       0                               0
Bank Sta=9599.169,10400.88
Exp/Cntr=0.3,0.1

Type RM Length L Ch R = 1 ,24767.19,237.806800,237.806800,237.806800
XS GIS Cut Line= 6
663060.474726798 841047.79962872663229.848135909840820.138424724
663279.281800709840794.119615694663471.173915338840755.704102193
663572.499047966840679.560194977663661.837543229840577.027138079
#Sta/Elev= 30
9599.198524.36649687.724  541.989712.602544.86649760.686542.74329797.167534.8561
 9822.49 520.8139848.212491.61089862.598 479.9439876.684464.0286 9901.76 430.426
9912.222422.33399945.514401.96319955.666 398.0599975.865394.26389995.883385.8024
10005.89385.787610015.89386.832510025.89391.744410035.93402.320910090.09433.5286
10108.74441.189810119.79443.975410157.43461.013310215.03473.0017 10241.5 472.722
10268.32469.445710297.38470.086910339.55479.136410373.75482.052510400.82486.3568
#Mann= 3 , 0 , 0
9599.198    0.12       09599.198    0.12       010400.82    0.12       0
#XS Ineff= 2 , 0
       0                               0
Bank Sta=9599.198,10400.82
Exp/Cntr=0.3,0.1

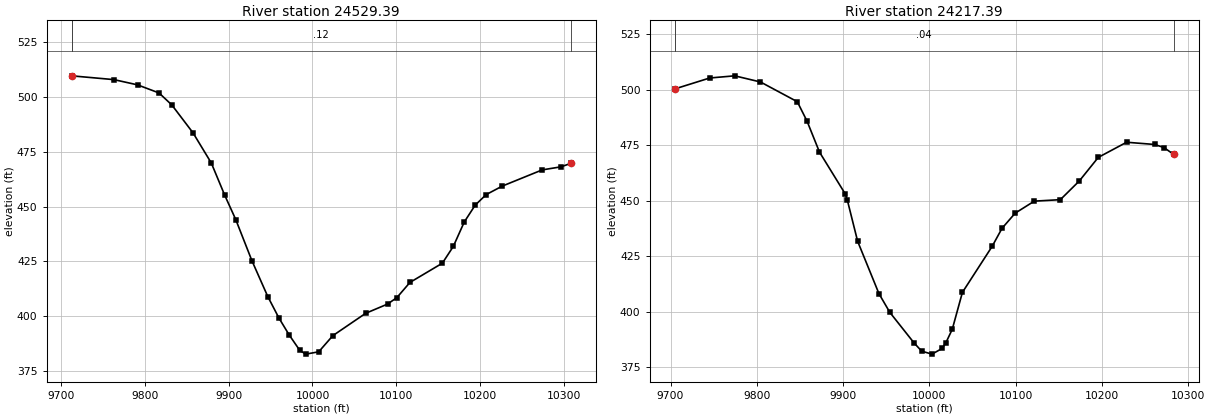
Type RM Length L Ch R = 1 ,24529.39,312.000000,312.000000,312.000000
XS GIS Cut Line= 6
663305.402101813841163.247173706663339.752114087841126.208861056
663400.267888041841056.550471538 663481.12521619840954.127754562
663635.809711463840770.338072347663685.750662729840705.952745552
#Sta/Elev= 30
9712.806509.62969763.321507.89479791.416505.51019817.067501.81259832.315496.3407
9857.571 483.6189879.371469.85979895.509455.04069908.533444.04929927.787425.2987
9946.755408.89879960.064399.10329972.236391.40799984.977384.31529992.052382.6507
10007.46383.708110024.27391.067910063.46401.277810089.59405.494810100.72408.4616
10116.26415.3667 10154.9424.140210167.97431.798910181.03442.946910194.09450.6375
10207.16455.442810226.31459.311310273.94466.707510296.34468.104910307.79 469.639
#Mann= 3 , 0 , 0
9712.806    0.12       09712.806    0.12       010307.79    0.12       0
#XS Ineff= 2 , 0
       0                               0
Bank Sta=9712.806,10307.79
Exp/Cntr=0.3,0.1

Type RM Length L Ch R = 1 ,24217.39,277.729500,277.729500,277.729500
XS GIS Cut Line= 6
663523.393764984841362.074734631663611.491978632841281.300784744
663667.313305896841223.246835584663714.822525604841162.739613008
663773.697010935841064.304992532 663850.78730727  840894.5660536
#Sta/Elev= 30
9704.782500.32089745.388505.25749774.384506.23769804.239503.47299846.926494.5866
9858.228485.83879872.656 471.8979902.417453.13039904.849450.41459916.865431.7521
9941.599408.14639954.176399.74759982.134386.04639991.104382.273910003.04380.9442
 10014.8383.499210019.24386.153810026.56392.1398 10038.3408.748910072.77429.4617
10084.26437.610710099.44444.401710121.61449.8199 10151.8450.480510173.81458.9133
10195.76469.514510228.61476.333910261.01475.334810271.81473.963410283.07470.8858
#Mann= 3 , 0 , 0
9704.782    0.04       09704.782    0.04       010283.07    0.04       0
#XS Ineff= 2 , 0
       0                               0
Bank Sta=9704.782,10283.07
Exp/Cntr=0.3,0.1