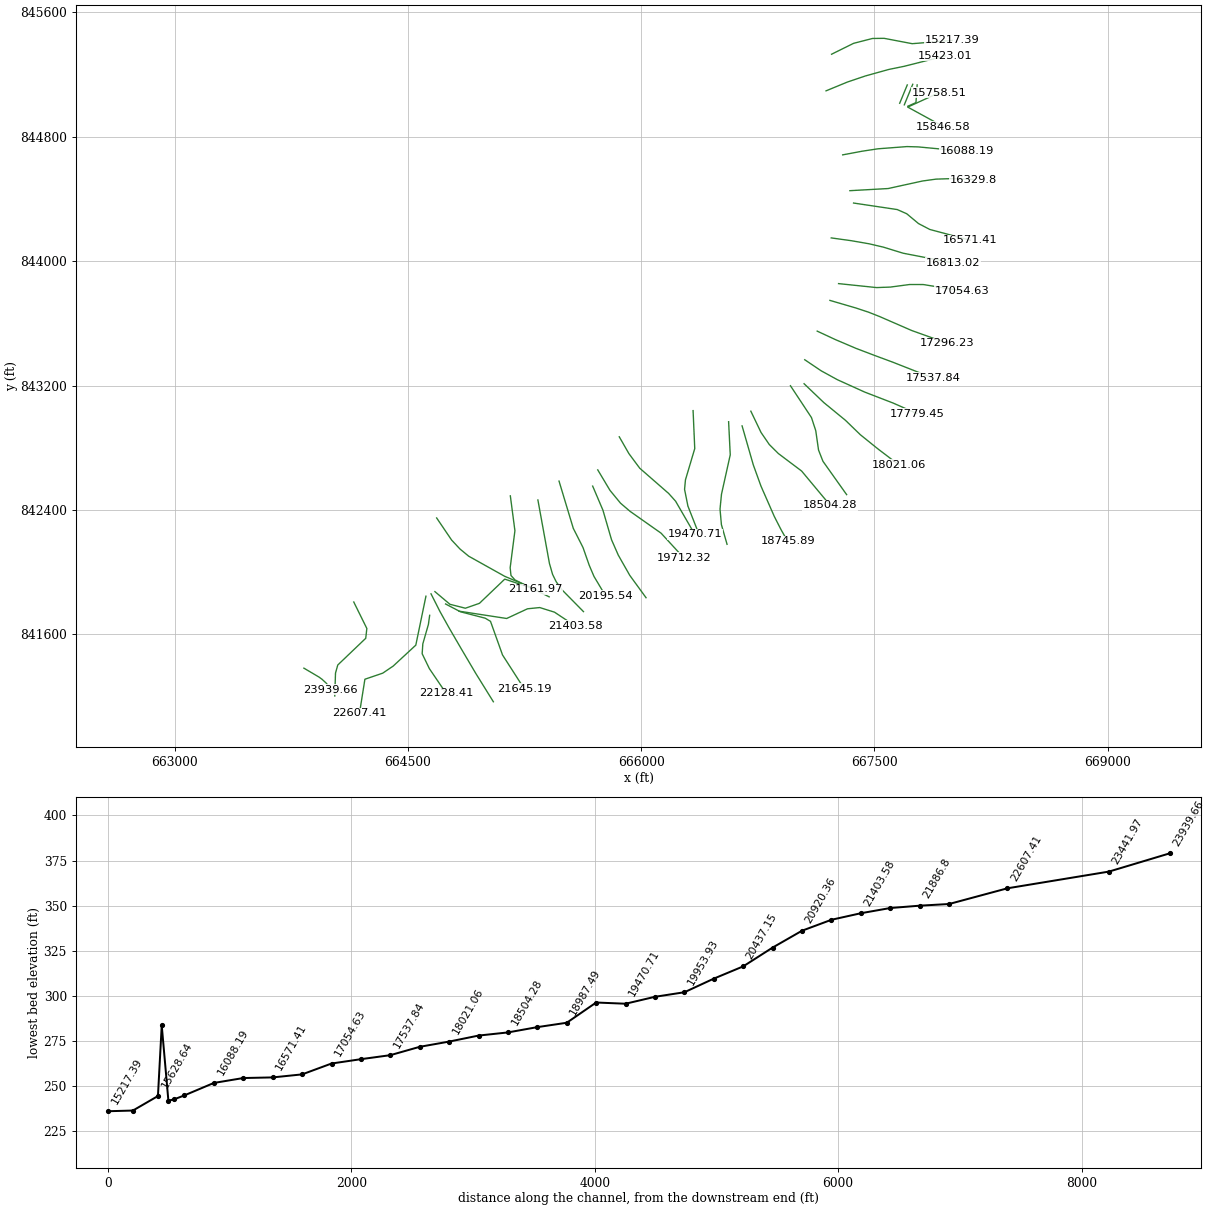
HEC-RAS study 13678_ras.prj: 13678

--- 13678_ras.g01 (geometry) --- (continued)

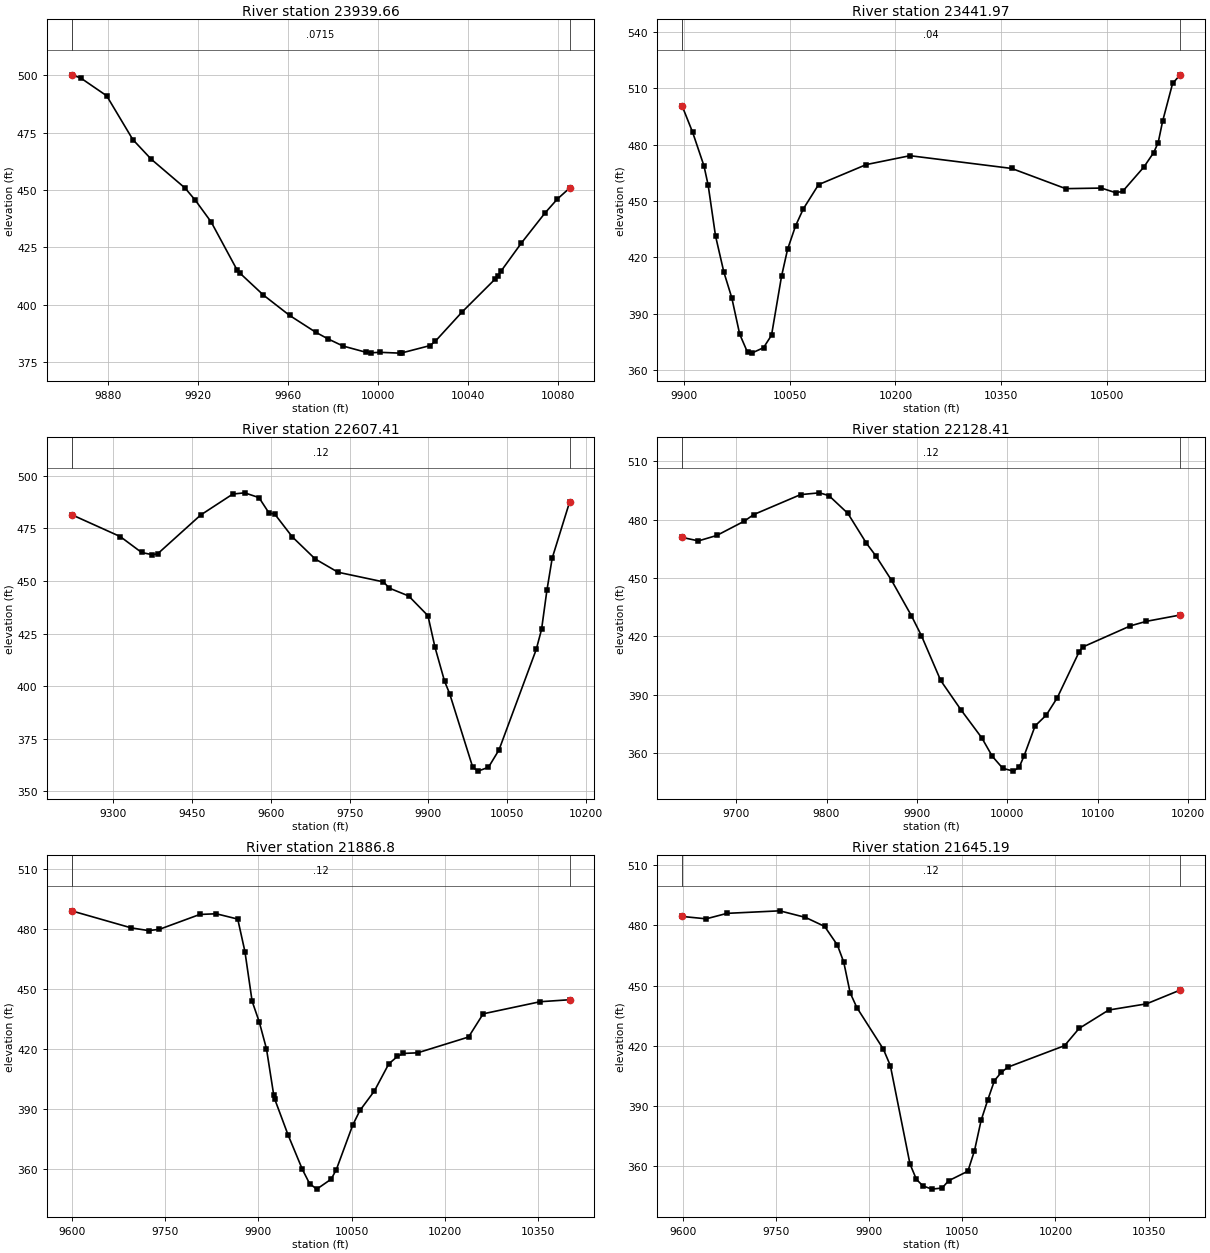
Type RM Length L Ch R = 1 ,23939.66,497.687500,497.687500,497.687500
XS GIS Cut Line= 6
663831.558468383841382.984894079663928.191896101841325.941509388
663948.285695792841311.285461252663975.331051577841286.327000895
663985.922034086841272.918614242663999.162688221841245.673670447
#Sta/Elev= 30
9863.915500.15239867.912498.82169879.524491.01959891.136471.96889899.294463.4404
9914.361450.84329918.966445.48669925.973436.06669937.586415.00499938.638413.8976
9949.198404.2458 9960.81395.39929972.423388.07459977.725 385.255 9984.56382.0578
9994.677379.36319996.945379.1014   10001379.310710009.82378.959210010.69 379.051
 10023.2382.227910025.58384.106110037.36 396.72110052.27411.276810053.43412.6319
10054.92 414.79310063.87426.895310074.42 440.047 10079.9 446.09610085.28  450.81
#Mann= 3 , 0 , 0
9863.915  0.0715       09863.915  0.0715       010085.28  0.0715       0
#XS Ineff= 2 , 0
       0                               0
Bank Sta=9863.915,10085.28
Exp/Cntr=0.3,0.1

Type RM Length L Ch R = 1 ,23441.97,834.562800,834.562800,834.562800
XS GIS Cut Line= 6
664152.168053379841808.421217422664236.379216114 841637.99894129
664229.149362296841574.907467395664049.411782205841403.266174659
664034.838464916841351.449935362 664030.04190581841204.413360266
#Sta/Elev= 30
9897.666500.5295 9912.43486.60719928.455468.75219934.432458.40429944.868431.3477
9956.654412.10069967.864398.44749979.074379.04319990.284369.23989996.112368.8748
 10012.9371.767210024.25378.4263 10038.4409.784510046.97424.190710058.32436.7284
10069.31445.789710090.94458.728710158.58469.420310220.49474.154310364.74467.3562
10441.31456.585510491.88456.8911 10511.9454.453410521.91455.079710552.18468.1331
10566.09475.851610572.43481.163610578.69  492.5310592.84 512.68110603.64517.2811
#Mann= 3 , 0 , 0
9897.666    0.04       09897.666    0.04       010603.64    0.04       0
#XS Ineff= 2 , 0
       0                               0
Bank Sta=9897.666,10603.64
Exp/Cntr=0.3,0.1

Type RM Length L Ch R = 1 ,22607.41,479.000000,479.000000,479.000000
XS GIS Cut Line= 6
664616.285446703841845.623947099664551.181280077841530.953808233
664405.781974524841396.405197114664338.507668972841350.832280442
664223.841362238841311.719254345664188.896968812841092.173371047
#Sta/Elev= 30
9220.479481.51039313.023471.1065 9353.87463.52699374.293 462.4539384.505462.9142
9466.199481.3076 9527.47491.29279549.949491.87799577.275489.62119596.533482.2496
9607.223481.81629640.676470.97399684.331460.44659727.805454.1326 9814.32449.5481
9825.559446.57189862.384442.85379899.083433.45869912.389418.56769930.684402.3362
9940.402396.40259984.262361.5144 9994.29359.600110014.35361.439310034.41369.7119
10105.29417.450810115.42426.987110125.55445.480710135.67460.845810168.68487.4115
#Mann= 3 , 0 , 0
9220.479    0.12       09220.479    0.12       010168.68    0.12       0
#XS Ineff= 2 , 0
       0                               0
Bank Sta=9220.479,10168.68
Exp/Cntr=0.3,0.1

Type RM Length L Ch R = 1 ,22128.41,241.608600,241.608600,241.608600
XS GIS Cut Line= 6
664640.325367064841722.786394114 664632.17903562841664.148683356
664596.279737689841539.103319691664592.085298129 841475.61920602
664638.477686924841379.740182229664745.385723453841222.510731758
#Sta/Elev= 30
9640.465470.83469658.415469.06879678.615471.84759709.118 479.205 9719.44482.5607
 9771.32492.81579792.248493.73649802.711492.29069823.639483.16789844.171467.8386
9854.354461.50789871.887448.86699893.936430.62419904.924420.47229926.294397.4095
9948.577 382.4339971.743367.96289983.326358.51969994.909352.343310006.59350.8903
10013.13352.922410018.62358.886610030.69374.094110042.95379.599510055.12388.4811
10079.45412.182310083.38414.592610136.06425.447910153.63427.769610191.16431.0198
#Mann= 3 , 0 , 0
9640.465    0.12       09640.465    0.12       010191.16    0.12       0
#XS Ineff= 2 , 0
       0                               0
Bank Sta=9640.465,10191.16
Exp/Cntr=0.3,0.1

Type RM Length L Ch R = 1 , 21886.8,241.608600,241.608600,241.608600
XS GIS Cut Line= 6
  664649.0213353841860.991211219664706.454225645841747.326824262
664764.273514155 841643.61882065664842.609725168841508.832930899
 664936.05035885841350.389824288665049.943863288841166.807002317
#Sta/Elev= 30
9599.016489.22989695.361 480.6759723.142479.33419740.479479.97889805.523487.4149
9832.073487.7573 9866.64485.10029878.208468.84279889.775444.02269901.343433.5708
9912.911420.17569924.478397.27799926.126395.08039947.613377.15039970.748359.8185
9982.316352.73689993.883349.967310017.06354.944910025.39359.723710051.89382.0665
 10063.5389.371910086.72399.093110109.93412.668810123.82416.375810133.15 417.868
10156.37418.178310238.36426.0793 10261.9437.690810353.67443.748610400.99444.7329
#Mann= 3 , 0 , 0
9599.016    0.12       09599.016    0.12       010400.99    0.12       0
#XS Ineff= 2 , 0
       0                               0
Bank Sta=9599.016,10400.99
Exp/Cntr=0.3,0.1

Type RM Length L Ch R = 1 ,21645.19,241.608500,241.608500,241.608500
XS GIS Cut Line= 6
664742.639062768841795.625127109664838.030459503841745.570362049
664997.361164232841704.265926193665031.563550673 841683.91161111
665108.743322397841467.868630612 665248.18819162841250.825405286
#Sta/Elev= 30
9599.232484.46379637.799483.28239671.367486.00739756.303487.26399797.656483.9887
9828.465479.50669849.005470.23189859.275461.68979869.545446.45439880.282439.1118
9922.981418.40569934.311410.14319965.889361.18969976.228 353.5339986.567350.3178
   10001348.664610017.62349.208610027.99352.8195 10059.1357.593910069.73367.8073
 10080.4382.899810091.07393.059610101.87402.708210112.86406.812410123.85409.4552
10214.74420.113510238.16428.692810285.82437.861710346.64440.935410400.95447.8105
#Mann= 3 , 0 , 0
9599.232    0.12       09599.232    0.12       010400.95    0.12       0
#XS Ineff= 2 , 0
       0                               0
Bank Sta=9599.232,10400.95
Exp/Cntr=0.3,0.1

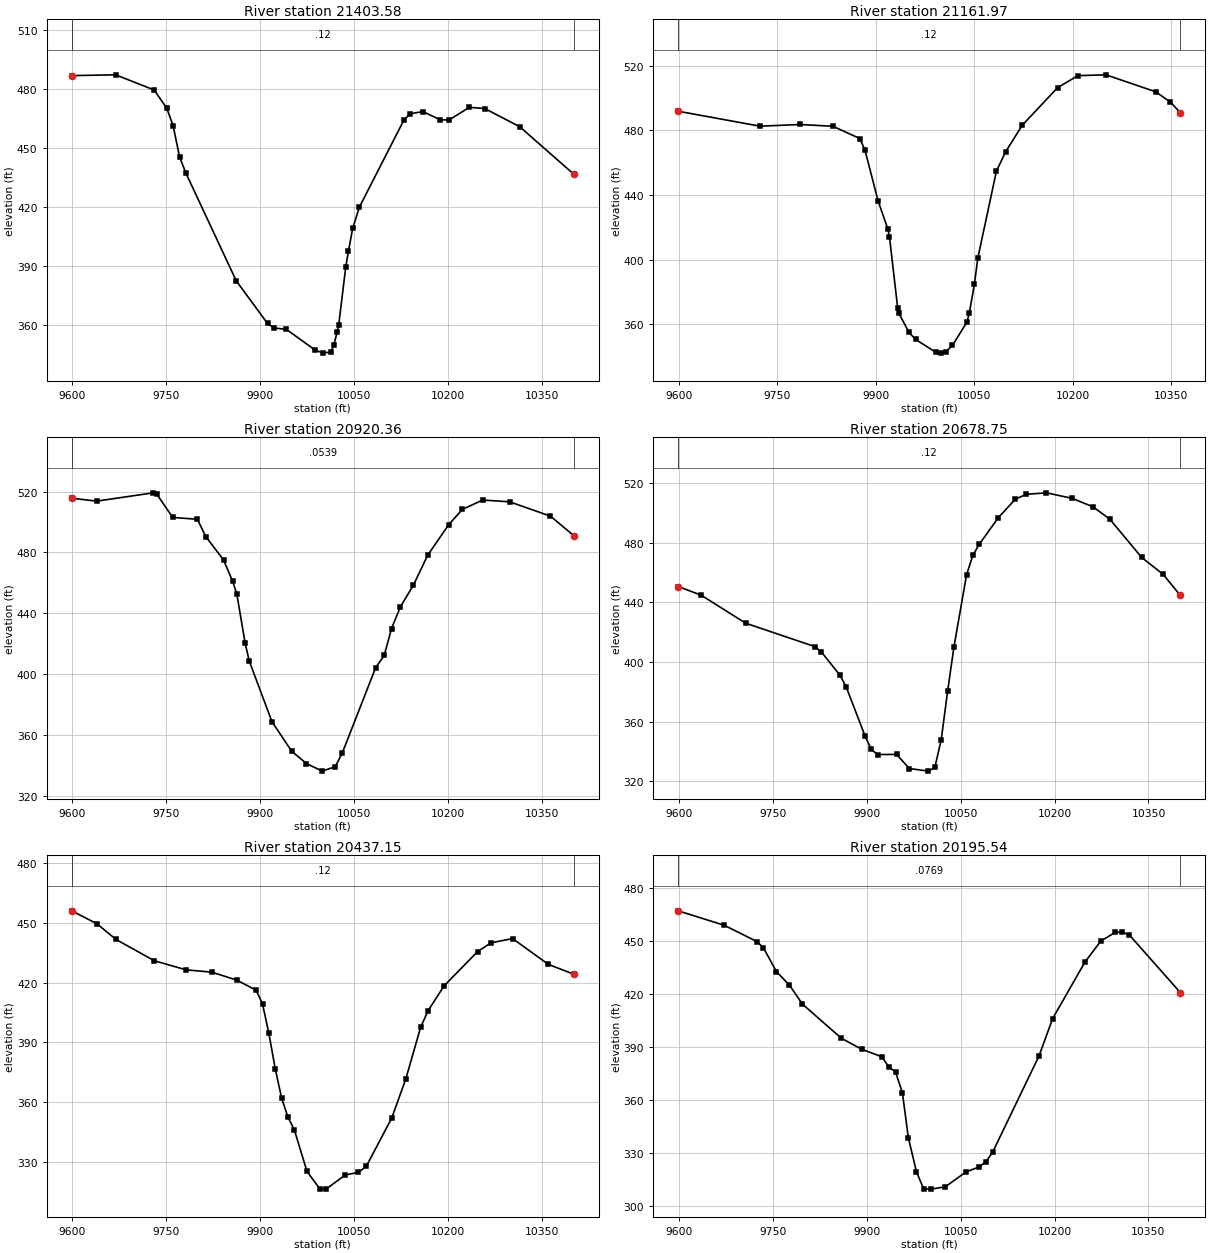
Type RM Length L Ch R = 1 ,21403.58,241.608600,241.608600,241.608600
XS GIS Cut Line= 6
 664828.14156543841749.519855383665135.550066357841702.392348009
665269.164352445 841764.59725031665348.067063763841772.625690615
665442.994400459841742.947489882665574.661873932841655.670785355
#Sta/Elev= 30
9599.165486.60949669.244487.00799730.599479.31789750.923470.01669761.085461.0278
9771.247445.35279781.352437.15039861.691382.48519911.701360.82429921.746358.5759
9941.935357.7898 9987.32347.407710000.55345.773410013.08346.464610017.67350.0217
10022.72356.348910025.31360.015710036.64389.661510040.87397.503510047.61409.0418
10058.35419.882810129.57464.145910139.58467.265710159.94468.340710187.42464.1889
10201.54464.097810233.88470.506210258.45469.910610314.34 460.67610400.72436.5468
#Mann= 3 , 0 , 0
9599.165    0.12       09599.165    0.12       010400.72    0.12       0
#XS Ineff= 2 , 0
       0                               0
Bank Sta=9599.165,10400.72
Exp/Cntr=0.3,0.1

Type RM Length L Ch R = 1 ,21161.97,241.608600,241.608600,241.608600
XS GIS Cut Line= 6
 664674.08712424841875.022813589664770.695251992841793.645524517
664870.016077418841768.385936629664960.356460411 841799.86161083
 665123.17715579841955.448161702665319.017602331841890.554496117
#Sta/Elev= 30
9599.172491.90729723.771482.64669784.381483.7018 9834.83482.59329875.608475.0144
9883.426467.91839903.481 436.3839918.461418.79039920.791414.19669933.344369.8753
9935.123366.81019950.441354.97569960.547350.62599991.052342.7659    9999342.1452
10006.52342.965210016.71346.948510038.64361.292710042.27366.780910050.03384.6389
10055.38401.144110083.71454.931710097.66466.770710122.93483.226610176.77506.5057
10207.62513.948910250.53514.451210326.27503.921310348.24497.682610363.63491.0515
#Mann= 3 , 0 , 0
9599.172    0.12       09599.172    0.12       010363.63    0.12       0
#XS Ineff= 2 , 0
       0                               0
Bank Sta=9599.172,10363.63
Exp/Cntr=0.3,0.1

Type RM Length L Ch R = 1 ,20920.36,241.608600,241.608600,241.608600
XS GIS Cut Line= 6
664685.243770131  842348.7439896664781.545471307842206.539722446
664835.082640368 842149.31469933664891.017503012842103.112946048
 665122.23305995841973.904684259665319.017602331841890.554496117
#Sta/Elev= 30
9599.077515.71629638.685513.80819729.394519.27399734.862518.41449760.261503.0762
9799.606501.86939813.273490.35769841.409475.1719 9855.91461.14469862.661452.6698
9876.026420.14419882.623408.43779918.918368.53379950.517349.09259973.921341.0632
    9999336.080810019.85 339.00510030.96347.877110084.53404.280610098.08412.2235
10109.73429.959610123.97444.2307 10144.7458.510310167.65478.279310201.14498.3389
10223.01508.384410255.33514.519610298.35513.373410363.59503.921310400.95491.0515
#Mann= 3 , 0 , 0
9599.077  0.0539       09599.077  0.0539       010400.95  0.0539       0
#XS Ineff= 2 , 0
       0                               0
Bank Sta=9599.077,10400.95
Exp/Cntr=0.3,0.1

Type RM Length L Ch R = 1 ,20678.75,241.608500,241.608500,241.608500
XS GIS Cut Line= 6
665159.080158007842490.846258453665188.485020586842266.657343879
665157.904594762842028.373713607 665163.27956866841978.772199065
665188.439632224841950.676664077665408.747724978 841841.54164299
#Sta/Elev= 30
9599.049450.49759635.628444.7104 9706.66425.93959817.184410.22819827.192406.8418
9857.199391.12239867.201383.26249897.313350.37279907.357341.2588  9917.4337.8475
9947.756337.94659968.025328.48199998.632326.727710008.84329.223810019.04347.8376
10029.23380.272910039.38 410.14910059.57458.528410069.63471.434710079.63478.7764
10110.08496.593310137.36509.056210154.79512.344410187.09513.336610228.43509.6078
10261.27503.964610288.03495.797110339.17469.9997 10373.4458.673410400.85  444.57
#Mann= 3 , 0 , 0
9599.049    0.12       09599.049    0.12       010400.85    0.12       0
#XS Ineff= 2 , 0
       0                               0
Bank Sta=9599.049,10400.85
Exp/Cntr=0.3,0.1

Type RM Length L Ch R = 1 ,20437.15,241.608600,241.608600,241.608600
XS GIS Cut Line= 6
665336.279693816842464.505505261665410.475634637842056.343268251
665430.821357419841985.485290243665454.205822401841938.059370719
665492.213310047841885.647347271665629.453568428841746.443831226
#Sta/Elev= 30
9599.016456.13939639.233449.63759669.773441.73579730.854431.06919781.755426.4581
9822.475 425.3489863.067 421.2659893.505416.23929903.651409.41659913.797394.6425
9923.943376.86939934.089362.18039944.235352.47789954.381346.17339974.673325.2273
9994.965316.5332 10005.1316.302210035.83323.406810056.56324.731810069.34327.7008
10110.12352.044410132.68371.817510156.25397.654210168.23405.995210193.52418.3728
10247.08435.624110268.53440.048410303.09442.195210360.18429.242910400.93424.2667
#Mann= 3 , 0 , 0
9599.016    0.12       09599.016    0.12       010400.93    0.12       0
#XS Ineff= 2 , 0
       0                               0
Bank Sta=9599.016,10400.93
Exp/Cntr=0.3,0.1

Type RM Length L Ch R = 1 ,20195.54,241.608600,241.608600,241.608600
XS GIS Cut Line= 6
665472.139302854  842585.7537968665563.780708237842282.234794728
665626.436883804842158.595136501665665.850514799842045.796435502
665696.908818425841972.871870435665772.236533484841846.533042921
#Sta/Elev= 30
9599.036467.11589672.639458.90519724.653449.73559735.055446.20369755.861432.7112
9776.666425.03519797.472414.23269859.731394.91149891.915388.74179924.125384.4639
9935.095378.85069946.066375.81579957.037364.06659966.546338.6414 9979.49319.2951
9990.912309.6886 10002.5309.501210025.53310.809510058.74319.270910079.92322.0983
10090.52325.092210101.11330.380610175.28384.980410197.02406.130910248.81438.2177
10273.94449.9884 10296.6454.846410307.94455.165610319.48453.450210400.89420.8458
#Mann= 3 , 0 , 0
9599.036  0.0769       09599.036  0.0769       010400.89  0.0769       0
#XS Ineff= 2 , 0
       0                               0
Bank Sta=9599.036,10400.89
Exp/Cntr=0.3,0.1

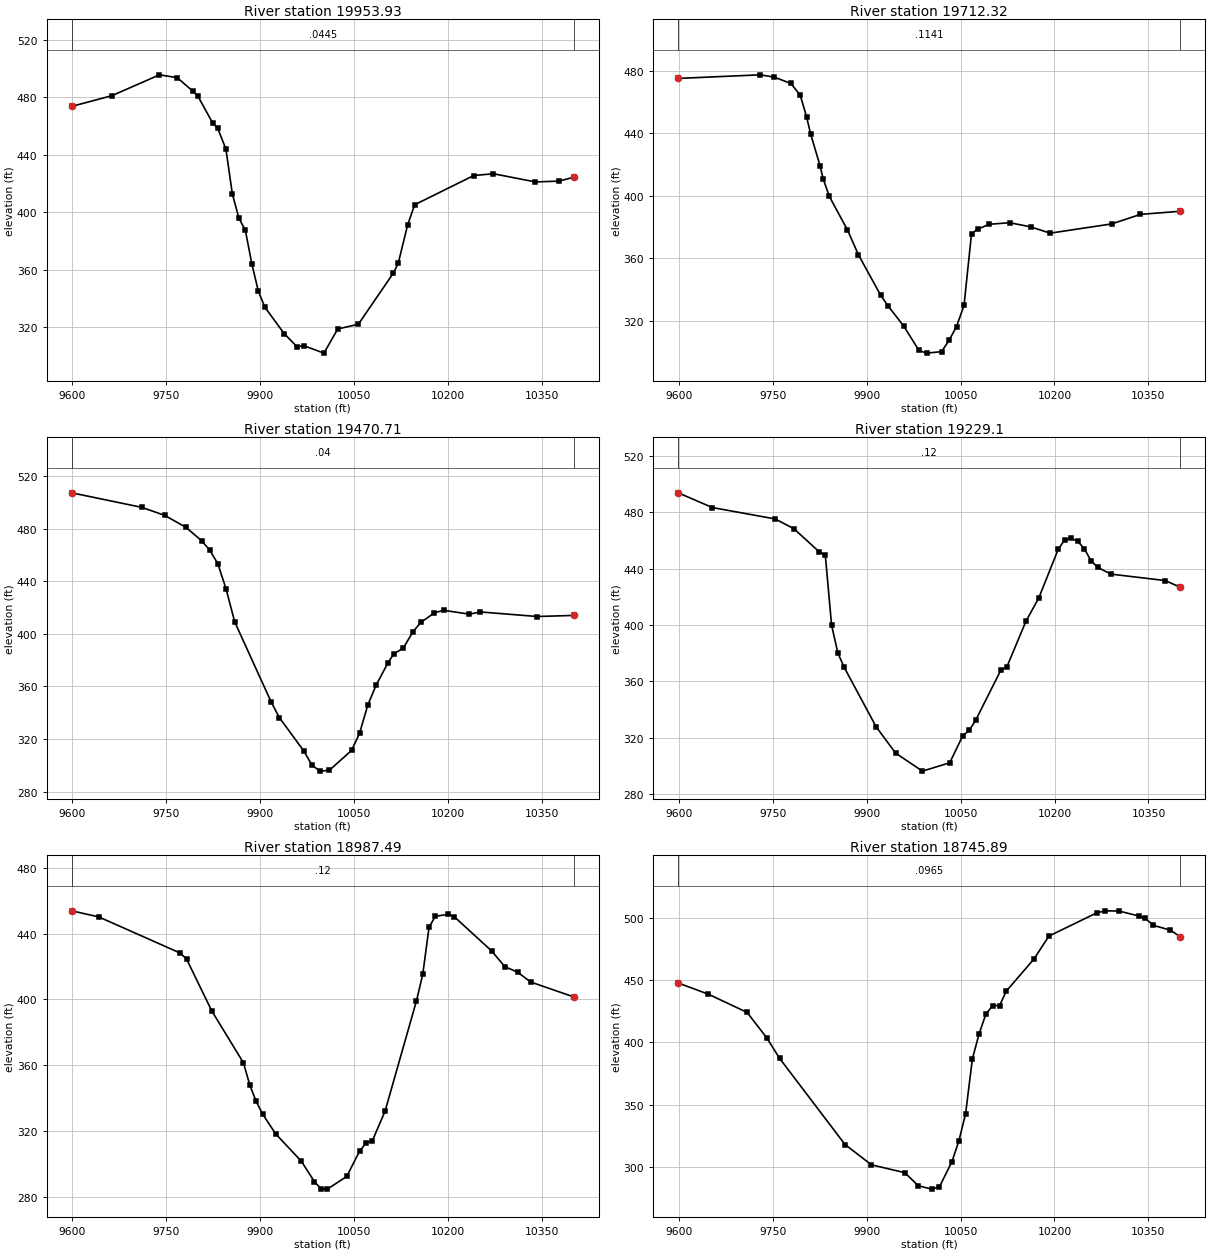
Type RM Length L Ch R = 1 ,19953.93,241.608600,241.608600,241.608600
XS GIS Cut Line= 6
665688.517390362842553.652997757665754.433428283842398.773053587
665809.808102143842208.669592135665853.179794313842109.719189156
665927.090980728841979.531595552666031.608067715841836.025606721
#Sta/Elev= 30
9599.067473.65419663.112481.10999739.137495.62569767.408493.64169792.478484.2507
9800.693480.65069824.115462.06949832.194458.36359845.206444.06669855.567   412.7
9865.907395.95029876.247 387.5229886.588364.28299896.928 345.1859907.268334.0477
9938.289315.5417 9958.97306.32299969.448307.148510001.83301.948310023.82318.7435
10056.79322.042310112.82357.742510120.46364.480110135.42391.051710146.72405.2102
10241.04425.539810272.52426.781710339.58421.088910377.18421.647610400.96424.3811
#Mann= 3 , 0 , 0
9599.067  0.0445       09599.067  0.0445       010400.96  0.0445       0
#XS Ineff= 2 , 0
       0                               0
Bank Sta=9599.067,10400.96
Exp/Cntr=0.3,0.1

Type RM Length L Ch R = 1 ,19712.32,241.608500,241.608500,241.608500
XS GIS Cut Line= 6
665721.247960821842657.789982829665799.775641012842526.361826734
665867.536228405842443.856983877665928.708091464842391.540321815
 666128.55337965842250.789914634666274.930750774842091.535068454
#Sta/Elev= 30
9599.083475.18999730.123477.48079752.254476.02739779.071471.94869793.981464.3468
9804.178450.46039810.523439.62019825.622419.22989830.546410.91129840.487399.6448
9869.345  378.249886.714362.49849922.139336.62459934.128329.66749959.366316.6616
9983.537 301.1419995.623299.429510019.58 300.36510031.56307.530110043.53316.4629
 10055.5329.931410067.48375.805910077.64 378.78710095.82381.8615 10128.5 382.865
10161.82380.223410193.08  376.1810291.37382.101510337.29388.193210400.96390.1902
#Mann= 3 , 0 , 0
9599.083  0.1141       09599.083  0.1141       010400.96  0.1141       0
#XS Ineff= 2 , 0
       0                               0
Bank Sta=9599.083,10400.96
Exp/Cntr=0.3,0.1

Type RM Length L Ch R = 1 ,19470.71,241.608600,241.608600,241.608600
XS GIS Cut Line= 6
665859.517424488842870.563390324665921.546792866842762.367462254
665990.994589104842668.823427116666177.080710071842506.376655475
666221.747068826842456.514099522666344.895891014842243.705809573
#Sta/Elev= 30
9599.061507.3916 9711.22496.29429747.368490.24549781.516481.11199806.742 470.787
9819.597463.65519832.451453.32319845.612434.03899859.271409.20419917.516 348.229
9930.477336.38589969.846310.79749982.657300.13749995.467295.582110010.35296.1838
10045.91311.319810058.68324.3954 10071.9345.915610085.11360.973410103.88377.8361
10113.31384.775310128.64389.251910143.85401.5653 10156.7408.827310178.38416.0848
10193.02417.982710234.18415.046210251.67416.729210342.63413.257510400.95414.0964
#Mann= 3 , 0 , 0
9599.061    0.04       09599.061    0.04       010400.95    0.04       0
#XS Ineff= 2 , 0
       0                               0
Bank Sta=9599.061,10400.95
Exp/Cntr=0.3,0.1

Type RM Length L Ch R = 1 , 19229.1,241.608600,241.608600,241.608600
XS GIS Cut Line= 6
666334.198958775 843038.94484258666344.849952309842794.682766736
666285.104941922842593.756628659666279.407230143842532.568668479
666300.864641167842425.268818568666364.745570274842262.813380204
#Sta/Elev= 30
9599.087493.82099653.542483.36739753.851475.28959783.851468.31929823.927452.0612
9833.952449.60179843.978 399.8639854.083379.95499864.192369.88169915.133 327.706
9946.256309.01929989.078296.255610032.61302.165410053.62321.4899 10063.8325.1881
10073.93332.256910114.12367.826410124.15370.526410154.42402.7267 10174.8419.1203
10205.82453.664710216.16460.423810226.51461.4834 10237.1459.403710247.69 454.044
10258.29445.567410269.06440.856210290.07436.116610376.78431.539810400.87426.7538
#Mann= 3 , 0 , 0
9599.087    0.12       09599.087    0.12       010400.87    0.12       0
#XS Ineff= 2 , 0
       0                               0
Bank Sta=9599.087,10400.87
Exp/Cntr=0.3,0.1

Type RM Length L Ch R = 1 ,18987.49,241.608600,241.608600,241.608600
XS GIS Cut Line= 6
666562.605756155 842967.68500606666573.152235014842754.723052439
666516.850157843842501.303137828666507.350758116842405.557844732
666516.415665004 842305.38964911666552.560060302842179.481345495
#Sta/Elev= 30
9599.066453.75189642.174450.06469772.498428.10249782.507424.42229822.614393.0974
9873.158361.66149883.344348.2219 9893.53338.18319903.721330.62579924.424318.6598
9965.829301.89679986.532289.58429996.883 285.32810007.26285.032110038.23292.7484
10058.72308.066310068.97312.918910079.13314.400310099.35332.230210149.59399.2335
10159.61415.332910169.62443.723710179.63450.456110199.66 451.58610209.67450.2663
10269.75429.370510290.67419.904510311.19416.525810331.92410.591110400.88401.5524
#Mann= 3 , 0 , 0
9599.066    0.12       09599.066    0.12       010400.88    0.12       0
#XS Ineff= 2 , 0
       0                               0
Bank Sta=9599.066,10400.88
Exp/Cntr=0.3,0.1

Type RM Length L Ch R = 1 ,18745.89,241.608600,241.608600,241.608600
XS GIS Cut Line= 6
 666649.27745839 842940.96245797666721.077682934842690.990816622
666770.500476843842554.076694888666856.491946229842358.325898483
666899.901295158842273.348826055666942.784312832842197.625041959
#Sta/Elev= 30
9599.013447.57499646.739438.7144 9709.04424.0522 9740.19403.82859761.006387.2213
9865.418318.31039907.594 302.0779960.868295.78069982.308285.386410003.71282.6066
10016.24284.447110036.28304.691610047.13320.919310057.99342.834110068.85386.9223
10079.71407.120810090.57422.909510101.43429.493710112.29429.555110123.15441.1441
10167.21466.781710191.09485.128210267.18503.6616 10281.2505.356810303.18505.1896
10335.04 501.144 10344.6499.454910358.03493.731510385.18489.880610400.98484.5534
#Mann= 3 , 0 , 0
9599.013  0.0965       09599.013  0.0965       010400.98  0.0965       0
#XS Ineff= 2 , 0
       0                               0
Bank Sta=9599.013,10400.98
Exp/Cntr=0.3,0.1

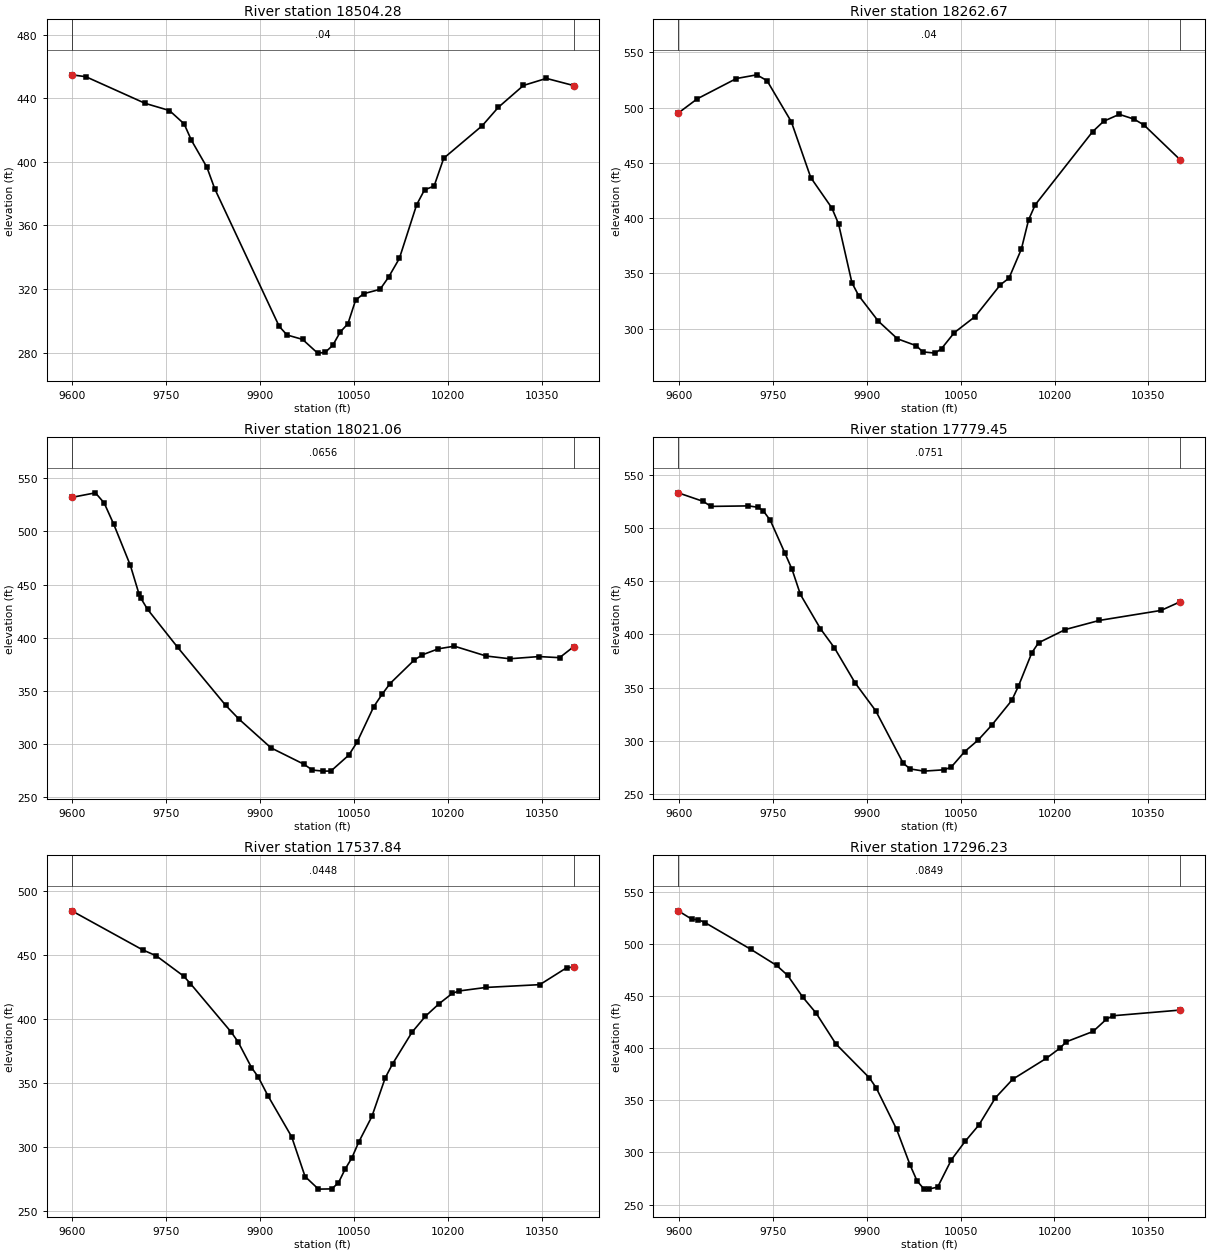
Type RM Length L Ch R = 1 ,18504.28,241.608500,241.608500,241.608500
XS GIS Cut Line= 6
666705.610459084 843035.36309062666771.322875024842898.235123169
666824.330265062842820.796472156666882.507277122 842763.03967967
667032.401467886842650.247877831667215.280298204842430.722240729
#Sta/Elev= 30
9599.085454.75719621.443453.59669716.377436.79379755.013432.30999778.522423.8986
9790.276413.49949814.969396.56699827.435383.06119930.339296.52729942.872291.0799
  9967.7288.29769991.735279.663410003.76280.125110015.88 284.55710028.01293.0362
10040.13298.145410052.38312.996310065.19317.043410091.47319.790410105.05327.4441
10122.33339.275810149.89373.018310162.48382.381110177.77384.757510193.14402.2864
10254.63422.744610280.24 434.27510320.47448.074210357.07452.508810400.96 447.981
#Mann= 3 , 0 , 0
9599.085    0.04       09599.085    0.04       010400.96    0.04       0
#XS Ineff= 2 , 0
       0                               0
Bank Sta=9599.085,10400.96
Exp/Cntr=0.3,0.1

Type RM Length L Ch R = 1 ,18262.67,241.608600,241.608600,241.608600
XS GIS Cut Line= 6
666960.179303762843199.103193288667095.417303863842994.280199119
667122.936075758842910.202681897667141.002346611842785.034261191
 667169.28503036842713.159915085667321.418976592842498.898691579
#Sta/Elev= 30
 9599.09 495.1489629.607508.08669692.073526.42179724.627529.75169740.925524.4403
9779.723487.2674 9810.75436.75379844.345409.32859855.083394.94629876.488341.5516
 9887.19330.0241 9918.44306.96999949.154290.86229979.443284.58619989.492279.0542
 10009.6277.916610019.66282.054410039.94296.4312 10073.2311.005510113.69339.8519
 10127.3345.730410147.09372.083210158.62398.553710169.19412.137710260.68478.1932
10278.49487.7223 10303.4493.993510327.11489.652210343.01484.276210400.91452.7497
#Mann= 3 , 0 , 0
 9599.09    0.04       0 9599.09    0.04       010400.91    0.04       0
#XS Ineff= 2 , 0
       0                               0
Bank Sta=9599.09,10400.91
Exp/Cntr=0.3,0.1

Type RM Length L Ch R = 1 ,18021.06,241.608600,241.608600,241.608600
XS GIS Cut Line= 6
667047.973255528843211.917107717667174.233202157843091.233231484
667314.010078575 842976.71361532 667409.38545579842884.306171186
 667522.88020249842792.738025646667656.473621418842691.210537649
#Sta/Elev= 30
9599.034532.02999636.789536.32469650.758526.80429666.226506.55239692.667467.9909
9706.468441.08139709.445437.13449720.125426.71639768.176 390.9959844.853336.4862
  9866.2 323.4549917.341 296.432 9969.55281.15139983.428275.5681   10001 274.584
10012.96 274.66610041.42289.596510054.56301.663110081.45335.299210094.56346.7256
10107.41356.959310145.95378.9953 10158.8383.9124 10184.5389.6157 10210.2392.0946
10260.95382.832810298.63380.265310345.12382.320910378.17381.292810400.96391.7353
#Mann= 3 , 0 , 0
9599.034  0.0656       09599.034  0.0656       010400.96  0.0656       0
#XS Ineff= 2 , 0
       0                               0
Bank Sta=9599.034,10400.96
Exp/Cntr=0.3,0.1

Type RM Length L Ch R = 1 ,17779.45,241.608600,241.608600,241.608600
XS GIS Cut Line= 6
667052.229440183843366.133786021667157.833384802843294.997481536
667261.901153141843237.917676038667437.448228851843158.363589291
667621.484042115843087.271477627667773.216992156843020.342293964
#Sta/Elev= 30
9599.025532.8662 9639.01 524.8189651.211  520.139711.118520.60399726.372519.3108
9734.651516.16219746.197506.90549769.289476.41939780.835460.98579794.171437.4692
9826.125 405.3579848.512  387.399881.468354.53599914.424328.33289958.365279.1089
 9969.35273.76439991.321271.6812 10024.2272.946410035.16275.542310056.66290.0565
 10078.1300.855310099.54314.6428 10131.7338.000110142.42 351.46810163.86382.8455
10174.58392.145310217.46 404.59110271.76413.127510370.13422.495210400.97430.6724
#Mann= 3 , 0 , 0
9599.025  0.0751       09599.025  0.0751       010400.97  0.0751       0
#XS Ineff= 2 , 0
       0                               0
Bank Sta=9599.025,10400.97
Exp/Cntr=0.3,0.1

Type RM Length L Ch R = 1 ,17537.84,241.608500,241.608500,241.608500
XS GIS Cut Line= 6
667132.396897839 843550.05457719667247.883860278843496.375248544
667381.685371651843439.352390719667500.553942731843394.132170881
667618.268475529843350.460715285 667875.51592719843249.251424504
#Sta/Elev= 30
9599.022484.56889712.167454.0722 9734.11449.37089777.591433.59729788.462427.7383
9853.683389.78049864.553382.25639886.066362.10829896.765354.78869912.186340.1961
9950.261 307.9669971.659276.90829993.058267.0505 10014.4267.238810025.07 272.085
10035.73282.7523 10046.4291.406910057.07   303.5 10078.4323.830410099.73354.0421
10111.51364.993510142.53389.704310164.03402.225910185.52411.870810207.01 420.108
10217.76421.936410260.74424.694410346.71426.872910389.69440.1417   10401440.5739
#Mann= 3 , 0 , 0
9599.022  0.0448       09599.022  0.0448       0   10401  0.0448       0
#XS Ineff= 2 , 0
       0                               0
Bank Sta=9599.022,10401
Exp/Cntr=0.3,0.1

Type RM Length L Ch R = 1 ,17296.23,241.608600,241.608600,241.608600
XS GIS Cut Line= 6
667214.132542246843747.743164333667381.796470734843698.754370122
667462.856526649843671.854303841667532.277561401843644.459750636
 667739.54148494843554.285145577667966.594830055843472.950471763
#Sta/Elev= 30
9599.023531.73639620.763523.68239631.181523.17899641.599520.52279714.526494.9824
9756.198 479.3619773.697469.88589798.145448.79059819.217433.66489850.826404.0898
 9904.41371.5116 9915.16362.03849947.671322.48529969.579287.62589980.533272.6635
9991.487264.9614    9999264.824810013.42266.793310035.36293.0267 10057.3310.6465
10079.14326.227410105.53352.303810133.24 370.18510186.96390.273110208.31399.8434
10218.98406.153910261.67416.056510282.87427.750910293.46431.108710400.99 436.567
#Mann= 3 , 0 , 0
9599.023  0.0849       09599.023  0.0849       010400.99  0.0849       0
#XS Ineff= 2 , 0
       0                               0
Bank Sta=9599.023,10400.99
Exp/Cntr=0.3,0.1

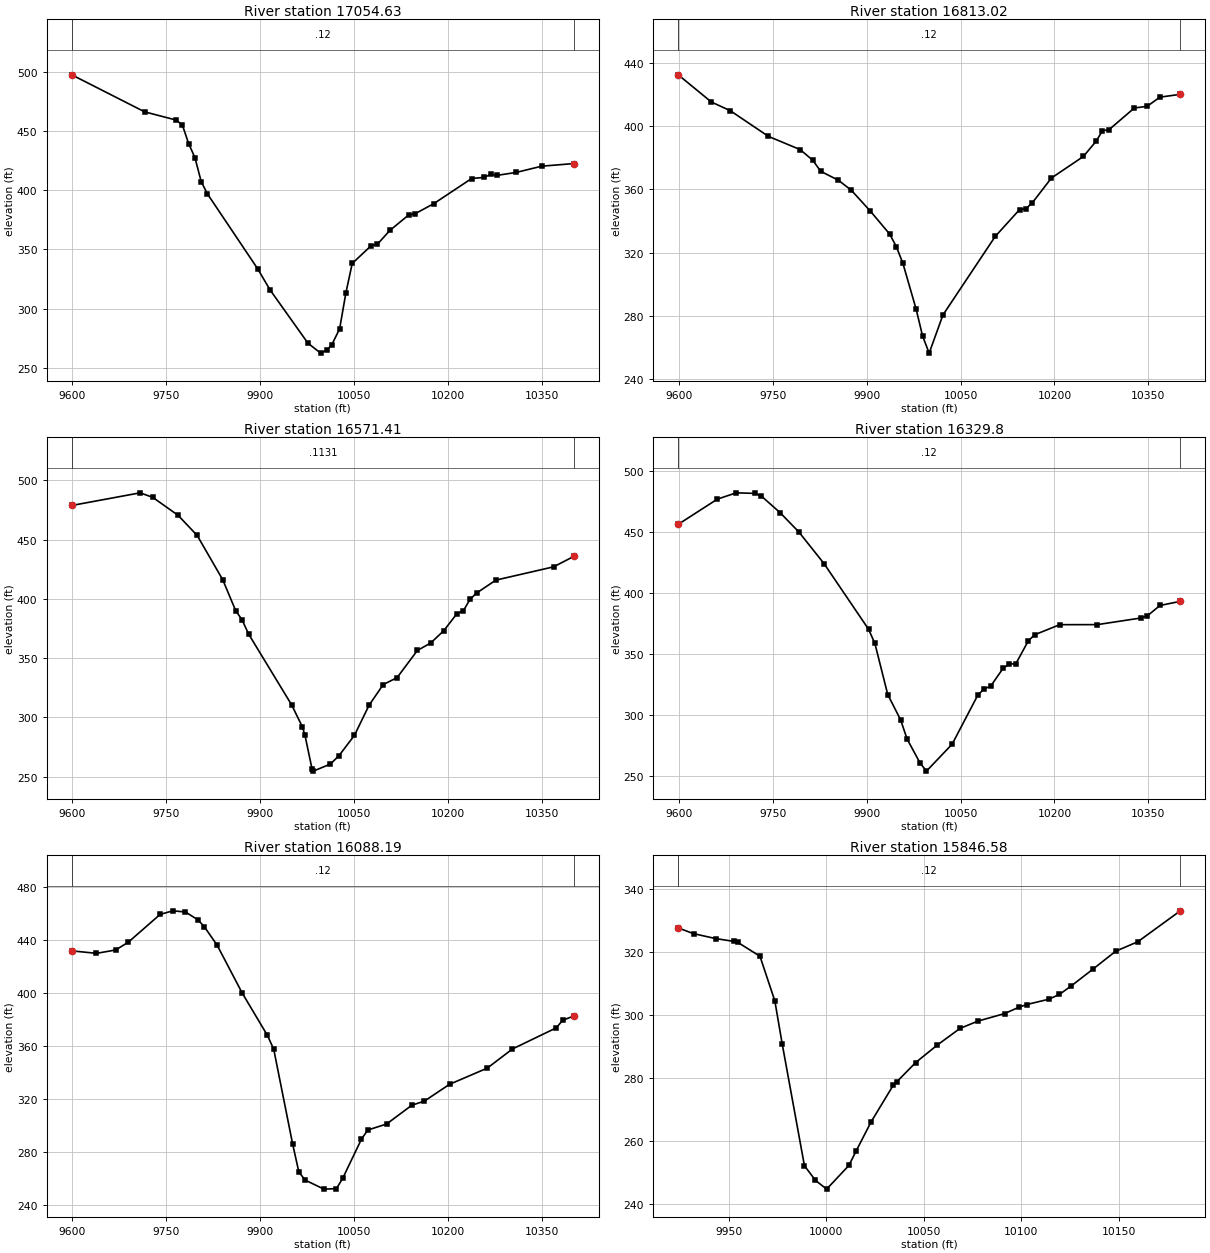
Type RM Length L Ch R = 1 ,17054.63,241.608600,241.608600,241.608600
XS GIS Cut Line= 6
667269.804819722  843855.6367819667514.319872475 843830.17203605
667602.850864564843833.442443052667726.717473982843849.934749487
667815.019769742843849.685831267668065.341425426843808.687222388
#Sta/Elev= 30
9599.047497.36119715.467466.09939765.684459.18679775.719455.00159785.753439.2154
9795.783427.40669805.789407.17039815.795396.78439895.822333.70669915.865315.6957
9976.319270.78289996.517262.411310006.64264.920410014.53269.682110026.87 282.914
10036.92313.446910046.97338.116110077.03353.040910087.04354.274410107.05365.9561
10137.07379.049810147.08380.002510177.21388.592810237.71409.828410257.95410.7969
10268.14413.365510278.33412.4908 10308.9414.965310349.66420.233310400.95422.4546
#Mann= 3 , 0 , 0
9599.047    0.12       09599.047    0.12       010400.95    0.12       0
#XS Ineff= 2 , 0
       0                               0
Bank Sta=9599.047,10400.95
Exp/Cntr=0.3,0.1

Type RM Length L Ch R = 1 ,16813.02,241.608600,241.608600,241.608600
XS GIS Cut Line= 6
667222.476101211844149.551626606667350.662185386844131.810665141
 667466.75817767844111.623549136667558.101162098844090.153984339
 667684.86342313844051.202392969 668007.06371427843988.779478019
#Sta/Elev= 30
9599.046432.33049652.071415.11939682.357409.61549743.007393.43689793.757385.0682
9814.058378.29749826.583371.34019854.759365.69339875.304359.44619906.121346.0735
9936.939331.56379947.364323.72479957.858313.19349978.846284.4381 9989.34267.1814
9999.837256.391310021.86280.521410105.39330.179810144.22347.117110154.41347.7309
 10164.6351.441810195.15367.094210246.08380.702210266.46390.310210276.64397.0505
10286.83397.549710327.57 411.37210347.94 412.39810368.32418.204310400.98419.9981
#Mann= 3 , 0 , 0
9599.046    0.12       09599.046    0.12       010400.98    0.12       0
#XS Ineff= 2 , 0
       0                               0
Bank Sta=9599.046,10400.98
Exp/Cntr=0.3,0.1

Type RM Length L Ch R = 1 ,16571.41,241.608500,241.608500,241.608500
XS GIS Cut Line= 6
667366.222471763 844373.80874698667646.877637218844331.904702527
667707.664250479844305.155957859667783.775754528844241.832689059
667856.398430716844203.891743137668116.659333113844134.532335988
#Sta/Elev= 30
9599.114 478.8949708.349 489.5629728.483485.71559768.903470.58099799.366453.5948
9840.164416.25759860.834390.20329871.169382.29649881.503370.38669950.257310.6203
9967.285292.18819971.409285.22519982.856256.46249984.826254.713610012.04260.6631
10025.52267.515110050.59284.959310073.91310.339310096.54327.785910118.62333.5973
10150.99356.516610172.27362.813510193.41 373.33410214.25387.629710224.66390.1825
10235.08 399.68110245.46404.921810276.34415.900710368.57427.100310400.92435.9368
#Mann= 3 , 0 , 0
9599.114  0.1131       09599.114  0.1131       010400.92  0.1131       0
#XS Ineff= 2 , 0
       0                               0
Bank Sta=9599.114,10400.92
Exp/Cntr=0.3,0.1

Type RM Length L Ch R = 1 , 16329.8,241.608600,241.608600,241.608600
XS GIS Cut Line= 6
667342.420553238844453.250715225667588.031511436844467.019853265
667809.582556076844515.558597533667896.378345785844527.573125604
668000.412294735 844530.96909607668137.430363743844525.107780396
#Sta/Elev= 30
9599.055456.27649661.675476.90899691.695482.03849721.714481.57199731.721479.4152
9761.775465.79429791.892449.89859832.047424.05879902.982370.47369913.137358.8062
9933.644317.04729954.252296.30449964.556 280.6359985.163261.12479995.467254.3661
10036.55276.440110077.53 316.54810087.67321.749110097.81323.674310118.05338.5933
10128.11342.005110138.18342.1427 10158.3361.051110168.33365.914410208.39374.1786
 10268.4374.218610338.46379.673310348.47381.472610368.49389.878710400.95 393.276
#Mann= 3 , 0 , 0
9599.055    0.12       09599.055    0.12       010400.95    0.12       0
#XS Ineff= 2 , 0
       0                               0
Bank Sta=9599.055,10400.95
Exp/Cntr=0.3,0.1

Type RM Length L Ch R = 1 ,16088.19,241.608600,241.608600,241.608600
XS GIS Cut Line= 6
667296.207693229844683.617776338667421.379127216844707.105128028
667523.544019273844722.664961004667709.864321698844736.888657247
667781.035673208844734.827019425668092.783074837844705.612796176
#Sta/Elev= 30
9599.022431.51979638.491429.63749669.015432.15639689.364438.06159740.156459.0339
9760.386461.73069780.617460.86169800.848454.82949810.963449.57299831.184435.7983
9871.381399.55299911.578 367.6589921.598357.23819951.655286.04459961.674264.6714
9971.692258.507210001.75251.644610021.76252.008210031.77259.801510061.78 289.426
10071.78296.246910101.86300.790210142.08314.953310162.18318.0768 10202.4330.7647
10262.71342.991410302.85357.436610373.08373.431110383.11379.153510400.96382.3095
#Mann= 3 , 0 , 0
9599.022    0.12       09599.022    0.12       010400.96    0.12       0
#XS Ineff= 2 , 0
       0                               0
Bank Sta=9599.022,10400.96
Exp/Cntr=0.3,0.1

Type RM Length L Ch R = 1 ,15846.58,88.069600,88.069600,88.069600
XS GIS Cut Line= 2
667718.228609562844988.762686059667944.090993285844865.244418606
#Sta/Elev= 30
9924.091327.67439931.933325.86999943.207324.30689952.775323.39099954.604323.1113
9966.002 318.6829973.616304.5277  9977.4290.85639988.797252.19389994.458247.5292
10000.19244.761410011.59252.2722 10015.3256.870310022.99266.123410034.39277.7953
10036.14278.832510045.79 284.92510056.98290.529110068.58295.791510077.82298.1165
10091.38300.479510098.67302.480210102.77303.356310114.17305.059110119.51306.5732
10125.57309.255810136.97314.715510148.36320.271710159.76323.310110181.52333.1101
#Mann= 3 , 0 , 0
9924.091    0.12       09924.091    0.12       010181.52    0.12       0
#XS Ineff= 2 , 0
       0                               0
Bank Sta=9924.091,10181.52
Exp/Cntr=0.3,0.1

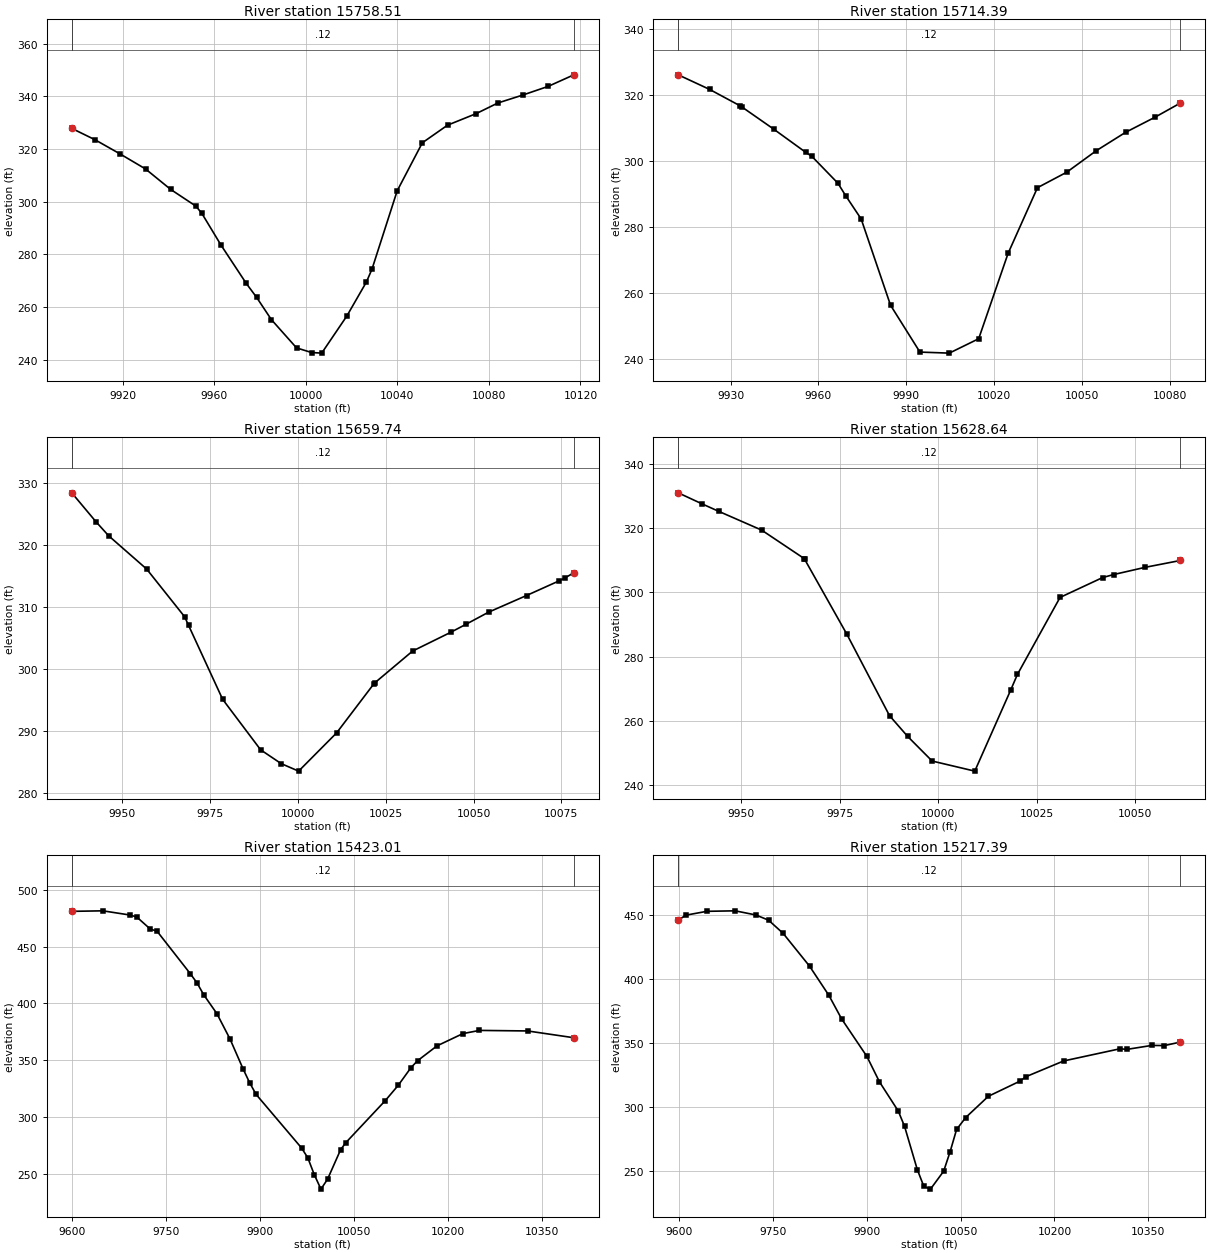
Type RM Length L Ch R = 1 ,15758.51,44.124500,44.124500,44.124500
XS GIS Cut Line= 2
667715.687043011 844991.30425255667915.200013787845082.800646797
#Sta/Elev= 25
9897.629327.78919907.875323.43479918.876 318.0279929.878312.38289940.879304.6136
9951.881298.28039954.474295.54619962.882283.46329973.884268.97149978.463263.6061
9984.885   255.29995.886244.462810002.45242.706910006.89242.473510017.89256.5706
10026.44269.483310028.89 274.39610039.89304.089110050.89322.325110061.89329.0005
10074.42333.3918 10083.9 337.425 10094.9340.4719 10105.9343.737210117.12348.1184
#Mann= 3 , 0 , 0
9897.629    0.12       09897.629    0.12       010117.12    0.12       0
#XS Ineff= 2 , 0
       0                               0
Bank Sta=9897.629,10117.12
Exp/Cntr=0.3,0.1

Type RM Length L Ch R = 1 ,15714.39,54.644100,54.644100,54.644100
XS GIS Cut Line= 3
667715.263448626844996.387385592667767.365562022845019.685078546
667774.990261495845133.631976902
#Sta/Elev= 21
9912.159 326.1929922.825321.79079933.258 316.8069933.779316.51459944.733 309.729
9955.687302.68029957.756301.47549966.642293.33059969.233289.6194 9974.56 282.506
9984.582256.36699994.604242.166910004.63241.852610014.65246.214710024.67272.0631
10034.69291.983510044.72296.698210054.74 303.18210064.76308.763310074.78 313.339
10083.43317.6293
#Mann= 3 , 0 , 0
9912.159    0.12       09912.159    0.12       010083.43    0.12       0
#XS Ineff= 2 , 0
       0                               0
Bank Sta=9912.159,10083.43
Exp/Cntr=0.3,0.1

Type RM Length L Ch R = 1 ,15659.74,31.105400,31.105400,31.105400
XS GIS Cut Line= 2
667692.389350057845005.282868356667746.609435529845137.444326684
#Sta/Elev= 21
9935.695328.46839942.573323.80429946.198321.52569957.006316.15399967.815308.4454
9968.919307.07119978.624295.11869989.433286.96459995.266284.739610000.24 283.523
10011.05289.699310021.61297.591610021.86297.755410032.67302.913510043.48305.9314
10047.96307.267410054.29309.194410065.09311.885410074.31314.2402 10075.9314.6888
10078.55315.5549
#Mann= 3 , 0 , 0
9935.695    0.12       09935.695    0.12       010078.55    0.12       0
#XS Ineff= 2 , 0
       0                               0
Bank Sta=9935.695,10078.55
Exp/Cntr=0.3,0.1

Type RM Length L Ch R = 1 ,15628.64,205.623900,205.623900,205.623900
XS GIS Cut Line= 2
667662.737740844 845015.44913438 667711.45109883845133.208382487
#Sta/Elev= 18
9934.061 330.966 9939.98327.59979944.397325.17629955.219319.37689966.041310.5059
 9966.14310.30269976.863286.97219987.685261.64629992.301255.17069998.506 247.521
10009.33244.381610018.46269.637810020.15274.458410030.97298.421310041.79304.6081
10044.62305.552510052.62307.7985 10061.5309.9127
#Mann= 3 , 0 , 0
9934.061    0.12       09934.061    0.12       0 10061.5    0.12       0
#XS Ineff= 2 , 0
       0                               0
Bank Sta=9934.061,10061.5
Exp/Cntr=0.3,0.1

Type RM Length L Ch R = 1 ,15423.01,205.623900,205.623900,205.623900
XS GIS Cut Line= 6
667189.089523187845095.246287576667326.352649106845151.843891533
667442.014916884845190.955561933 667592.74352365845232.872701613
667692.682368301845253.318591874667957.113862887845320.094897341
#Sta/Elev= 30
9599.038481.14679648.698481.60119691.965477.90389702.781476.18059724.415465.5449
9735.232463.64789788.603426.01769799.235417.92689809.867 407.5479830.835390.9973
9851.799368.62079872.717342.22829883.043330.2081 9893.37 319.8669966.056 272.601
9975.979 263.9949986.493248.9407 9997.01236.337310007.54245.044210028.45271.1118
10036.76277.2946 10099.9314.422210120.31 327.71410140.91 343.45610151.27349.4675
10182.33362.570410223.75373.395410250.22376.212210327.07375.735110400.95369.7548
#Mann= 3 , 0 , 0
9599.038    0.12       09599.038    0.12       010400.95    0.12       0
#XS Ineff= 2 , 0
       0                               0
Bank Sta=9599.038,10400.95
Exp/Cntr=0.3,0.1

Type RM Length L Ch R = 1 ,15217.39,205.623900,205.623900,205.623900
XS GIS Cut Line= 6
667224.518780421845330.682869953667366.636785802845400.918487267
667488.052565811845432.086281733667563.001144528845432.915435987
667743.206747255845398.518012098668000.315538844845419.453261851
#Sta/Elev= 30
9599.131445.70639610.989449.6894 9644.93452.72999690.155453.11039723.049449.8775
9743.306445.83929766.621435.54149808.824409.93859839.748387.12929860.043368.7876
 9900.41339.49859920.442319.69959950.485 296.9049960.532284.97719980.918251.1724
9991.424238.026710001.96235.950510023.02249.955510033.37265.235410043.65282.5199
10058.19291.798510094.41308.404110144.55320.137610154.55323.706310214.59335.9579
10305.04345.5154 10315.1344.955710355.34348.084610375.47347.969810400.94350.6801
#Mann= 3 , 0 , 0
9599.131    0.12       09599.131    0.12       010400.94    0.12       0
#XS Ineff= 2 , 0
       0                               0
Bank Sta=9599.131,10400.94
Exp/Cntr=0.3,0.1