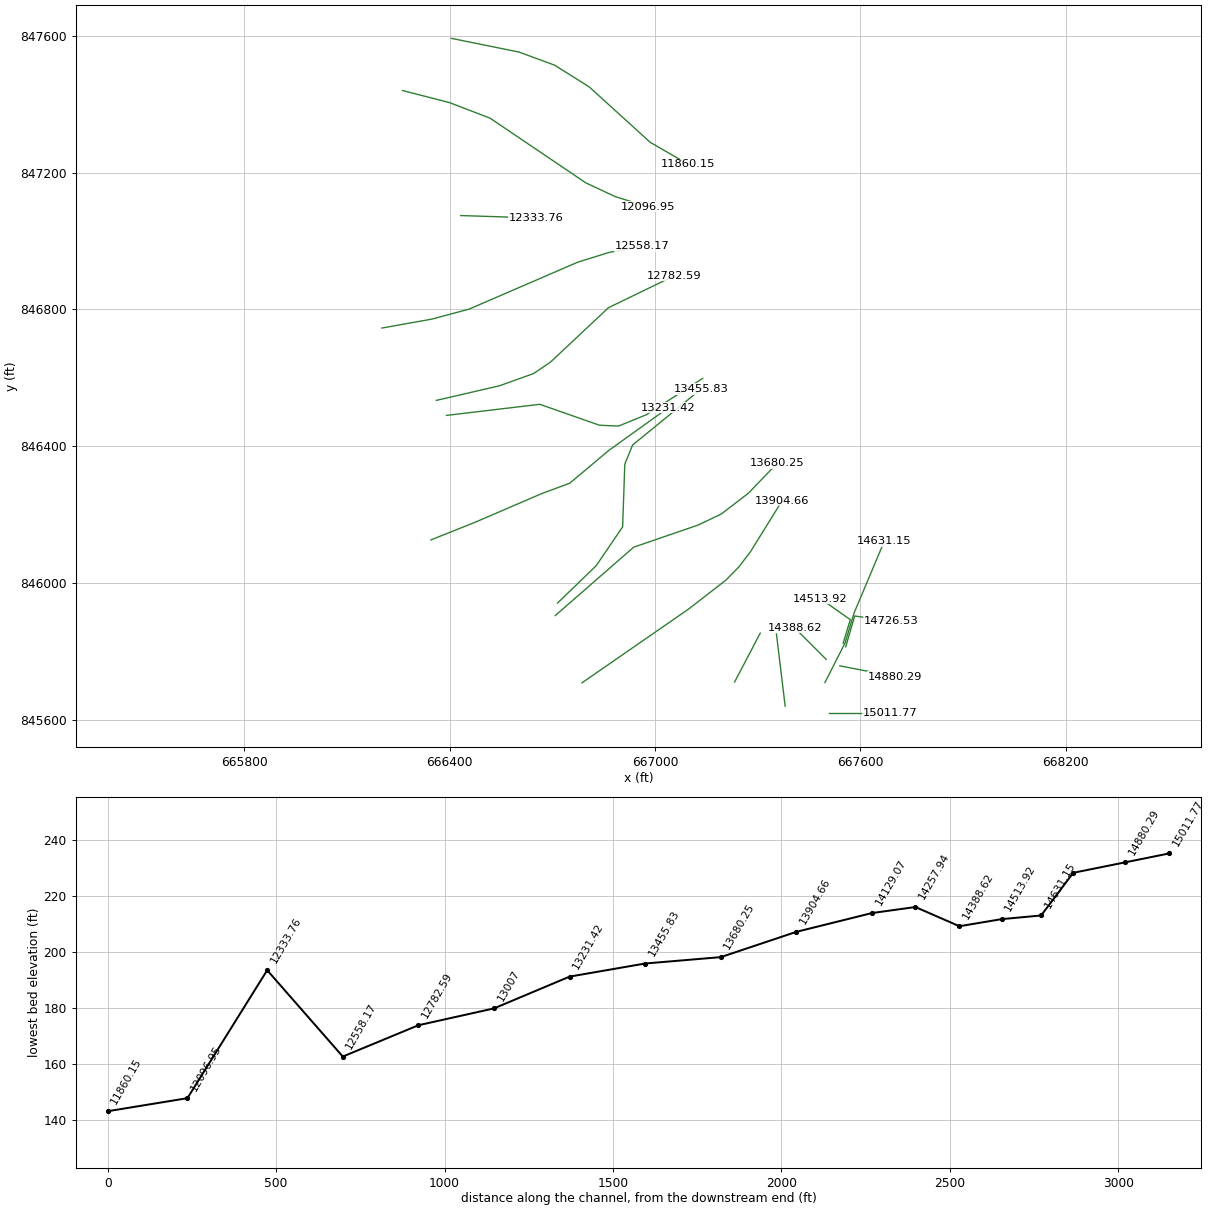
HEC-RAS study 13678_ras.prj: 13678

--- 13678_ras.g01 (geometry) --- (continued)

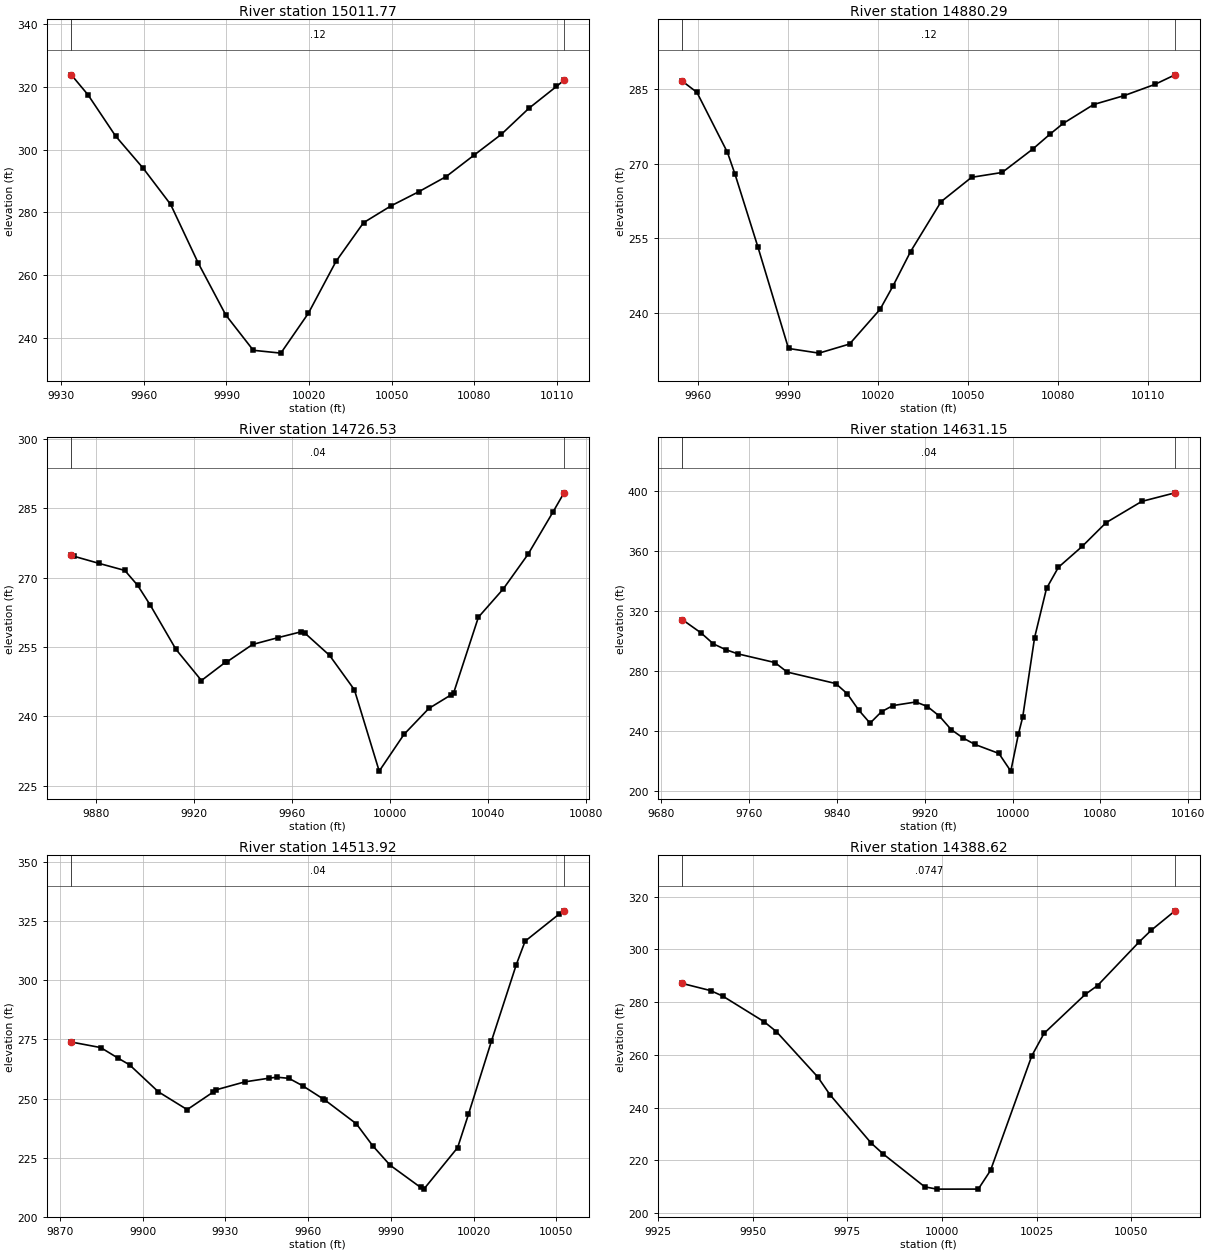
Type RM Length L Ch R = 1 ,15011.77,131.476900,131.476900,131.476900
XS GIS Cut Line= 2
667508.951365501845619.459320605667687.770809919845619.459320605
#Sta/Elev= 20
9933.689323.88619939.738317.52059949.738304.37989959.738294.11399969.738282.5341
9979.738263.85369989.738247.26989999.738235.984510009.74 235.08110019.74247.8229
10029.74264.331810039.74276.699510049.74282.080510059.74286.559210069.74 291.422
10079.74298.178910089.74 304.88610099.74313.189110109.74320.165510112.51 322.151
#Mann= 3 , 0 , 0
9933.689    0.12       09933.689    0.12       010112.51    0.12       0
#XS Ineff= 2 , 0
       0                               0
Bank Sta=9933.689,10112.51
Exp/Cntr=0.3,0.1

Type RM Length L Ch R = 1 ,14880.29,153.759500,153.759500,153.759500
XS GIS Cut Line= 2
667540.201365501845758.348209515667701.659698814845727.098209485
#Sta/Elev= 21
9954.664286.63589959.552284.38499969.738272.29059972.285267.85679979.923253.2107
9990.109232.828410000.29231.889310010.48 233.71810020.67 240.70510024.91245.3202
10030.85252.329510041.04262.385110051.22267.282810061.41268.258610071.59272.9496
10077.54276.047610081.78278.128310091.96281.941110102.15283.732710112.34285.9751
10119.12287.9161
#Mann= 3 , 0 , 0
9954.664    0.12       09954.664    0.12       010119.12    0.12       0
#XS Ineff= 2 , 0
       0                               0
Bank Sta=9954.664,10119.12
Exp/Cntr=0.3,0.1

Type RM Length L Ch R = 1 ,14726.53,95.383000,95.383000,95.383000
XS GIS Cut Line= 3
667557.432232797845814.040020823667583.667959958845904.183288515
667689.523614407845888.047394842
#Sta/Elev= 26
 9869.96274.79199870.959274.63239881.374 273.0669891.789271.55449897.041268.3214
9902.204264.02479912.619254.51359923.034247.76029932.825251.70889933.449251.7974
9943.864255.54699954.279257.02729963.843258.31189965.191258.02339975.306253.1882
9985.422245.75319995.537228.169210005.65236.113810015.77 241.71510024.78244.6374
10025.88245.0503   10036261.453510046.11 267.53910056.23275.043310066.35284.1278
10070.92288.3354
#Mann= 3 , 0 , 0
 9869.96    0.04       0 9869.96    0.04       010070.92    0.04       0
#XS Ineff= 2 , 0
       09958.797                       0
Bank Sta=9869.96,10070.92
Exp/Cntr=0.3,0.1

Type RM Length L Ch R = 1 ,14631.15,117.229300,117.229300,117.229300
XS GIS Cut Line= 4
667496.798587739845709.737098381667555.826365501845826.056542814
667581.868032157845912.862098381667670.409698814846122.931542829
#Sta/Elev= 30
9698.967314.27839716.083 305.3629727.296298.0529 9738.51294.19849749.724291.3598
9783.366 285.571 9794.58279.19589838.744271.54729849.184264.79969859.624253.8809
9870.065245.03169880.505 252.7049890.945256.81319911.826259.20339922.354256.1691
9933.206 249.7929944.058240.7037 9954.91 235.0919965.762230.78419987.466224.7927
9998.318212.967610005.34237.946310009.17249.052310020.02302.256310030.87335.1383
10041.73349.279510063.43363.263210085.13379.097410117.69393.3258   10148 399.061
#Mann= 3 , 0 , 0
9698.967    0.04       09698.967    0.04       0   10148    0.04       0
#XS Ineff= 2 , 0
       09904.307                       0
Bank Sta=9698.967,10148
Exp/Cntr=0.3,0.1

Type RM Length L Ch R = 1 ,14513.92,125.298500,125.298500,125.298500
XS GIS Cut Line= 4
 667550.03241232845824.803396061 667570.88645184845893.419913247
667560.931589365845900.339577615667483.468926907 845954.97113952
#Sta/Elev= 28
9874.132273.90039874.338273.86659884.789271.57269891.215 267.0069895.241264.2786
9905.692252.85169916.144245.31169925.604252.77679926.596 253.6859937.047257.0577
9945.848258.61949948.616 259.0359953.016258.55049957.971255.4341 9965.23249.9832
9966.057249.37679977.466239.31929983.408230.00899989.703221.793410000.76212.3944
10001.94211.663310014.18229.219310018.11243.303310026.41274.182610035.46306.6841
10038.65316.593210050.89327.971910052.76329.4423
#Mann= 3 , 0 , 0
9874.132    0.04       09874.132    0.04       010052.76    0.04       0
#XS Ineff= 2 , 0
       09948.685                       0
Bank Sta=9874.132,10052.76
Exp/Cntr=0.3,0.1

Type RM Length L Ch R = 1 ,14388.62,130.681400,130.681400,130.681400
XS GIS Cut Line= 2
667500.270809919845777.445431724667408.256921023 845869.45932059
#Sta/Elev= 20
9931.381287.11759938.835284.41869942.065282.32529952.977272.62079956.207268.8922
9967.119251.72379970.349244.99269981.262226.59329984.491222.39699995.404210.0014
9998.633209.134710009.55209.146410012.78216.224110023.69259.704610026.92268.2015
10037.83 283.00710041.06286.339510051.97302.7721 10055.2307.265110061.51314.6588
#Mann= 3 , 0 , 0
9931.381  0.0747       09931.381  0.0747       010061.51  0.0747       0
#XS Ineff= 2 , 0
       0                               0
Bank Sta=9931.381,10061.51
Exp/Cntr=0.3,0.1

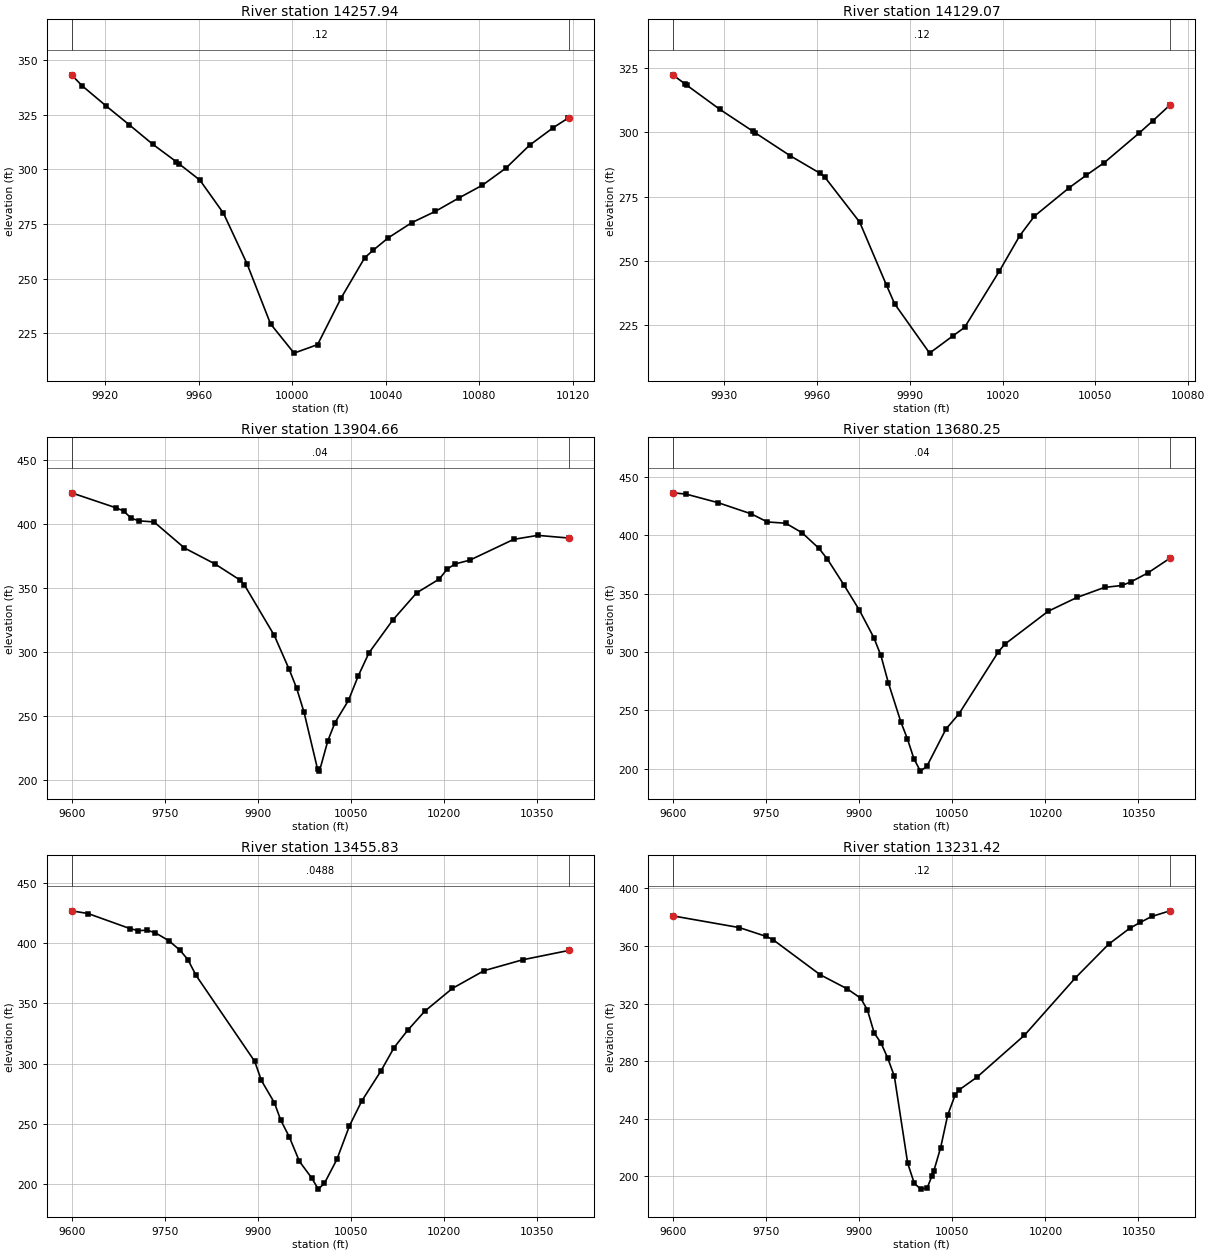
Type RM Length L Ch R = 1 ,14257.94,128.864700,128.864700,128.864700
XS GIS Cut Line= 2
667380.509252131845640.480594963667354.946235955845851.711834162
#Sta/Elev= 26
 9905.57 343.2769910.122338.25189920.195 329.1959930.268320.41859940.341311.4992
9950.414303.52039951.426302.68269960.487295.1184 9970.56 279.9929980.633256.9133
9990.706229.375610000.78215.975110010.85219.867310020.93241.2184   10031259.6057
10034.66263.065210041.07268.711310051.14275.659510061.22280.809710071.29286.9399
10081.36292.795610091.44300.613110101.51311.058110111.58319.0391 10117.9323.3913
10118.34323.6967
#Mann= 3 , 0 , 0
 9905.57    0.12       0 9905.57    0.12       010118.34    0.12       0
#XS Ineff= 2 , 0
       0                               0
Bank Sta=9905.57,10118.34
Exp/Cntr=0.3,0.1

Type RM Length L Ch R = 1 ,14129.07,224.414300,224.414300,224.414300
XS GIS Cut Line= 2
667232.909698844845711.473209485667307.562476605 845853.83432059
#Sta/Elev= 24
9913.381322.52289917.363318.96379917.882318.49299928.655308.99219939.415300.3908
9939.947 299.9489951.238290.99529960.948284.1056 9962.53282.57579973.821264.9587
 9982.48240.33169985.113233.06619996.404 213.83110004.01220.6263 10007.7223.8438
10018.99245.938810025.55259.699310030.28267.315310041.57278.472210047.08283.3332
10052.86288.220410064.15299.781310068.61304.617210074.13310.7542
#Mann= 3 , 0 , 0
9913.381    0.12       09913.381    0.12       010074.13    0.12       0
#XS Ineff= 2 , 0
       0                               0
Bank Sta=9913.381,10074.13
Exp/Cntr=0.3,0.1

Type RM Length L Ch R = 1 ,13904.66,224.414200,224.414200,224.414200
XS GIS Cut Line= 6
666786.739586954 845708.74418808667098.494676013845924.511549932
667207.843065855846009.312324905667245.291259099846047.700001515
667279.295991872846092.207642939 667371.43292185846240.584286119
#Sta/Elev= 30
9599.016424.69979670.594413.0168 9682.88410.51029695.166404.93019707.451402.8058
9732.023401.94479781.167381.5555 9829.84369.23799870.824356.49029877.896352.6092
9925.951313.23079949.979286.65529961.992271.97419974.006253.02179995.753208.6543
9998.791 207.13610012.34230.911310023.88245.0996 10045.5262.380510061.49281.7212
10078.66299.631610116.62 324.98810155.51346.505810192.02357.3063 10204.6 364.981
10217.19 369.04910241.31372.070310311.94388.308210350.81391.448710400.91389.3474
#Mann= 3 , 0 , 0
9599.016    0.04       09599.016    0.04       010400.91    0.04       0
#XS Ineff= 2 , 0
       0                               0
Bank Sta=9599.016,10400.91
Exp/Cntr=0.3,0.1

Type RM Length L Ch R = 1 ,13680.25,224.414300,224.414300,224.414300
XS GIS Cut Line= 6
666708.520335087845905.265585958666937.825441934846105.150169662
667126.258321507846169.865813261667193.564967325846202.028577439
667272.773826784846262.661997778667357.923796264 846351.12960289
#Sta/Elev= 30
  9599.1436.11549620.525435.04189672.529427.63389725.781418.10269751.778411.1827
9781.176410.14239807.646401.96689834.934388.55019848.578379.32759874.677357.7079
9899.916335.86549923.378312.21279934.696297.0225 9946.62273.81739966.945240.1222
9977.406225.75919987.867208.85099998.329198.126210008.74202.178610039.71 234.186
10060.36246.965510123.81299.901210134.62306.723410204.31334.8178   10251346.6824
10295.27355.251110323.36356.8736   10338360.029710365.28367.655910400.91380.2454
#Mann= 3 , 0 , 0
  9599.1    0.04       0  9599.1    0.04       010400.91    0.04       0
#XS Ineff= 2 , 0
       0                               0
Bank Sta=9599.1,10400.91
Exp/Cntr=0.3,0.1

Type RM Length L Ch R = 1 ,13455.83,224.414200,224.414200,224.414200
XS GIS Cut Line= 6
666715.277312559 845941.94164469666828.204486286846050.994598479
666905.451414409  846164.5176481666911.825559448846347.748928937
666934.505366957846403.682121687667135.227361469846567.653585554
#Sta/Elev= 30
9599.206426.58329625.709424.35759693.097411.91429706.844410.10679720.591410.5484
9734.339408.37749756.327401.73059774.082393.87619786.759 386.1459799.923 373.057
9894.512301.74019905.213285.96939926.278267.39079936.425253.03589949.986239.4178
9966.629218.77239986.733204.84679996.812195.854810006.88200.704810027.01220.5805
10047.14248.281510067.15269.028710097.69293.631810119.21313.256810140.78  327.39
10168.49343.316910213.17362.280910264.22376.9719 10326.7386.027610400.81393.7452
#Mann= 3 , 0 , 0
9599.206  0.0488       09599.206  0.0488       010400.81  0.0488       0
#XS Ineff= 2 , 0
       0                               0
Bank Sta=9599.206,10400.81
Exp/Cntr=0.3,0.1

Type RM Length L Ch R = 1 ,13231.42,224.414300,224.414300,224.414300
XS GIS Cut Line= 6
666345.215179637846126.437024052666475.748899106846178.543917229
666667.739482102846261.198762125666751.227550618846292.363171512
666865.414797751846388.262914235667039.173973778846512.788827134
#Sta/Elev= 30
9599.019380.8306 9706.46372.68089749.641366.56289760.528364.3432 9836.74339.9718
9880.289330.18369902.064323.68739912.951315.47729923.838299.55899934.726292.6796
9945.613 282.1959956.373269.46149977.797209.27189988.434195.22829998.907191.1817
10009.36192.121510016.62199.963810020.01203.836910030.98219.976310042.38 242.628
 10054.5256.637910060.21259.866210089.63268.910410166.03297.927810248.14337.7286
 10301.7361.089910336.03372.2581 10353.2376.338610371.17380.389710400.91384.3181
#Mann= 3 , 0 , 0
9599.019    0.12       09599.019    0.12       010400.91    0.12       0
#XS Ineff= 2 , 0
       0                               0
Bank Sta=9599.019,10400.91
Exp/Cntr=0.3,0.1

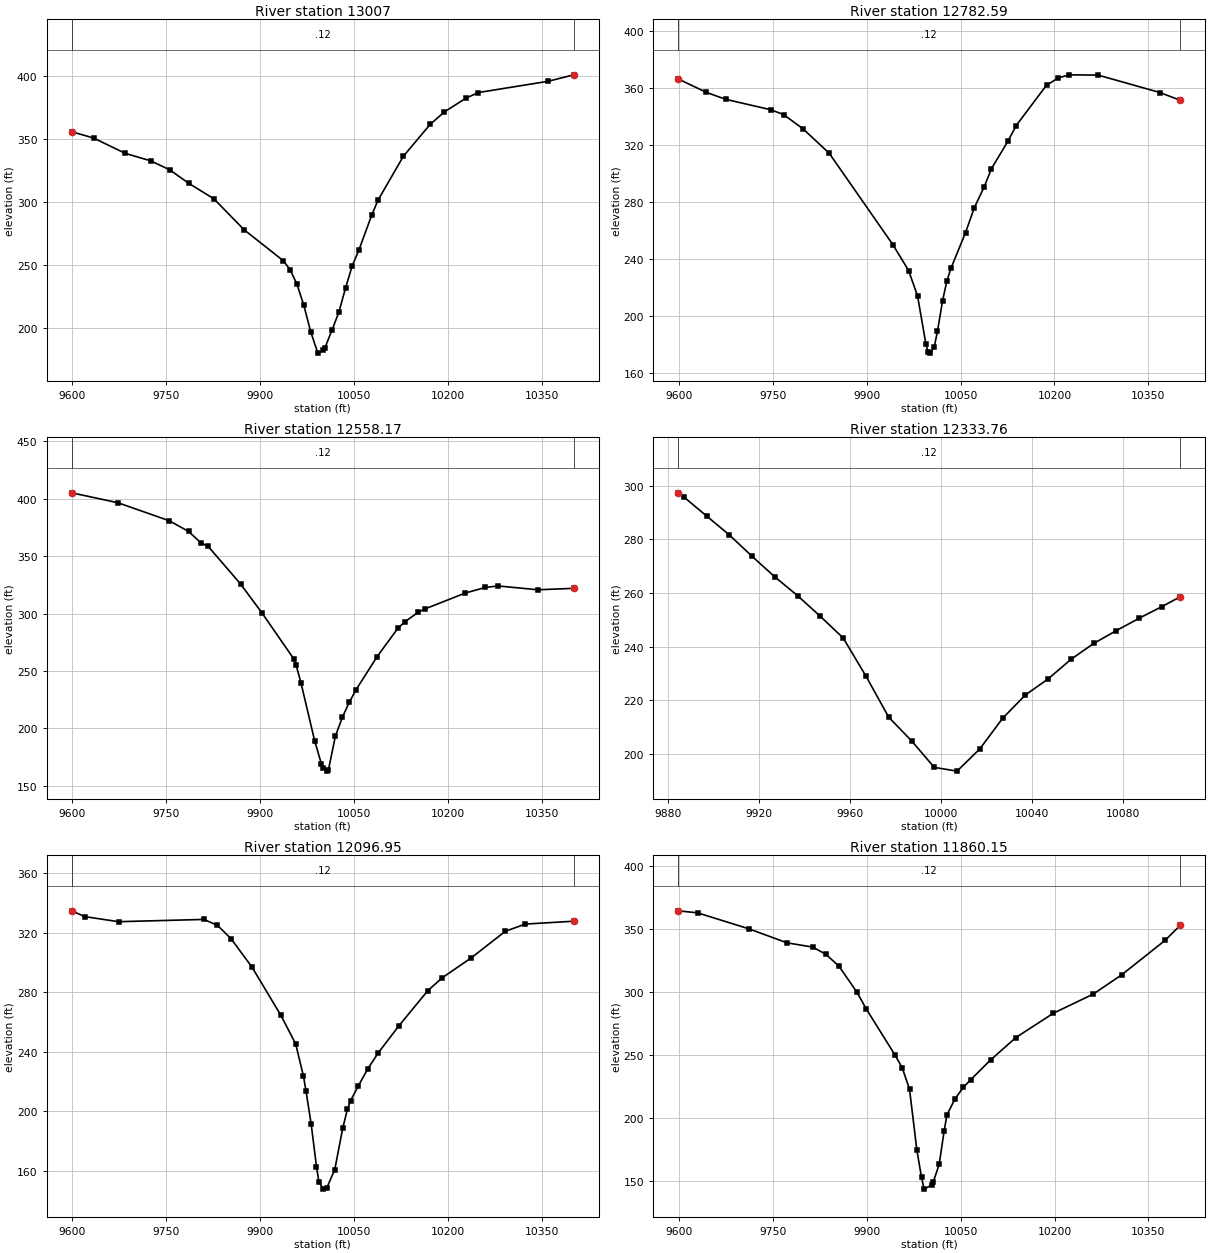
Type RM Length L Ch R = 1 ,   13007,224.414300,224.414300,224.414300
XS GIS Cut Line= 6
666390.745764964846490.320291554666663.528166057846522.683081575
666837.574915653846461.638382301666893.380559976846459.091855321
666974.735135433846492.185294117667139.450455139846598.581437726
#Sta/Elev= 30
9599.109  355.589633.946350.56189684.798338.35339725.287332.46219755.609325.3265
9785.796314.66539825.937302.37489874.469277.69069937.169253.07639947.862245.9007
9958.661234.59459969.498218.0206 9980.75196.62149992.003179.8552   10001182.1281
10003.23183.935910014.39197.843110025.55212.340610036.32231.692810046.94249.2183
10057.56261.664710077.94289.268910088.06301.264810128.61336.141810171.44 361.475
10193.77371.195310228.38382.206110248.46 386.69410359.44395.596210400.76400.7446
#Mann= 3 , 0 , 0
9599.109    0.12       09599.109    0.12       010400.76    0.12       0
#XS Ineff= 2 , 0
       0                               0
Bank Sta=9599.109,10400.76
Exp/Cntr=0.3,0.1

Type RM Length L Ch R = 1 ,12782.59,224.414200,224.414200,224.414200
XS GIS Cut Line= 6
 666361.11537506846534.186674671666545.542374232846576.823705932
666644.743001457 846612.40874661666694.811215139846646.146457888
666863.948570307846804.972903652667055.701248344846897.944220245
#Sta/Elev= 30
9599.101366.31469644.038356.89929674.757 352.046 9746.63344.7342 9767.24341.3407
9798.306331.34969840.164 314.208 9941.98 249.9429967.045231.80879981.289213.9963
9994.653180.19359997.983174.8423   10001173.857510007.96178.140810013.13189.2891
 10021.3210.750610028.24224.755410034.64233.409210057.89258.440910071.97275.9743
10087.86290.681310099.32303.376310125.64322.6556 10138.8333.593610187.23361.9198
10206.27367.074710223.67369.223810269.72369.022410368.35 356.80110400.93351.3171
#Mann= 3 , 0 , 0
9599.101    0.12       09599.101    0.12       010400.93    0.12       0
#XS Ineff= 2 , 0
       0                               0
Bank Sta=9599.101,10400.93
Exp/Cntr=0.3,0.1

Type RM Length L Ch R = 1 ,12558.17,224.414300,224.414300,224.414300
XS GIS Cut Line= 6
 666201.96134578  846745.5948544666347.028171291846771.526814659
 666456.66615316846800.839945461666773.926787716846937.935264385
 666864.63269568846966.222895347 666962.88056528846985.159713856
#Sta/Elev= 30
9599.031 405.2039672.999396.52059754.626380.89089785.497371.58039806.117361.2193
9816.535358.77039868.772325.66729902.791300.59129954.239260.01979957.527254.7842
9965.037239.86079986.918189.21679997.888168.7888   10001165.680610006.65162.6979
10008.98163.706110020.06193.191410031.15209.475610042.23222.6747   10053233.5438
10086.57262.337710119.83287.107910130.91292.771810152.81301.298510163.64304.1261
10227.33317.8347 10259.7322.799810280.48324.028610343.26320.739710400.97 321.968
#Mann= 3 , 0 , 0
9599.031    0.12       09599.031    0.12       010400.97    0.12       0
#XS Ineff= 2 , 0
       0                               0
Bank Sta=9599.031,10400.97
Exp/Cntr=0.3,0.1

Type RM Length L Ch R = 1 ,12333.76,236.806300,236.806300,236.806300
XS GIS Cut Line= 2
666432.562476605847074.320431709 666653.04858771847067.375987262
#Sta/Elev= 24
9884.595297.39039887.033295.84849897.038288.75019907.043281.66759917.048 273.672
9927.053265.99019937.058258.96219947.063251.23629957.068243.19559967.073228.9475
9977.078213.59389987.083204.79229997.088194.865910007.09193.4649 10017.1201.7656
 10027.1213.172110037.11221.894810047.11227.892710057.12235.186110067.12 241.136
10077.13245.967210087.13250.550610097.14254.940110105.19258.5717
#Mann= 3 , 0 , 0
9884.595    0.12       09884.595    0.12       010105.19    0.12       0
#XS Ineff= 2 , 0
       0                               0
Bank Sta=9884.595,10105.19
Exp/Cntr=0.3,0.1

Type RM Length L Ch R = 1 ,12096.95,236.806400,236.806400,236.806400
XS GIS Cut Line= 6
666262.354203201847439.760745676666399.091841177 847404.57789438
666518.064043059847358.979958434666797.602380468847170.104655553
666883.624620025847129.801793812666979.124461358847100.037276898
#Sta/Elev= 30
9599.073334.59859619.755330.7133 9673.76 327.307 9810.04328.82599831.741324.8551
 9853.55 315.8369886.947296.81119932.918 264.5569956.596245.40399969.025223.7912
9973.055214.04539981.453191.43019989.896163.00779993.881152.5231   10001147.8711
10006.41148.741410019.12 161.01510031.74188.574410039.19 201.36410044.36207.2015
10056.98217.370210071.98228.674210088.37 239.17510121.55257.476710167.78281.0699
10191.11289.792910236.63302.902910291.47320.863510323.42325.711310400.94327.6336
#Mann= 3 , 0 , 0
9599.073    0.12       09599.073    0.12       010400.94    0.12       0
#XS Ineff= 2 , 0
       0                               0
Bank Sta=9599.073,10400.94
Exp/Cntr=0.3,0.1

Type RM Length L Ch R = 1 ,11860.15,236.806300,236.806300,236.806300
XS GIS Cut Line= 6
666404.710409046847592.284539804666602.561418016847552.179544126
666706.698281094847513.862739805 666807.66607389847450.481676152
666986.220555438847288.383087671667096.892690988847224.300913384
#Sta/Elev= 30
9599.089364.26959629.923362.68579711.361350.05729772.738338.87259813.994335.4283
9834.904329.73489855.813320.26169884.547299.57859899.364286.32169945.163249.8494
9956.828239.53899968.493222.49569980.158174.33079987.631152.48699991.823143.2197
10003.62146.428510006.37148.825810015.89163.073410023.63189.088710028.16 202.099
 10041.3215.123110054.56224.129910065.97230.034410097.89245.816510138.39263.6344
10198.34282.979410261.98298.164910307.28313.429110376.53 340.78710400.92352.8001
#Mann= 3 , 0 , 0
9599.089    0.12       09599.089    0.12       010400.92    0.12       0
#XS Ineff= 2 , 0
       0                               0
Bank Sta=9599.089,10400.92
Exp/Cntr=0.3,0.1