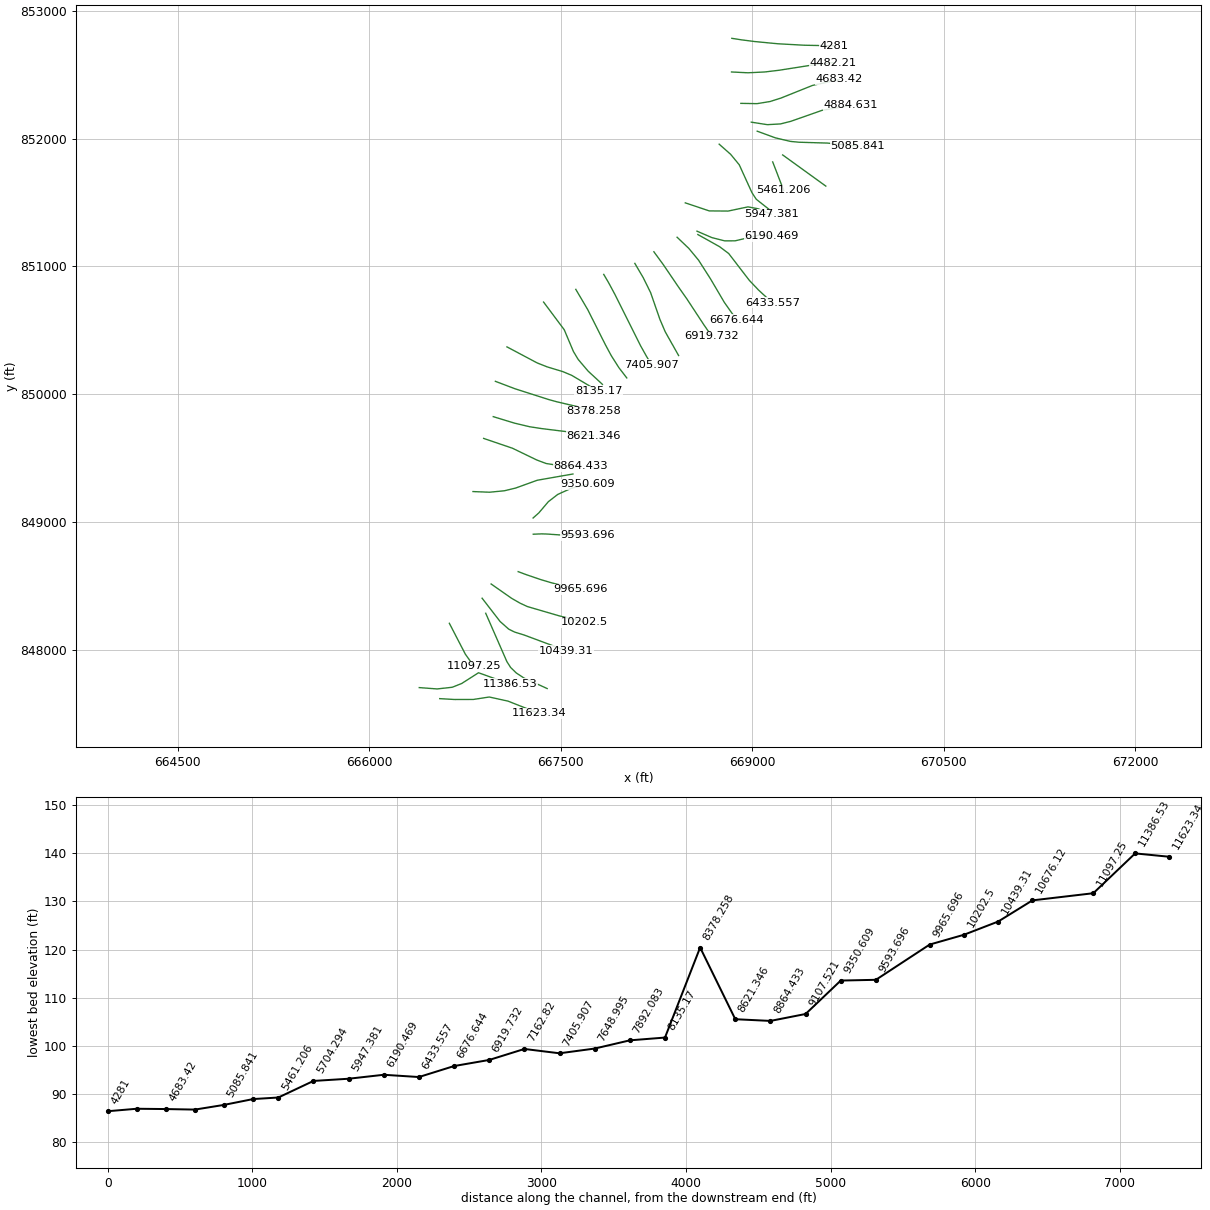
HEC-RAS study 13678_ras.prj: 13678

--- 13678_ras.g01 (geometry) --- (continued)

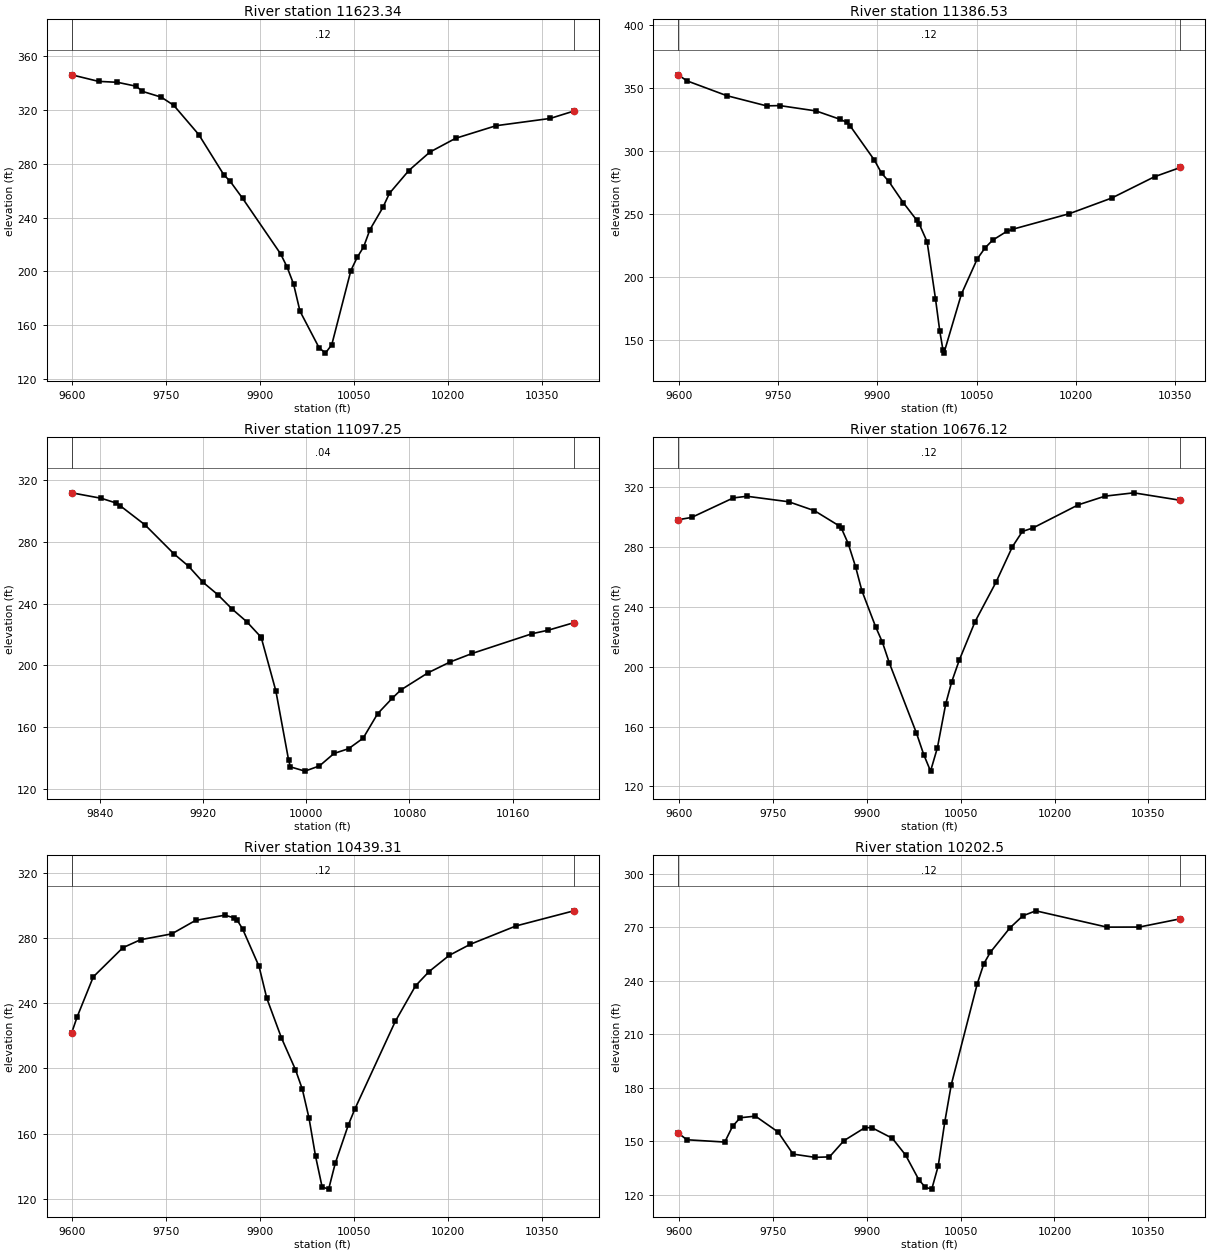
Type RM Length L Ch R = 1 ,11623.34,236.806400,236.806400,236.806400
XS GIS Cut Line= 6
666552.394146431847615.268091033666668.416175478847608.373232522
 666815.52363244847608.769329181 666940.38221749847627.945027016
667087.637620484 847595.56603194667330.083412642847499.723469131
#Sta/Elev= 30
9599.179346.33739641.916341.46449671.967340.77869701.995337.85999712.004334.0245
9742.007329.73869762.007323.65139802.007301.84999842.008271.93039852.008267.1763
9872.039254.38729932.746213.06389943.036203.26649953.325190.73489963.615170.4454
9994.019143.322910004.21139.239210014.37 145.47710044.87200.672810055.03210.5639
10065.19218.229210075.36231.174610095.99247.625610106.36258.093910137.47275.1421
10170.97288.827910212.05299.085110276.78308.480610363.09313.874210400.94319.3684
#Mann= 3 , 0 , 0
9599.179    0.12       09599.179    0.12       010400.94    0.12       0
#XS Ineff= 2 , 0
       0                               0
Bank Sta=9599.179,10400.94
Exp/Cntr=0.3,0.1

Type RM Length L Ch R = 1 ,11386.53,289.281800,289.281800,289.281800
XS GIS Cut Line= 6
666392.144548251847701.671775188 666531.83252979847691.131476584
666650.333934107847704.268800299 666724.77864696847733.950194562
666856.375754609847817.911537174667100.989678179847729.814942844
#Sta/Elev= 30
9599.179360.46389612.104 355.7459672.431343.95949732.503335.87329752.528336.0826
9807.405331.83359843.215325.27879853.381322.93069858.804319.98599895.244 292.992
9906.138282.60949917.214275.97169939.121259.09049959.604245.10019963.136242.2439
9975.012 228.1719987.605183.18279994.168157.2386    9999 142.28410000.38139.9348
 10026.8 186.727 10050.8214.678610062.53223.328910073.85229.399610095.03236.3316
10105.08238.221410189.64250.398710253.83262.839310318.41279.712110357.36287.0362
#Mann= 3 , 0 , 0
9599.179    0.12       09599.179    0.12       010357.36    0.12       0
#XS Ineff= 2 , 0
       0                               0
Bank Sta=9599.179,10357.36
Exp/Cntr=0.3,0.1

Type RM Length L Ch R = 1 ,11097.25,421.137200,421.137200,421.137200
XS GIS Cut Line= 3
666627.738955051 848205.35027732666753.567086309847962.472721651
666820.870505363847868.833182141
#Sta/Elev= 30
9818.467311.65499841.386308.10459852.648305.1119 9855.99303.28129875.173290.9434
9897.697 272.118 9908.96264.16659920.222253.71639931.484245.85139942.747236.4321
9954.009228.28229964.685218.65519965.271217.88859976.534183.53039986.424138.7204
9987.796 134.4379999.058131.679210010.32135.066610021.58 143.11210032.85146.1816
10044.11152.971110055.37 168.83710066.63178.783310073.38184.204610094.46 195.307
10111.59202.303910128.73207.8337 10175.1220.572710187.41222.800910207.32227.6693
#Mann= 3 , 0 , 0
9818.467    0.04       09818.467    0.04       010207.32    0.04       0
#XS Ineff= 2 , 0
       0                               0
Bank Sta=9818.467,10207.32
Exp/Cntr=0.3,0.1

Type RM Length L Ch R = 1 ,10676.12,236.806300,236.806300,236.806300
XS GIS Cut Line= 6
666912.636264006848283.950322527667078.392435891  847905.2599682
667107.852591038847859.110937358667151.753491191847816.455663881
667211.910259287847776.837387658 667393.91807303847694.221317178
#Sta/Elev= 30
9599.052298.24079620.473299.77419686.998312.81819708.814313.91669775.524310.2384
9816.666304.26419855.615294.25029859.806292.41249870.592282.18659882.313266.7277
9892.316250.81339914.265226.7246 9925.24216.22589936.214202.46189979.502155.6233
9991.088141.285610002.02130.195610012.93145.7769 10026.3175.245210035.77189.8399
10047.85204.340410073.07230.090910106.56 256.48410132.76280.217110148.62290.3719
10165.93292.811910237.98308.207910280.76314.013710326.54316.219410400.89311.2379
#Mann= 3 , 0 , 0
9599.052    0.12       09599.052    0.12       010400.89    0.12       0
#XS Ineff= 2 , 0
       0                               0
Bank Sta=9599.052,10400.89
Exp/Cntr=0.3,0.1

Type RM Length L Ch R = 1 ,10439.31,236.806400,236.806400,236.806400
XS GIS Cut Line= 6
666884.407163871848401.659545785 667025.47007381848219.178463491
667092.831665977848159.503894694667138.695535075 848136.73491839
667213.844686504848113.415121519667542.640235771847991.066127665
#Sta/Elev= 30
9599.086222.09289607.677231.72749633.479256.35539680.681274.27149708.933279.1757
9758.791282.76969796.758291.0532  9843.5294.25959857.898292.68989863.383291.1264
9871.858285.86979898.216262.73269910.542243.1976 9934.03218.73029956.395199.2307
9967.301187.25739977.944169.57329988.434146.03059998.923127.137310009.37125.8081
10019.83141.608310040.76165.251210051.26175.100510115.82228.9835 10148.1250.8085
10169.62259.5615 10201.9269.545710235.34276.328710308.63 287.66110400.96296.9456
#Mann= 3 , 0 , 0
9599.086    0.12       09599.086    0.12       010400.96    0.12       0
#XS Ineff= 2 , 0
       0                               0
Bank Sta=9599.086,10400.96
Exp/Cntr=0.3,0.1

Type RM Length L Ch R = 1 , 10202.5,236.806300,236.806300,236.806300
XS GIS Cut Line= 6
666954.894863995848513.195272065667115.845085067848400.685827778
667182.120711689848362.757612776667238.238628483848336.635636043
 667488.62096708848263.427290557667688.833230551848213.810882644
#Sta/Elev= 30
9599.074154.47159613.004150.74139673.403 149.457 9685.77158.22719697.992163.0794
9722.394163.98219758.435 155.1199782.463142.69679817.561140.87699840.605141.1331
9863.648 150.2139897.089157.49499908.119157.55319940.925151.59519962.142142.2057
9983.243128.39529993.613 124.10910004.01123.063910014.39136.164310024.78160.7094
10035.16181.6092 10076.7238.222410087.09249.379210097.47255.808910128.63269.4585
 10149.4276.289510170.17279.103710283.96269.957910335.44270.001810400.99274.6271
#Mann= 3 , 0 , 0
9599.074    0.12       09599.074    0.12       010400.99    0.12       0
#XS Ineff= 2 , 0
       09894.683                       0
Bank Sta=9599.074,10400.99
Exp/Cntr=0.3,0.1

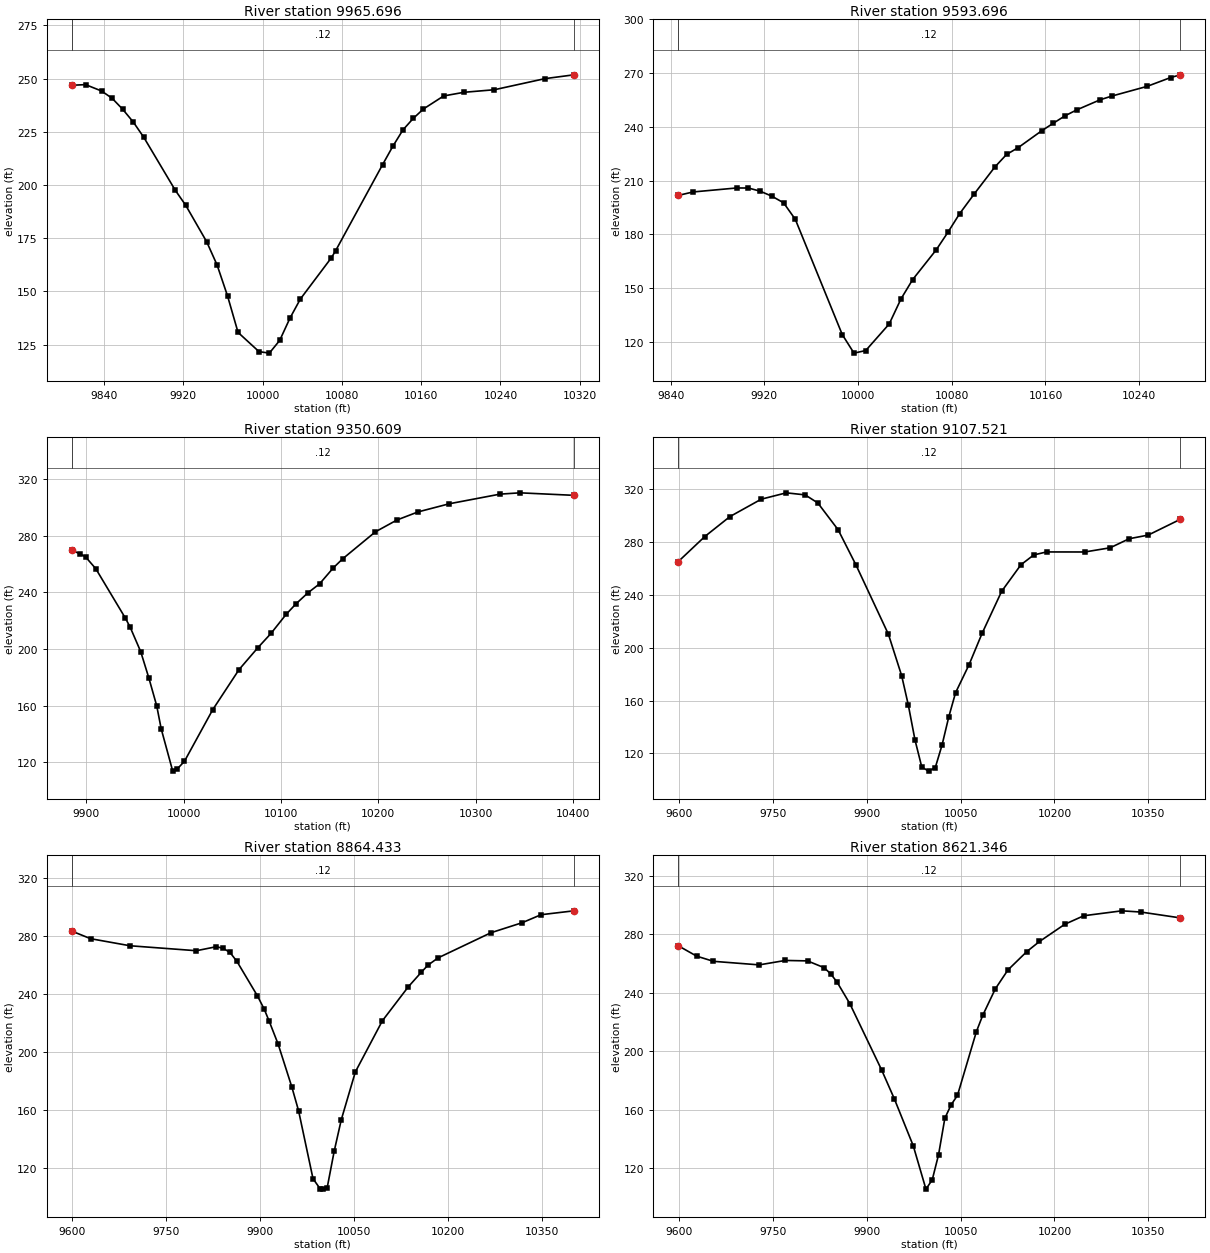
Type RM Length L Ch R = 1 ,9965.696,372.000000,372.000000,372.000000
XS GIS Cut Line= 6
667166.816469609848609.890221221667227.179908738848587.279957744
667343.273016344848547.685071159 667424.91063906848523.284221225
667493.469322676848505.958578294667653.613810281848472.328287225
#Sta/Elev= 30
9807.355 246.8899821.297247.18689837.451244.1879 9848.13240.75179858.808 235.578
9869.487229.57829880.077222.40519911.774197.58819922.339190.50479943.471 173.388
9954.036 162.4199964.602147.83679975.168130.76099996.289121.748410006.75121.0351
10017.19127.004310027.62 137.53310038.05146.456810069.34165.832710073.66169.1816
10121.03209.600310131.35218.208810141.66225.970210151.96231.306110162.21235.7394
 10182.7241.879310203.19243.586710233.92244.796310284.88250.002210314.05251.7954
#Mann= 3 , 0 , 0
9807.355    0.12       09807.355    0.12       010314.05    0.12       0
#XS Ineff= 2 , 0
       0                               0
Bank Sta=9807.355,10314.05
Exp/Cntr=0.3,0.1

Type RM Length L Ch R = 1 ,9593.696,243.087700,243.087700,243.087700
XS GIS Cut Line= 6
667285.118296755848903.073010168667350.733210857 848905.73717276
667392.997960642848904.406546468667519.778071705848895.580985509
667573.447268242848893.808757303 667713.35563652848895.116595962
#Sta/Elev= 30
9846.465201.76699859.111203.69539896.398205.92799906.403205.89499916.409204.1262
9926.414201.33889936.419197.63739946.424188.40249986.495124.09939996.516113.7245
10006.54115.168510026.59 130.00810036.62143.972110046.64154.8075 10066.7171.3571
10076.72181.195110086.74191.591710099.12202.544510116.76 217.61110126.76224.6168
10136.77 228.46610156.77237.844610166.77242.099910176.77246.233810186.77249.5324
10206.77255.177810216.77257.248610246.77262.641210266.77267.544910275.13269.0855
#Mann= 3 , 0 , 0
9846.465    0.12       09846.465    0.12       010275.13    0.12       0
#XS Ineff= 2 , 0
       0                               0
Bank Sta=9846.465,10275.13
Exp/Cntr=0.3,0.1

Type RM Length L Ch R = 1 ,9350.609,243.087600,243.087600,243.087600
XS GIS Cut Line= 6
667283.625254881849030.037881157667328.407077992849069.710009694
667402.541874199849157.138649258667476.621461379849214.628318186
667583.888251598849263.213755176667709.191015104849293.606333187
#Sta/Elev= 30
9885.261269.69449893.431267.51919899.579265.03229909.897256.82739940.399 221.732
9945.221 215.4159956.056198.10889964.489179.31529972.489159.7877 9977.09143.5207
9988.923113.56969993.524115.0264   10001120.563910029.97157.003910057.05185.4366
10076.52201.029110089.81210.969510105.42 224.52310115.46231.905410127.61239.6368
10139.76246.113410153.88 257.42310163.38263.757910197.09282.905310219.27291.2889
10240.77296.972410272.98302.759710325.01309.562910345.51310.491510400.85308.7163
#Mann= 3 , 0 , 0
9885.261    0.12       09885.261    0.12       010400.85    0.12       0
#XS Ineff= 2 , 0
       0                               0
Bank Sta=9885.261,10400.85
Exp/Cntr=0.3,0.1

Type RM Length L Ch R = 1 ,9107.521,243.087700,243.087700,243.087700
XS GIS Cut Line= 6
666812.633426777849237.088747267666942.818594823849231.926788859
667058.934188029 849243.31664462 667147.59878524849264.793840221
 667315.90294327849325.654481255667595.871274415849374.709644299
#Sta/Elev= 30
9599.067265.33419641.533284.33889681.605299.4301 9731.61 312.609  9771.7317.4335
9801.808315.87039822.003 309.7569854.452289.44169883.006262.72019934.754210.2942
9955.914178.92159966.522156.73319977.185130.2888 9987.98109.81929998.775106.6398
10009.58109.283810020.39126.365310031.19147.8045   10042 166.02410063.49187.1972
10084.36211.006410115.65242.866910146.42262.954810166.91270.3914 10187.3272.6602
10248.38 272.62610288.92 275.81310319.32 282.66610349.61285.418710400.95297.3587
#Mann= 3 , 0 , 0
9599.067    0.12       09599.067    0.12       010400.95    0.12       0
#XS Ineff= 2 , 0
       0                               0
Bank Sta=9599.067,10400.95
Exp/Cntr=0.3,0.1

Type RM Length L Ch R = 1 ,8864.433,243.087700,243.087700,243.087700
XS GIS Cut Line= 6
 666896.37486559849653.461288108667122.293655813849576.443570268
667312.999963573849484.141369478667385.833151389849456.878032923
667504.323150719849438.263011056667657.415745121 849437.37623166
#Sta/Elev= 30
9599.081283.35159629.144278.10729692.156273.22229798.098269.80099830.048272.5845
9841.326271.38489851.756268.59349862.727262.4911 9895.64238.58549906.611229.2522
9914.264221.20689928.553205.42579950.584175.61419961.297159.27939984.307112.4403
9995.548 105.536   10001105.201710006.96106.187610018.23131.5724 10029.5153.1587
10051.95186.153110095.11221.440910136.51244.896310157.45 255.03110167.68 259.755
10183.88264.826910268.43282.213210318.44289.156210348.44294.662410400.86297.3455
#Mann= 3 , 0 , 0
9599.081    0.12       09599.081    0.12       010400.86    0.12       0
#XS Ineff= 2 , 0
       0                               0
Bank Sta=9599.081,10400.86
Exp/Cntr=0.3,0.1

Type RM Length L Ch R = 1 ,8621.346,243.087600,243.087600,243.087600
XS GIS Cut Line= 6
666971.423387334 849823.95016408667137.044495304849773.338101641
667256.225239936849744.907278532667347.638709937849730.822511076
667545.522615909849706.358135803667757.242549387849673.042250929
#Sta/Elev= 30
9599.027272.27989628.497265.14869655.259261.61139728.416259.17499770.091262.2149
9805.505261.90459832.085257.24349842.361253.10789852.592 247.4639873.055232.6492
9923.885187.21439944.121167.49549974.475135.17549994.669105.554310004.73111.9128
10014.81 129.08810024.88154.115710034.96163.364510045.04169.781210075.27213.4686
10085.35224.567110105.51242.757610125.66255.7012 10155.9268.320410176.05275.1952
 10216.5287.002710246.87 292.842 10307.6296.203810337.97295.370110400.98291.3602
#Mann= 3 , 0 , 0
9599.027    0.12       09599.027    0.12       010400.98    0.12       0
#XS Ineff= 2 , 0
       0                               0
Bank Sta=9599.027,10400.98
Exp/Cntr=0.3,0.1

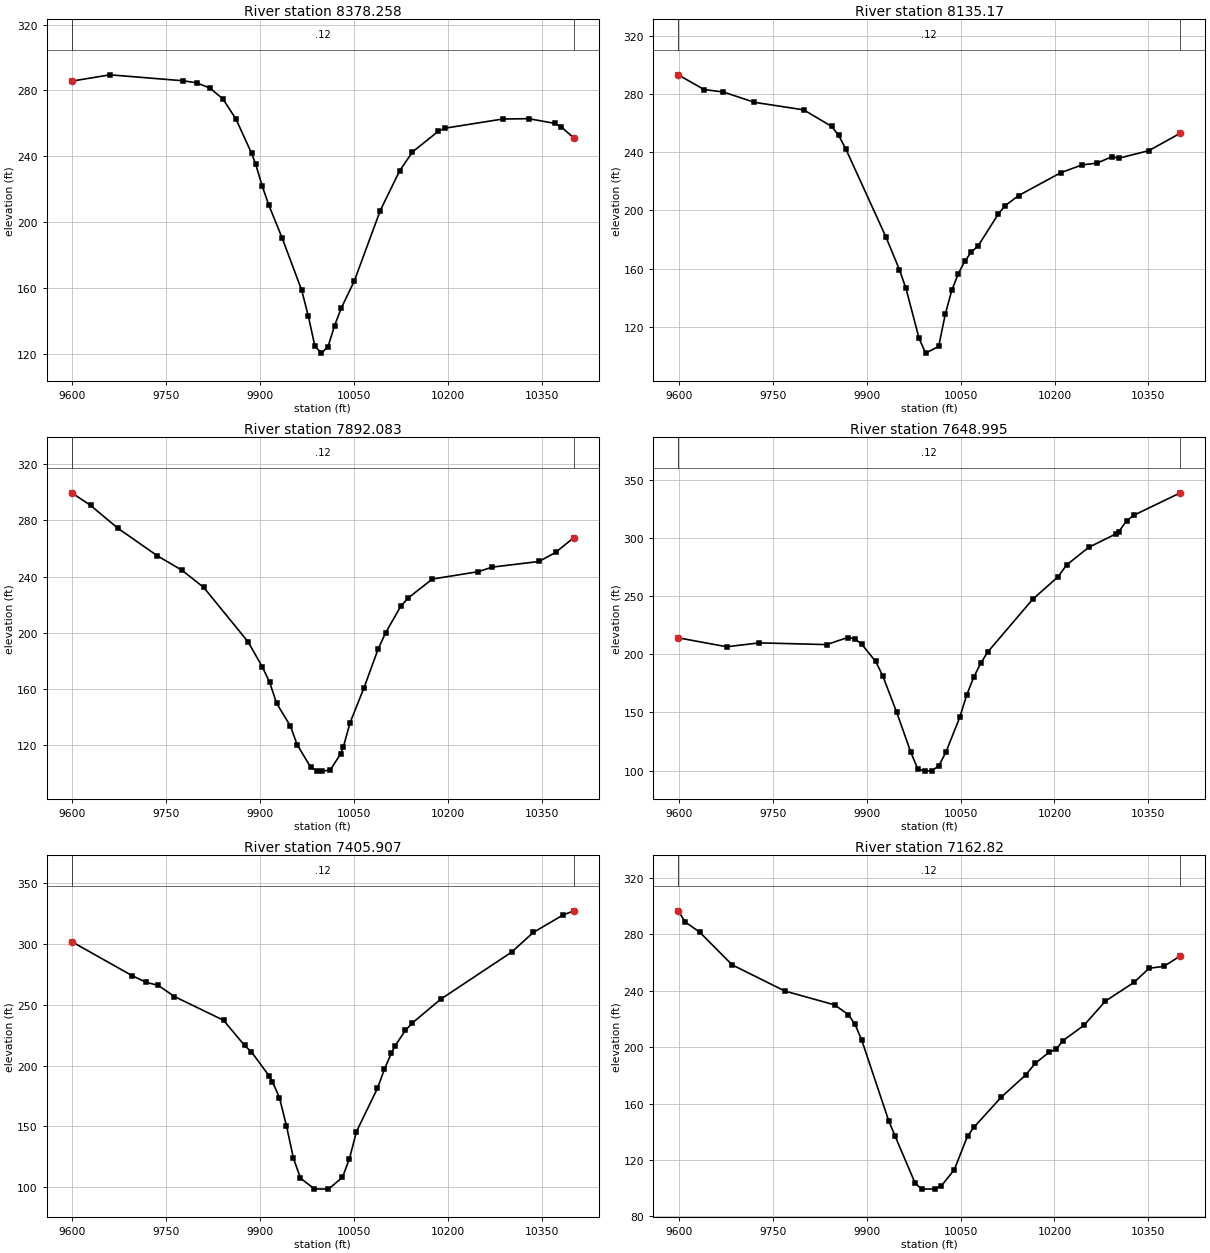
Type RM Length L Ch R = 1 ,8378.258,243.087700,243.087700,243.087700
XS GIS Cut Line= 6
666988.018524712850100.629295285  667143.6760514850041.743986157
667410.471162589849956.376955444667468.874947984849940.485014914
667631.925691275849902.043533821667754.167592276849866.379026314
#Sta/Elev= 30
9599.016285.67159660.245289.48149777.346285.84849798.341284.61329819.337281.5141
9840.332274.89469861.327262.56839886.225241.7772 9892.82235.13769903.318221.7823
9913.816210.29059934.811190.58039966.304158.57759976.802142.9931  9987.3124.7228
9997.797120.422410008.31124.312210018.82137.132110029.32147.664210050.27 164.193
10091.73206.994210122.67231.163610143.22242.635410184.32255.147110194.59257.0291
10287.25262.628310328.91262.847910370.58259.9759   10381 257.83710400.97 251.061
#Mann= 3 , 0 , 0
9599.016    0.12       09599.016    0.12       010400.97    0.12       0
#XS Ineff= 2 , 0
       0                               0
Bank Sta=9599.016,10400.97
Exp/Cntr=0.3,0.1

Type RM Length L Ch R = 1 , 8135.17,243.087700,243.087700,243.087700
XS GIS Cut Line= 6
667079.015060103850370.263993742667315.291061278850244.845841397
667393.263695155850214.001802182667517.108010293850176.427483321
667586.161112395850147.436574706667797.650977802850021.878515179
#Sta/Elev= 30
9599.071293.35449640.352 283.2169671.033281.54129720.654274.43389799.552269.2163
9844.086257.82829855.219251.64249866.353242.63169930.887181.61069952.342159.2004
 9962.79146.28369983.687111.92629994.135101.750910015.04106.358310025.49128.4289
10035.94144.977410046.39156.505910056.84165.074610067.29171.481310077.74175.3796
 10110.2197.492110121.04203.223410142.73210.236810209.93  225.9610244.01231.3262
10268.01232.590610291.61236.970510303.41236.0161 10350.6 241.14910400.93253.1435
#Mann= 3 , 0 , 0
9599.071    0.12       09599.071    0.12       010400.93    0.12       0
#XS Ineff= 2 , 0
       0                               0
Bank Sta=9599.071,10400.93
Exp/Cntr=0.3,0.1

Type RM Length L Ch R = 1 ,7892.083,243.087600,243.087600,243.087600
XS GIS Cut Line= 6
667365.847967723850721.268923441667527.629755385850504.550946682
667599.418011397850334.506625345667637.013407636850271.764656044
667715.161789425850179.962336271667826.872536455850076.762855093
#Sta/Elev= 30
9599.044299.70419628.968290.78489672.277274.57679735.664254.81519774.866 244.516
9809.792232.22049880.707193.36229903.589175.3619 9915.03164.62879926.123149.6278
9948.206133.3751 9958.99120.05569980.372104.1194 9990.83 101.239    9999101.1734
10011.76101.859310028.68113.702410032.81118.4554 10043.6135.820410065.69 160.499
10088.36188.337410100.33199.877810124.28218.661410136.76224.845410174.97 238.208
10248.55243.467310270.32246.689310345.25250.722710371.84257.199310400.92267.7522
#Mann= 3 , 0 , 0
9599.044    0.12       09599.044    0.12       010400.92    0.12       0
#XS Ineff= 2 , 0
       0                               0
Bank Sta=9599.044,10400.92
Exp/Cntr=0.3,0.1

Type RM Length L Ch R = 1 ,7648.995,243.087700,243.087700,243.087700
XS GIS Cut Line= 6
667618.217789831850820.937029599667712.057818394850661.274367101
667848.445929109 850390.02319874 667895.47235602850302.523529175
667956.380382144850206.573913287668017.457981529850127.310478959
#Sta/Elev= 30
9599.023214.18589676.456206.5068 9728.78209.85959836.058208.36229869.638214.4562
9880.831213.42439892.024208.7547 9914.41193.82299925.604181.6068 9947.99150.0825
9970.377 115.895 9981.57101.43289992.763 99.468810003.9599.8573410015.14  103.91
10026.34115.540610048.72 145.78610059.92165.201910071.11180.4186 10082.3192.4112
10093.57202.112610165.09 247.30810205.61266.707910219.38276.907110254.62292.0357
10298.41303.710810302.85305.566810315.32315.0801 10327.8319.960710400.98338.9827
#Mann= 3 , 0 , 0
9599.023    0.12       09599.023    0.12       010400.98    0.12       0
#XS Ineff= 2 , 0
       0                               0
Bank Sta=9599.023,10400.98
Exp/Cntr=0.3,0.1

Type RM Length L Ch R = 1 ,7405.907,243.087600,243.087600,243.087600
XS GIS Cut Line= 6
667837.136552227 850938.05469534 667875.49109794850872.492482404
667923.372433974850783.411313214668124.718792924850380.727501082
668175.766778604850289.475810864668213.190615091850230.203829415
#Sta/Elev= 30
9599.012301.87649695.053274.04649717.534268.53899737.297265.92969762.946256.8121
9841.386 237.2799874.915216.67629886.091211.2361  9914.1191.68779919.621186.6811
9930.797173.58199941.974150.4361 9953.15123.81129964.326107.49849986.67998.61463
10009.0498.48865 10031.4108.172210042.59123.579310053.77145.786810087.33181.4345
10098.51197.1477 10109.7210.524310115.31216.205410132.06229.035710143.25235.1526
10187.99254.477510301.63293.323110336.17309.460410383.48323.737410400.98327.2428
#Mann= 3 , 0 , 0
9599.012    0.12       09599.012    0.12       010400.98    0.12       0
#XS Ineff= 2 , 0
       0                               0
Bank Sta=9599.012,10400.98
Exp/Cntr=0.3,0.1

Type RM Length L Ch R = 1 , 7162.82,243.087700,243.087700,243.087700
XS GIS Cut Line= 6
668080.636387133851024.284784949668145.850779485850913.390994137
668204.116268437 850795.63213527668276.497833401850587.176311504
668318.599970119 850488.57844133668423.508185511850302.491957281
#Sta/Elev= 30
9599.052296.49229609.918288.69849633.325281.38539685.187258.21279769.256239.7034
9848.779229.88289870.574223.03349881.338216.18689892.102204.99379935.159147.8463
9945.073137.28329977.279103.73169987.73999.38484 10008.699.5204110019.01101.5606
10039.96113.142210061.11136.947210071.69 143.37910114.61164.362310154.07180.2699
10169.19188.4264 10191.2196.306810202.39198.357510213.58204.565610247.14215.4376
10281.32232.5323 10327.2245.886610351.12255.827310374.57257.142510400.96264.5383
#Mann= 3 , 0 , 0
9599.052    0.12       09599.052    0.12       010400.96    0.12       0
#XS Ineff= 2 , 0
       0                               0
Bank Sta=9599.052,10400.96
Exp/Cntr=0.3,0.1

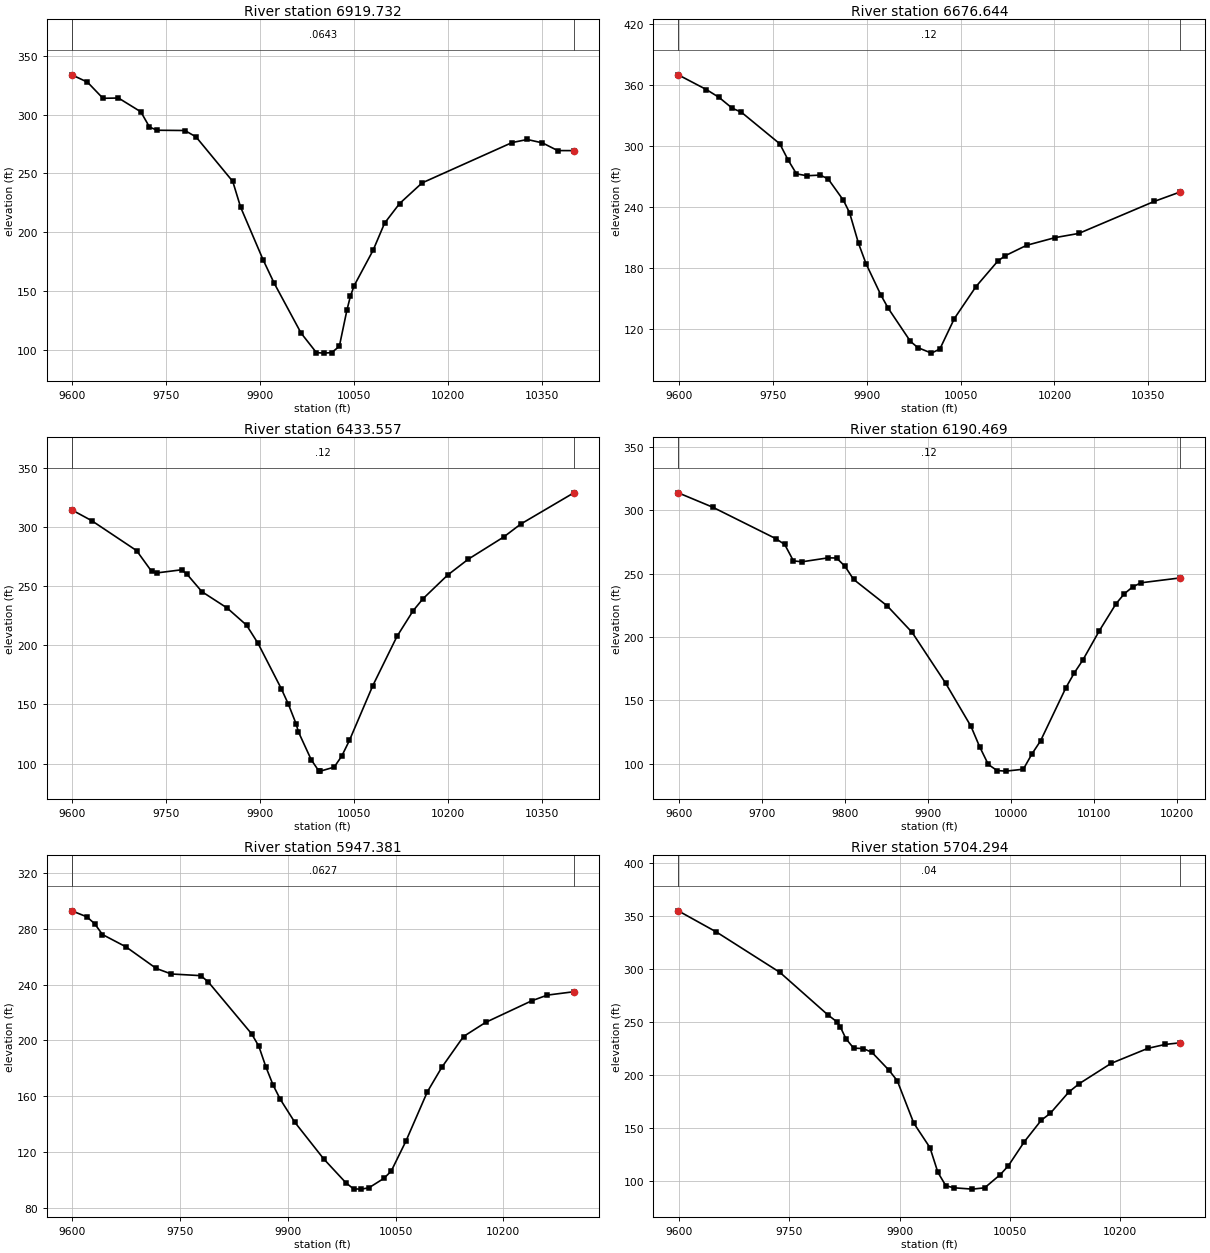
Type RM Length L Ch R = 1 ,6919.732,243.087700,243.087700,243.087700
XS GIS Cut Line= 6
668229.885882389851115.187307752668305.071124813851012.404970421
668417.850629351850846.214048838668488.391869863850745.659851307
668621.062511426850543.902945131668683.166081297 850453.74054365
#Sta/Elev= 30
9599.015333.96859624.027327.75749648.807313.99239673.587314.22949709.303302.5062
9723.146289.5455 9735.31286.8036 9779.66286.57649797.469281.16669856.162243.2485
9868.704221.35079904.503176.7023 9922.13156.83049965.331114.1279 9989.7697.54973
10001.9997.10859 10014.297.5678110026.41102.909610038.63133.987610044.13145.6228
10050.04 154.49510080.26184.5679 10098.7207.738210122.64224.412410158.54241.9647
10302.32276.3144 10326.6278.929210350.89276.032610375.17269.491310400.99269.4644
#Mann= 3 , 0 , 0
9599.015  0.0643       09599.015  0.0643       010400.99  0.0643       0
#XS Ineff= 2 , 0
       0                               0
Bank Sta=9599.015,10400.99
Exp/Cntr=0.3,0.1

Type RM Length L Ch R = 1 ,6676.644,243.087600,243.087600,243.087600
XS GIS Cut Line= 6
668411.823106847851229.065425656668503.924684705851141.156718372
668579.578730871851049.757163865668672.757029492850903.931037882
668781.477467425 850719.19201053668878.509119225850581.594785772
#Sta/Elev= 30
9599.037370.16669644.072 355.6249664.199347.93889685.459337.15629699.609333.4447
9761.231 302.1859774.552286.19419787.873272.56379804.554270.68959825.944271.3195
9838.516267.5243  9862.9246.46839872.713 234.2289887.014203.9613 9899.07183.8919
9922.736153.0706 9934.52139.9766 9969.87107.45859981.654101.308710003.39 95.8432
10016.9399.8828410040.05129.916810074.71161.518210109.36186.499710120.91191.7161
10155.56 202.15110200.96209.697510238.86213.838410359.28 245.38110400.97254.7502
#Mann= 3 , 0 , 0
9599.037    0.12       09599.037    0.12       010400.97    0.12       0
#XS Ineff= 2 , 0
       0                               0
Bank Sta=9599.037,10400.97
Exp/Cntr=0.3,0.1

Type RM Length L Ch R = 1 ,6433.557,243.087700,243.087700,243.087700
XS GIS Cut Line= 6
668574.167313988 851250.27564329668744.518668539 851155.10179317
 668815.77344407851101.651945664668977.400864106850891.344497884
669051.017337507850813.985875145669157.859609256850715.778949326
#Sta/Elev= 30
 9599.07314.60089630.934305.47169702.571280.14869726.438 262.6919734.815261.2607
9774.554263.92449783.206 260.0979806.929245.3858 9847.18231.59249878.209217.0727
9896.658201.57089933.749163.26559945.078150.12019957.229133.73729961.044  126.79
9981.532103.17549993.68493.662639996.247 93.564810018.1796.95893 10030.4106.4194
10042.63119.696110079.94166.001310118.56207.645310144.31229.305510160.04239.4432
10199.19259.372610232.57272.9717 10288.8291.624610316.31302.662510400.94329.0329
#Mann= 3 , 0 , 0
 9599.07    0.12       0 9599.07    0.12       010400.94    0.12       0
#XS Ineff= 2 , 0
       0                               0
Bank Sta=9599.07,10400.94
Exp/Cntr=0.3,0.1

Type RM Length L Ch R = 1 ,6190.469,243.087700,243.087700,243.087700
XS GIS Cut Line= 6
668567.255272537851276.673605829668684.131000578851226.268268213
668784.096930802851200.749925882 668866.26144436851201.072702572
669051.533694118 851244.59604539669151.986260116851239.133002564
#Sta/Elev= 30
9599.171 313.7149640.766302.34879716.708277.54639727.422 272.9369737.908259.9797
9748.393259.28639779.691262.39429789.901262.26279800.111255.6119 9810.32245.4005
9850.763 224.519 9880.83203.56539921.102163.55489951.739129.40249962.056113.4518
9972.57899.330349983.09994.48894 9993.6294.0329710014.7795.5209510025.21107.6512
10035.51117.896210066.16160.016910076.25171.657210086.33 181.58210106.48205.0079
10126.48226.208510136.48234.061710146.48239.453410156.52242.699910203.85246.5665
#Mann= 3 , 0 , 0
9599.171    0.12       09599.171    0.12       010203.85    0.12       0
#XS Ineff= 2 , 0
       0                               0
Bank Sta=9599.171,10203.85
Exp/Cntr=0.3,0.1

Type RM Length L Ch R = 1 ,5947.381,243.087600,243.087600,243.087600
XS GIS Cut Line= 6
668475.806652516851498.388971746668663.709528387851435.330952287
668811.207051873851434.147659212668966.684918046 851466.93272303
 669046.16828692851452.188937858 669148.68663016851409.328189462
#Sta/Elev= 30
9599.189293.15329620.111288.87079631.011283.93639641.911276.13259674.612267.2863
9716.831251.75789737.752247.78179778.792246.58369789.052 242.1799849.611204.7716
9859.612 195.8889869.613180.80549879.613167.83979889.614157.64189909.687 141.283
9949.976114.92329980.75397.823869991.44293.3931710002.2793.2119910012.8994.15639
10033.64100.914410043.84106.048310064.23127.4822 10094.3163.151110114.36180.7135
10144.61202.864410175.53213.035810239.38228.470310261.23232.599110298.23235.0307
#Mann= 3 , 0 , 0
9599.189  0.0627       09599.189  0.0627       010298.23  0.0627       0
#XS Ineff= 2 , 0
       0                               0
Bank Sta=9599.189,10298.23
Exp/Cntr=0.3,0.1

Type RM Length L Ch R = 1 ,5704.294,243.087700,243.087700,243.087700
XS GIS Cut Line= 6
668741.293904573851957.986178979668831.228059381851878.419552967
 668898.50386402851796.561749652668997.948786616851578.139717847
669031.707210541851526.410377473 669152.08189705851431.736950964
#Sta/Elev= 30
9599.098354.55239651.081334.60999737.312296.66639802.141256.94689814.706250.2209
9819.521245.34039827.149234.25319837.582225.40919850.721224.98689862.507221.4434
9885.794204.51279896.997194.67159919.403154.8231 9941.41131.79079952.202108.4912
9962.99395.958349973.78594.01993    999992.75527 10015.893.9908710037.01106.3874
 10047.9114.617910069.85137.445510092.84157.624310104.99164.011310130.11183.9965
10144.12191.833910187.74211.045810237.71225.181610261.52228.909410281.86230.3978
#Mann= 3 , 0 , 0
9599.098    0.04       09599.098    0.04       010281.86    0.04       0
#XS Ineff= 2 , 0
       0                               0
Bank Sta=9599.098,10281.86
Exp/Cntr=0.3,0.1

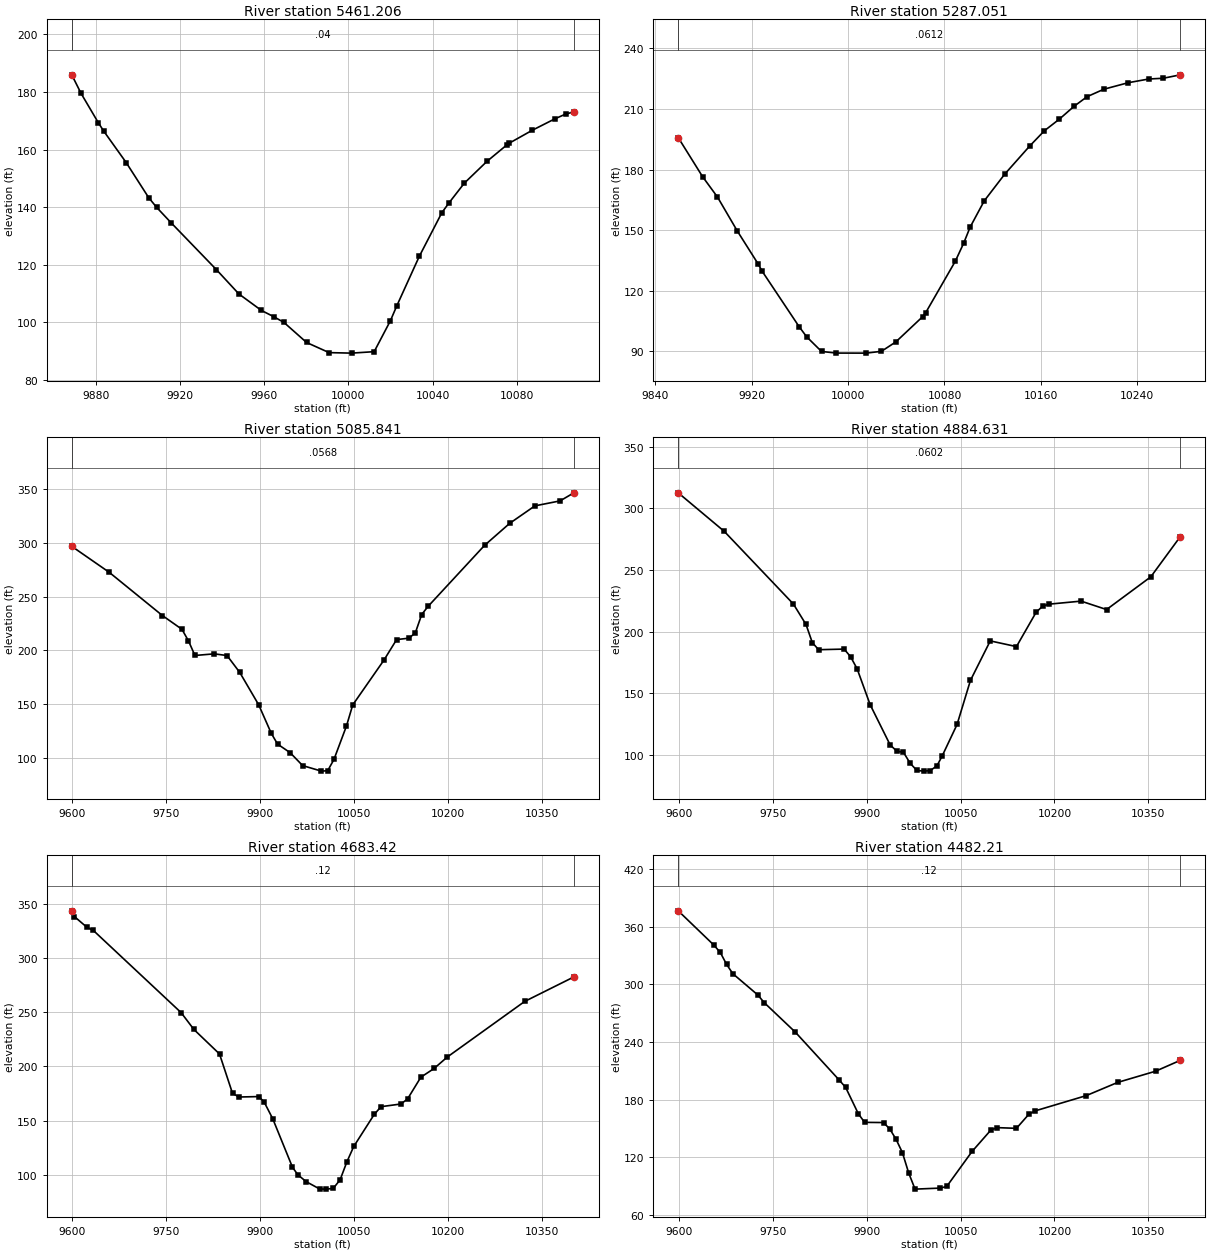
Type RM Length L Ch R = 1 ,5461.206,174.155300,174.155300,174.155300
XS GIS Cut Line= 2
669160.459095001851819.114165083669246.396594971851596.457915097
#Sta/Elev= 30
9868.505185.98269872.915 179.5469881.116169.35899883.634166.50149894.353155.5299
9905.072 143.3169908.888139.91429915.791134.54929937.229118.33649947.948109.8712
9958.667 104.1379964.432102.01019969.38699.969119980.10593.024779990.82489.49482
10001.5489.3190710012.2689.8264810019.98100.590710022.98105.6917 10033.7122.9319
10044.42138.086310047.75141.436210055.14148.386210065.86155.919510075.52161.7611
10076.58162.2875 10087.3166.684610098.01170.645110103.29172.361910107.17173.1014
#Mann= 3 , 0 , 0
9868.505    0.04       09868.505    0.04       010107.17    0.04       0
#XS Ineff= 2 , 0
       0                               0
Bank Sta=9868.505,10107.17
Exp/Cntr=0.3,0.1

Type RM Length L Ch R = 1 ,5287.051,201.210200,201.210200,201.210200
XS GIS Cut Line= 2
669238.584095001851873.801665083669576.474719971851629.661040112
#Sta/Elev= 30
9858.961195.81619879.213176.42569891.551166.34679908.139 149.3979925.213133.2779
9928.562129.65959959.363  102.089965.57497.099139977.91189.829729990.24889.02654
10014.9288.9969310027.6689.89496 10039.694.5430410061.81107.017810064.27108.8815
10088.95134.483410095.96143.484210101.28151.403710113.04164.476410130.11177.7557
10150.63191.549510162.97199.212410175.31204.925810187.64211.346610198.41216.0993
10212.32219.791510232.56223.023410249.63224.861710261.67225.229810275.82226.9314
#Mann= 3 , 0 , 0
9858.961  0.0612       09858.961  0.0612       010275.82  0.0612       0
#XS Ineff= 2 , 0
       0                               0
Bank Sta=9858.961,10275.82
Exp/Cntr=0.3,0.1

Type RM Length L Ch R = 1 ,5085.841,201.210100,201.210100,201.210100
XS GIS Cut Line= 6
669039.179041956 852059.73210964669182.010087928 852007.42880762
669299.344129454851979.788573502669366.863090597851973.343814562
669589.507982824 851966.63091804 669826.78553088851942.578307248
#Sta/Elev= 30
9599.076296.68559658.978272.5176 9743.79232.40119775.062219.57389785.437 208.849
9795.812195.2616 9826.68196.78159847.052195.20929867.423179.4802 9897.62149.4215
9917.711122.93269927.757112.90529947.811 104.9649967.81492.938849997.81887.78886
10007.8288.1737510017.8298.6414710037.82129.731110047.82149.319510097.87 191.123
 10117.9210.031610137.93211.374710147.94216.515610157.95 233.29410167.98240.7882
10258.32297.570610298.53318.056910338.79334.313710379.05338.932910400.98346.4209
#Mann= 3 , 0 , 0
9599.076  0.0568       09599.076  0.0568       010400.98  0.0568       0
#XS Ineff= 2 , 0
       0                               0
Bank Sta=9599.076,10400.98
Exp/Cntr=0.3,0.1

Type RM Length L Ch R = 1 ,4884.631,201.210200,201.210200,201.210200
XS GIS Cut Line= 6
 668992.77056248852130.455559558669118.437786659852110.845468713
669221.424680012852116.636229686 669301.27073991852136.755518005
669548.112234321852223.382927222669771.734895676852261.461702749
#Sta/Elev= 30
9599.112312.6446 9672.71 281.3299783.052222.39129803.167205.81669813.225191.1297
9823.282185.33639864.075185.84149874.347179.63349884.768169.88629905.609140.7209
9937.491108.12579948.173103.00199958.855102.04559969.53793.161679980.21987.37355
  9990.986.8149710001.5987.2398310012.29 91.129910020.6599.1243410044.39124.6528
10065.78160.435810097.42192.497710139.25187.864610170.62215.678610180.95220.6258
10191.23222.298910242.47224.763710283.17217.925510353.83244.484310400.94277.1216
#Mann= 3 , 0 , 0
9599.112  0.0602       09599.112  0.0602       010400.94  0.0602       0
#XS Ineff= 2 , 0
       0                               0
Bank Sta=9599.112,10400.94
Exp/Cntr=0.3,0.1

Type RM Length L Ch R = 1 , 4683.42,201.210100,201.210100,201.210100
XS GIS Cut Line= 6
668910.853275838 852277.73618618669038.022325745852275.510126511
 669139.90049099852292.212134109669225.945027147852319.482359035
669472.435288185852418.325838997669682.379199805 852464.70691421
#Sta/Elev= 30
9599.086343.5193 9603.24338.25079623.275328.33789633.292325.56549773.711249.6761
9794.121  234.159835.036211.54869855.817175.20849866.208171.85349897.864172.2637
9906.393167.15299920.039 151.8559951.561107.10939960.056100.25639973.25893.88718
9994.95687.0691210005.8686.9250610016.7587.6524210027.6595.5268410038.55112.1851
10049.44126.256810082.13155.780610092.89162.927910124.75 165.42210135.36170.0663
 10156.6190.117310177.83198.187510198.79 208.70510322.42259.971910400.95282.5556
#Mann= 3 , 0 , 0
9599.086    0.12       09599.086    0.12       010400.95    0.12       0
#XS Ineff= 2 , 0
       0                               0
Bank Sta=9599.086,10400.95
Exp/Cntr=0.3,0.1

Type RM Length L Ch R = 1 , 4482.21,201.210200,201.210200,201.210200
XS GIS Cut Line= 6
668837.985163081852523.631250976668966.080574747852517.256454338
669098.157867933852523.552425166669211.581144569852537.237840965
669482.198301741852579.787470118669634.402779271852597.217534626
#Sta/Elev= 30
9599.035376.29719656.197340.51849666.223 333.0019676.235320.64319686.237310.9503
9726.247288.7697 9736.25 280.9359786.266250.05019856.425200.18729866.482 192.693
9886.627165.4427  9896.7156.39869926.917156.2006 9936.99149.45369947.063138.6953
9957.135124.88619967.208103.60769977.29586.9879410017.7888.07304 10027.9 89.7872
10068.39126.167810098.76148.661810108.89150.900110139.26150.1881 10159.5 165.126
10169.63168.4314 10250.6184.162210301.01197.943710361.39209.550210400.99 220.864
#Mann= 3 , 0 , 0
9599.035    0.12       09599.035    0.12       010400.99    0.12       0
#XS Ineff= 2 , 0
       0                               0
Bank Sta=9599.035,10400.99
Exp/Cntr=0.3,0.1

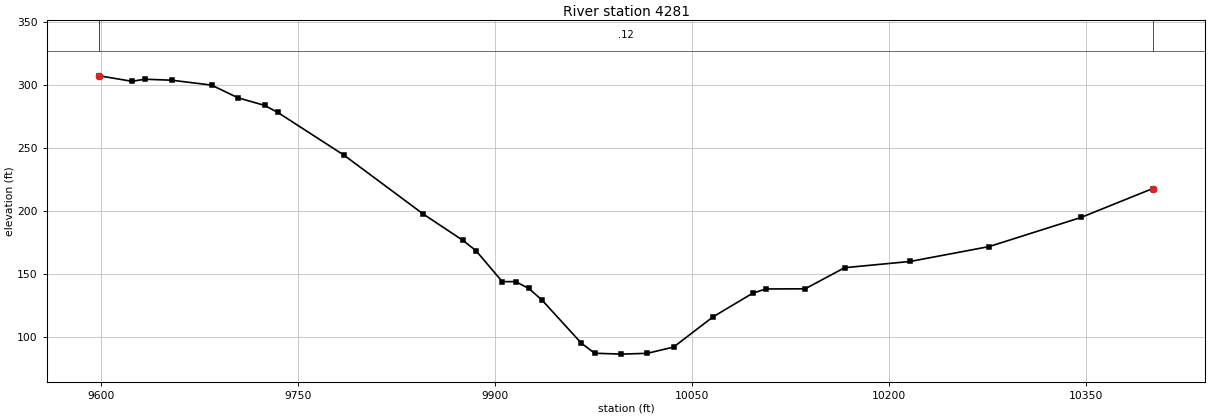
Type RM Length L Ch R = 1 ,    4281,0.000000,0.000000,0.000000
XS GIS Cut Line= 6
668840.557897404852787.063203767 668917.84191448852775.055112493
669018.839001274852762.021871964669201.091281048852744.482143125
669408.900004199852733.040786769669639.560029063852728.511708082
#Sta/Elev= 30
9599.018307.17789623.753302.85729633.873304.47449654.113303.70599684.446299.8125
9704.612289.73249724.778 283.7489734.861278.15479785.253244.2653 9845.53197.6354
9875.669176.78589885.715168.55819905.807143.91719915.854 143.993  9925.9138.6271
9935.946129.42139966.07695.066349976.09887.181859996.14486.4732210016.1887.10614
 10036.292.0796210066.24116.018910096.28134.7122 10106.3138.152910136.34138.2547
10166.38155.004910216.39159.972410276.41 171.76410346.42194.882210400.99217.7959
#Mann= 3 , 0 , 0
9599.018    0.12       09599.018    0.12       010400.99    0.12       0
#XS Ineff= 2 , 0
       0                               0
Bank Sta=9599.018,10400.99
Exp/Cntr=0.3,0.1